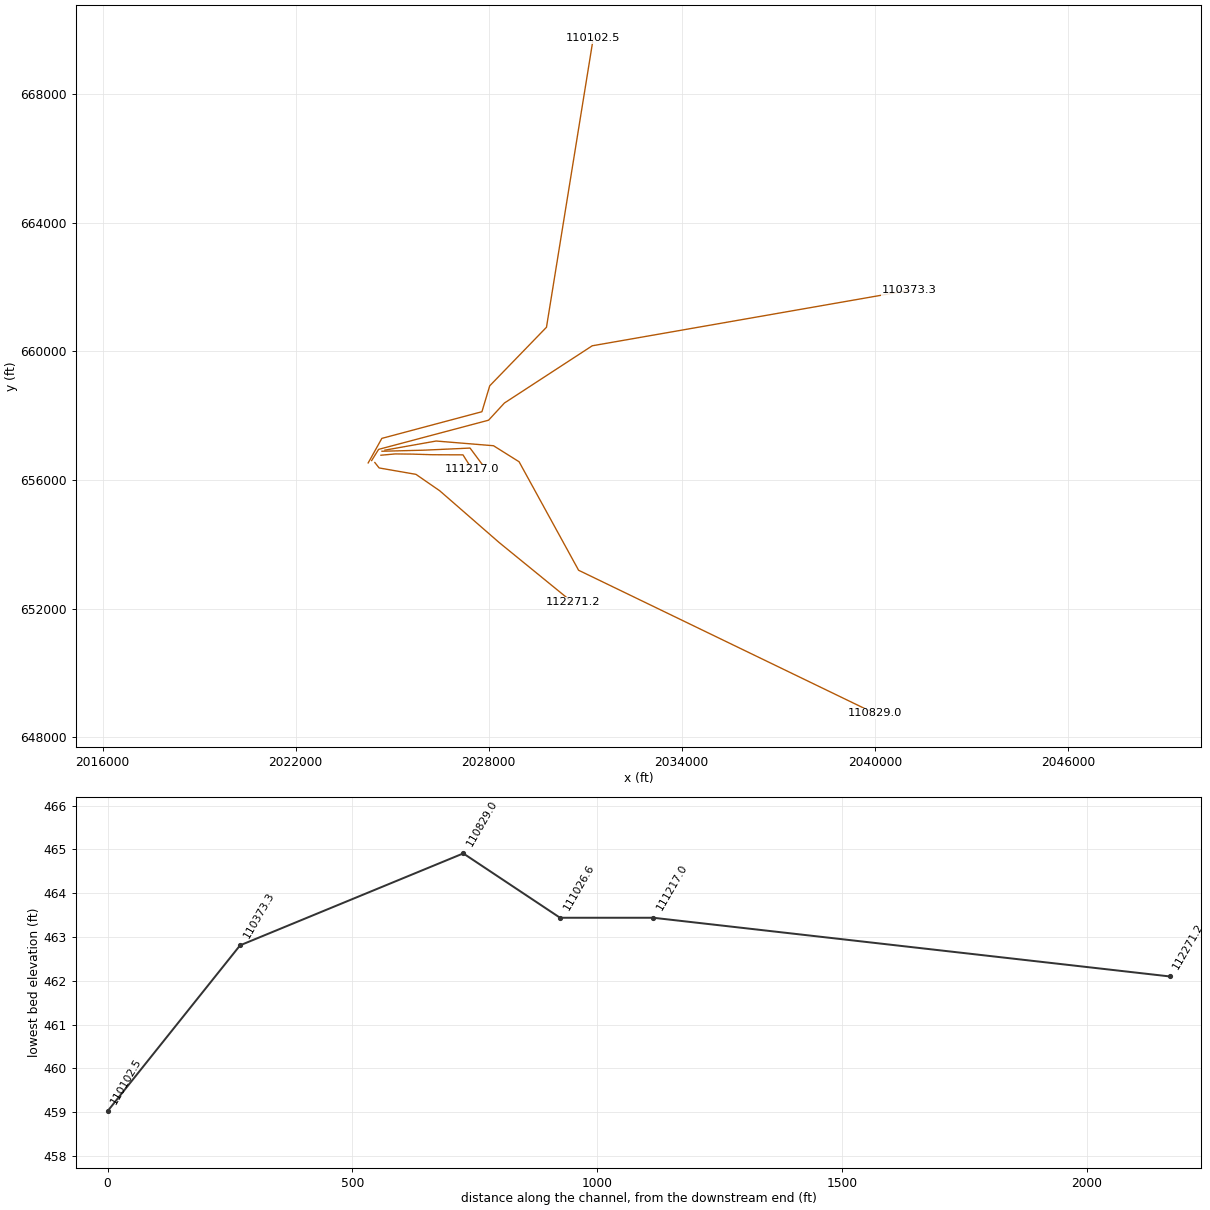
HEC-RAS study CaneyFork.prj: Caney Fork River- Smith County

--- CaneyFork.g02 (geometry) --- (continued)

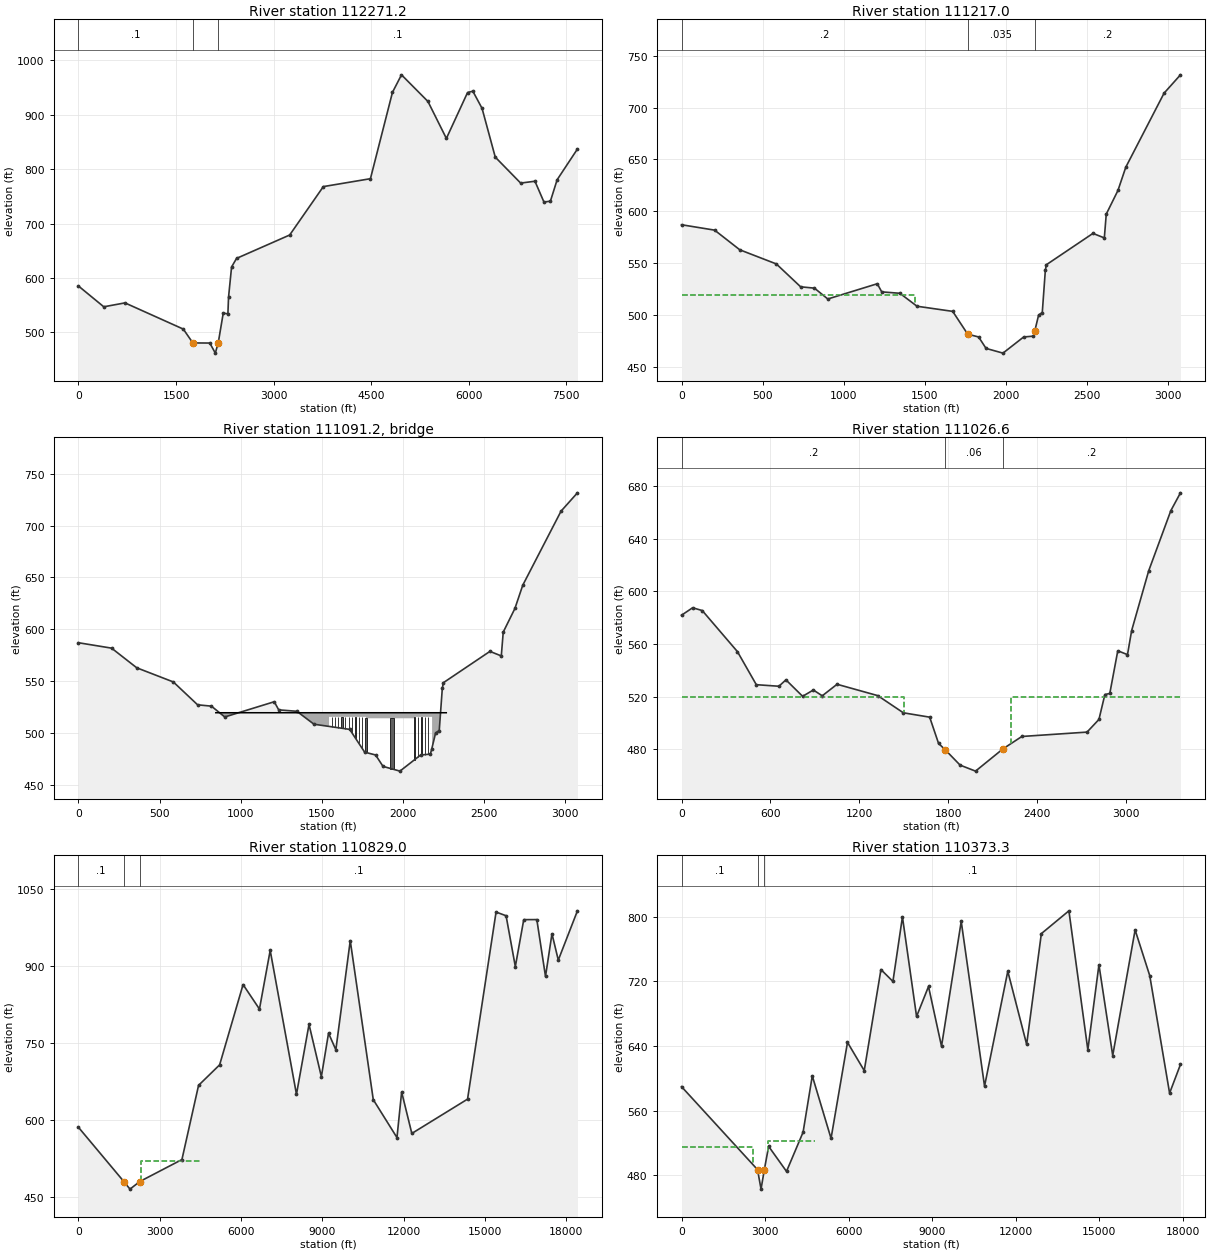
Type RM Length L Ch R = 1 ,112271.2,875.2,1054.2,1178.9
BEGIN DESCRIPTION:
34820.01
END DESCRIPTION:
XS GIS Cut Line= 6
      2024461.57       656544.48      2024594.68       656376.26
       2025739.3       656176.862026479.70833173655665.522059899
      2028330.04       654054.14      2030608.46       652197.92
#Sta/Elev= 30
       0  585.36   388.7  547.22   714.5  554.39  1611.5  506.23    1758  480.84
  2018.4  480.63  2103.4   462.1  2149.3  481.58  2225.2  535.52  2296.9  534.35
  2306.7  564.79  2353.5  620.42  2430.2  636.17  3246.6   679.1    3764  768.04
    4488  782.56  4826.8  941.27  4965.5  973.39  5371.8   924.5  5655.5  856.53
  5981.2   940.9  6062.5   943.3  6203.7  911.84  6406.9  822.21  6797.1  774.51
  7017.1   777.9  7155.3  739.69  7254.6  741.23  7358.1  780.62  7670.2   837.1
#Mann= 3 , 0 , 0
       0      .1       0    1758    .035       0  2149.3      .1       0
Bank Sta=1758,2149.3
XS Rating Curve= 0 ,0
Exp/Cntr=0.5,0.3

Type RM Length L Ch R = 1 ,111217.0,161.4,190.4,201.8
BEGIN DESCRIPTION:
34553.28
END DESCRIPTION:
XS GIS Cut Line= 6
      2024651.16       656771.482025092.79362414656811.554899802
2025624.38503421656806.1782551322026250.79610704656786.688724342
2027200.76742013656782.763616216      2027481.96       656338.64
#Sta/Elev= 30
       0   587.1   204.2   581.9   359.4  562.96     585  549.33   734.7  527.31
   819.9  526.03   902.2  515.59  1207.4  530.27  1234.9  522.44  1346.7  521.08
  1452.5   508.6  1672.6  503.66  1765.1   481.7 1832.47     479 1878.28     468
  1982.6  463.44 2110.32     479  2170.1   479.8  2178.6  484.65  2202.6  500.17
  2225.1  502.57  2243.9  543.06  2250.1  548.56  2537.6  578.77  2607.8  574.41
  2619.7  597.35  2691.8  620.13  2740.2  642.54  2976.2  713.83  3077.4   731.5
#Mann= 3 , 0 , 0
       0      .2       0  1765.1    .035       0  2178.6      .2       0
#XS Ineff= 2 , 0
         1442.37  519.68
Permanent Ineff=
       F       F
Bank Sta=1765.1,2178.6
XS Rating Curve= 0 ,0
Exp/Cntr=0.5,0.3

Type RM Length L Ch R = 3 ,111091.2,,,
BEGIN DESCRIPTION:
RailRoad Trestle
2019 Update:
- Removed trestle as the space is open for flow
-Included Momentum modeling for low flow
END DESCRIPTION:
Bridge Culvert--1,0,-1,-1, 0
Deck Dist Width WeirC Skew NumUp NumDn MinLoCord MaxHiCord MaxSubmerge Is_Ogee
75,20,2.6,0, 24, 25, , , 0.95, 0, 0,0,,
     847    1539  1542.2 1542.23 1545.28 1545.37 1563.43 1603.04 1624.67 1647.12
 1750.39 1772.18 1772.19 1799.79 1907.87    1933 1961.07 2045.33 2072.87 2072.88
 2094.21 2156.69 2180.97 2268.51
  519.68 519.684 519.684 519.684 519.684 519.684 519.684 519.684 519.684 519.684
 519.684 519.684 519.684 519.684 519.684 519.684 519.684 519.684 519.684 519.684
 519.684 519.684 519.684 519.684
                                 503.641   515.7   515.7   515.7   515.7   515.7
   515.7   515.7 514.342 514.342 514.342 514.342 514.342 514.342 514.342   515.7
   515.7   515.7   515.7
  829.75 1538.75 1541.95 1541.98 1545.03 1545.12 1563.18 1602.79 1624.42 1646.87
 1750.14 1771.93 1771.94 1799.54 1905.62 1932.75 1960.82 2045.08 2072.62 2072.63
 2093.96 2156.44 2180.72    2313    2900
  519.68 519.684 519.684 519.684 519.684 519.684 519.684 519.684 519.684 519.684
 519.684 519.684 519.684 519.684 519.684 519.684 519.684 519.684 519.684 519.684
 519.684 519.684 519.684 519.684 519.684
                                 503.641   515.7   515.7   515.7   515.7   515.7
   515.7   515.7 514.342 514.342 514.342 514.342 514.342 514.342 514.342   515.7
   515.7   515.7   515.7
Pier Skew, UpSta & Num, DnSta & Num=  ,1561.71, 2 ,1561.75, 2 , 0 , 0 , 0 ,,
       1       1
 503.234   515.7
       1       1
 503.234   515.7
Pier Skew, UpSta & Num, DnSta & Num=  ,1581.74, 2 ,1581.25, 2 , 0 , 0 , 0 ,,
       1       1
 494.018   515.7
       1       1
 494.018   515.7
Pier Skew, UpSta & Num, DnSta & Num=  ,1602.31, 2 ,1601, 2 , 0 , 0 , 0 ,,
       1       1
 486.179   515.7
       1       1
 486.179   515.7
Pier Skew, UpSta & Num, DnSta & Num=  ,1624.45, 2 ,1624.42, 2 , 0 , 0 , 0 ,,
       8     6.4
 482.828   515.7
       8     6.4
 482.828   515.7
Pier Skew, UpSta & Num, DnSta & Num=  ,1645.66, 4 ,1624.42, 4 , 0 , 0 , 0 ,,
    1.24    1.22       1       1
 478.755 481.857 481.858   515.7
    1.24    1.22       1       1
 478.755 481.857 481.858   515.7
Pier Skew, UpSta & Num, DnSta & Num=  ,1667.18, 3 ,1665.93, 3 , 0 , 0 , 0 ,,
     1.1       1       1
 476.538 480.394   515.7
     1.1       1       1
 476.538 480.394   515.7
Pier Skew, UpSta & Num, DnSta & Num=  ,1688.01, 2 ,1686.76, 2 , 0 , 0 , 0 ,,
       1       1
 503.234   515.7
       1       1
 503.234   515.7
Pier Skew, UpSta & Num, DnSta & Num=  ,1708.86, 2 ,1708.61, 2 , 0 , 0 , 0 ,,
       1       1
 475.356   515.7
       1       1
 475.356   515.7
Pier Skew, UpSta & Num, DnSta & Num=  ,1729.73, 2 ,1729.48, 2 , 0 , 0 , 0 ,,
       1       1
 472.909   515.7
       1       1
 472.909   515.7
Pier Skew, UpSta & Num, DnSta & Num=  ,1750.44, 2 ,1750.19, 2 , 0 , 0 , 0 ,,
       1       1
 471.547   515.7
       1       1
 471.547   515.7
Pier Skew, UpSta & Num, DnSta & Num=  ,1772.19, 2 ,1771.94, 2 , 0 , 0 , 0 ,,
       9       6
 466.924   515.7
       9       6
 466.924   515.7
Pier Skew, UpSta & Num, DnSta & Num=  ,1933.47, 4 ,1933.47, 4 , 0 , 0 , 0 ,,
      23      23       6       6
     471 510.292   510.3  514.44
      23      23       6       6
     471 510.292   510.3  514.44
Pier Skew, UpSta & Num, DnSta & Num=  ,2072.88, 2 ,2072.62, 2 , 0 , 0 , 0 ,,
    7.28       6
  478.18   515.7
    7.28       6
  478.18   515.7
Pier Skew, UpSta & Num, DnSta & Num=  ,2094.6, 2 ,2093.35, 2 , 0 , 0 , 0 ,,
       1       1
 487.429   515.7
       1       1
 487.429   515.7
Pier Skew, UpSta & Num, DnSta & Num=  ,2115.6, 2 ,2114.35, 2 , 0 , 0 , 0 ,,
       1       1
 494.353   515.7
       1       1
 494.353   515.7
Pier Skew, UpSta & Num, DnSta & Num=  ,2136.5, 2 ,2135.25, 2 , 0 , 0 , 0 ,,
       1       1
 506.728   515.7
       1       1
 506.728   515.7
Pier Skew, UpSta & Num, DnSta & Num=  ,2157.48, 2 ,2156.23, 2 , 0 , 0 , 0 ,,
       1       1
 510.133   515.7
       1       1
 510.133   515.7
BR Coef=-1 , 1 , 0 ,, 0 ,,,0.8,0,1.2,0,
WSPro=,,,, 1 ,,,, 0 ,,,, 0 ,,,,-1 ,-1 ,-1 , 0 , 0 , 0 , 0 , 0
BC Design=,, 0 ,, 0 ,,,,,,
BC HTab HWMax=583
BC Use User HTab Curves=0
BC User HTab FreeFlow(D)= 0

Type RM Length L Ch R = 1 ,111026.6,261,197.6,160.4
XS GIS Cut Line= 5
      2024684.06       656895.032025998.14496822656928.641478486
2027056.12181086656976.821813289 2027420.6926173  656994.4922825
2027797.23369743656488.262350921
#Sta/Elev= 30
       0  581.86      75  587.52   140.1   585.4   377.6  554.21   505.1  529.09
   657.7  527.91   705.1  532.77   817.8  520.26   890.3  525.06   950.3  520.65
  1050.4  529.41  1325.4  520.78  1498.1  507.74  1675.8  504.43  1735.8  484.51
  1780.4   479.7 1881.28     468  1985.6  463.44  2171.3  480.39  2298.4  489.76
  2738.6  493.08    2819  502.71    2859  521.62  2892.2  522.42  2946.2  554.86
  3011.7  551.92  3039.7  570.15    3155  615.63  3304.5  661.29  3369.5  674.82
#Mann= 3 , 0 , 0
       0      .2       0  1780.4     .06       0  2171.3      .2       0
#XS Ineff= 2 , 0
         1505.12  519.68 2223.77          519.68
Permanent Ineff=
       F       F
Bank Sta=1780.4,2171.3
XS Rating Curve= 0 ,0
Exp/Cntr=0.5,0.3

Type RM Length L Ch R = 1 ,110829.0,224.1,455.8,540.2
XS GIS Cut Line= 6
2024775.52426079656929.3482024262026367.33852455657212.627352826
2028149.36530751657066.4322412192028944.83530157656568.400910045
2030794.36885228653196.4815963682039997.70526163648748.186999514
#Sta/Elev= 30
       0  585.24 1673.78  479.66  1901.1  464.91 2260.46  479.66  3817.2  522.48
  4431.3  667.02  5208.6  706.95  6073.7  863.27  6678.2  815.57  7074.6  929.78
  8044.3  649.57  8507.3  785.68  8962.9  683.87  9227.7  768.62  9497.7  736.25
 10028.9  948.84 10878.6  639.12 11753.2  565.28 11925.4  654.09 12301.2  573.34
 14357.8  640.19 15410.1 1004.53 15779.4  997.34   16121  898.31 16431.7  989.75
 16914.3  989.84 17234.4  879.16 17473.2  962.22 17706.5  910.97   18413 1006.91
#Mann= 3 , 0 , 0
       0      .1       0 1673.78     .04       0 2260.46      .1       0
#XS Ineff= 1 ,-1
 2307.69  4519.9  519.68
Permanent Ineff=
       F
Bank Sta=1673.78,2260.46
XS Rating Curve= 0 ,0
Exp/Cntr(USF)=0,0
Exp/Cntr=0.5,0.3

Type RM Length L Ch R = 1 ,110373.3,280.8,270.7,271.5
XS GIS Cut Line= 6
2024362.88105669656605.980220516 2024578.5759134656953.069929864
2027996.32065351657859.7087741232028488.57689032658393.434555037
2031218.43062933660172.6500002232041058.70059211661893.351843632
#Sta/Elev= 30
       0  589.67  2730.1486.9498  2856.5  462.81  2971.6486.3088  3129.5  515.74
    3771  484.74  4366.7  533.29    4697  602.98  5370.9  525.59  5961.6  644.47
  6563.1   609.5  7163.3   734.6  7593.6  719.88  7935.2  799.77  8442.8   676.5
  8871.7  713.62  9338.7  639.59 10046.8  794.16 10884.3  590.22 11719.3  732.44
 12396.9  641.94 12924.8  779.06 13914.6  807.28 14594.8  635.16 14993.2  740.47
 15488.1  628.19 16292.6  783.62   16818  727.03 17531.1  581.62 17921.6  617.12
#Mann= 3 , 0 , 0
       0      .1       0  2730.1    .035       0  2971.6      .1       0
#XS Ineff= 2 ,-1
       0 2581.86  514.52 3089.28  4796.9  521.95
Permanent Ineff=
       F       F
Bank Sta=2730.1,2971.6
XS Rating Curve= 0 ,0
Exp/Cntr=0.5,0.3

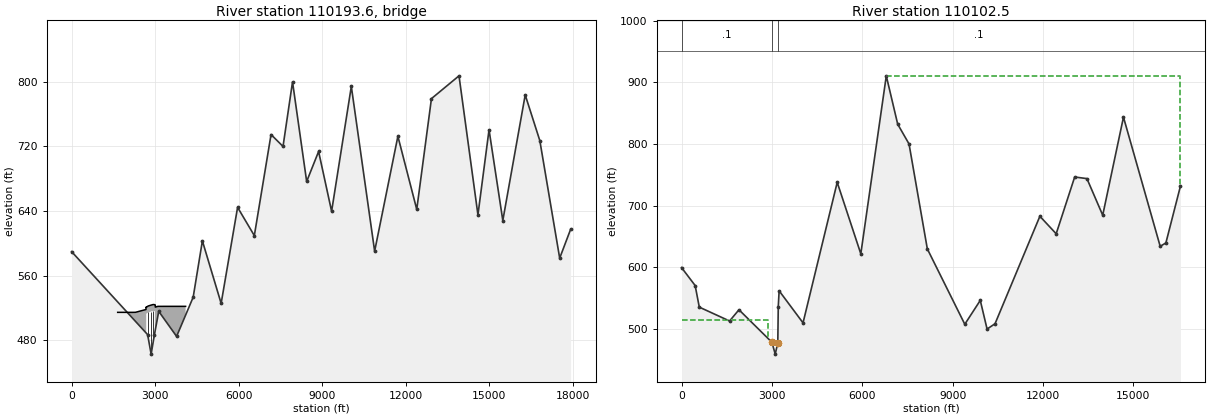
Type RM Length L Ch R = 3 ,110193.6,,,
BEGIN DESCRIPTION:
I 40 Bridge
2019 Update:
-Included Momentum and Yarnell Low Flow methods
-Increased deck width to include both bridges
END DESCRIPTION:
Bridge Culvert--1,0,-1,-1, 0
Deck Dist Width WeirC Skew NumUp NumDn MinLoCord MaxHiCord MaxSubmerge Is_Ogee
77,112,2.61,0, 19, 16, , , 0.95, 0, 0,0,,
    1655    2195    2295 2670.41 2670.42 2672.99 2679.36 2679.86 2682.16 2683.66
 2748.59 2837.82 2928.23 2991.28 3005.79  3005.8 3099.67    3530    4095
  514.52  514.52  514.58  518.04  520.08  520.63  520.79  521.03  521.22  520.82
  522.35  523.31   524.2  523.99  523.42  521.02  521.94  521.95  521.95
                                                          514.03  513.22  512.82
  514.35  515.31   516.2  515.99
    2153    2453 2878.41 2878.42 2880.99 2887.36 2888.16 2894.38  2894.7 2956.59
 3045.82 3136.23 3199.28 3213.79  3213.8 3307.67
  514.52  514.58  518.04  520.08  520.63  520.79  521.03  521.25  520.14  522.35
  523.31   524.2  523.99  523.42  521.02  521.94
                                                  514.07  513.25  512.14  514.35
  515.31   516.2  515.99
Pier Skew, UpSta & Num, DnSta & Num=  ,2751, 4 ,2956.59, 4 , 3 , 3 , 0 ,,
       3       3       4       4
  488.34  509.34  509.35  514.35
       3       3       4       4
  488.34  509.34  509.35  514.35
Pier Skew, UpSta & Num, DnSta & Num=  ,2846, 4 ,3045.82, 4 , 3 , 3 , 0 ,,
       3       3       4       4
  463.35   510.3  510.31  515.31
       3       3       4       4
  463.35   510.3  510.31  515.31
Pier Skew, UpSta & Num, DnSta & Num=  ,2937, 4 ,3136.23, 4 , 3 , 3 , 0 ,,
       3       3       4       4
  469.17  511.19   511.2   516.2
       3       3       4       4
  469.17  511.19   511.2   516.2
Abutment Skew #Up #Dn= , 10 , 10
 2679.86 2680.93 2689.62 2690.62 2690.73 2734.81 2735.44 2736.07  2747.3 2767.03
  514.03  511.96  507.85  507.85  500.03  500.38  502.04  492.73  488.34  472.39
 2888.16 2888.94 2897.62 2898.62 2898.73 2942.81 2943.44 2944.07  2955.3 2975.03
  514.07  511.97  507.85  507.85  500.03  500.38  502.04  492.73  488.34  472.39
Abutment Skew #Up #Dn= , 4 , 4
 2950.47 2963.06 2978.22 2991.28
  474.92  496.32  509.45  515.99
 2275.47 2288.06 2303.22 2316.28
  474.92  496.32  509.45  515.99
BR Coef=-1 , 1 , 1 ,0.9, 0 ,,,0.8,0,1.33,0,
WSPro=,,,, 1 ,,,, 0 ,,,, 0 ,,,,-1 ,-1 ,-1 , 0 , 0 , 0 , 0 , 0
BC Design=,, 0 ,, 0 ,,,,,,
BC HTab HWMax=583
BC Use User HTab Curves=0
BC User HTab FreeFlow(D)= 0

Type RM Length L Ch R = 1 ,110102.5,1149.6,1522,1675.7
BEGIN DESCRIPTION:
34093.24
END DESCRIPTION:
XS GIS Cut Line= 6
      2024255.09       656532.492024679.86849911657294.979870142
2027789.74523101658123.2808252562028032.31847907658928.358209604
 2029796.1052498660748.6279537242031249.04553652669728.081202811
#Sta/Elev= 30
       0  599.56   452.6  570.36     590   535.3  1595.5  512.78    1907  531.03
    3001  478.24  3110.9  459.02  3196.1  477.47  3211.7  535.94  3240.4  561.83
  4033.8  509.76  5168.6  737.87  5951.9  621.84  6797.8  910.62  7176.8  832.21
  7552.5  800.18  8160.3   629.8  9403.8   507.5  9917.9  546.26 10143.3  499.75
 10407.5  508.32 11896.3  682.77 12437.8  654.39 13051.6  746.52 13458.4  743.91
 13982.4   684.5 14671.4  843.62 15890.5  633.98 16079.4  639.52 16563.4   731.9
#Mann= 3 , 0 , 0
       0      .1       0    3001    .035       0  3196.1      .1       0
#XS Ineff= 2 , 0
         2854.66  514.55 6801.07          910.73
Permanent Ineff=
       F       F
Bank Sta=3001,3196.1
XS Rating Curve= 0 ,0
Exp/Cntr=0.5,0.3