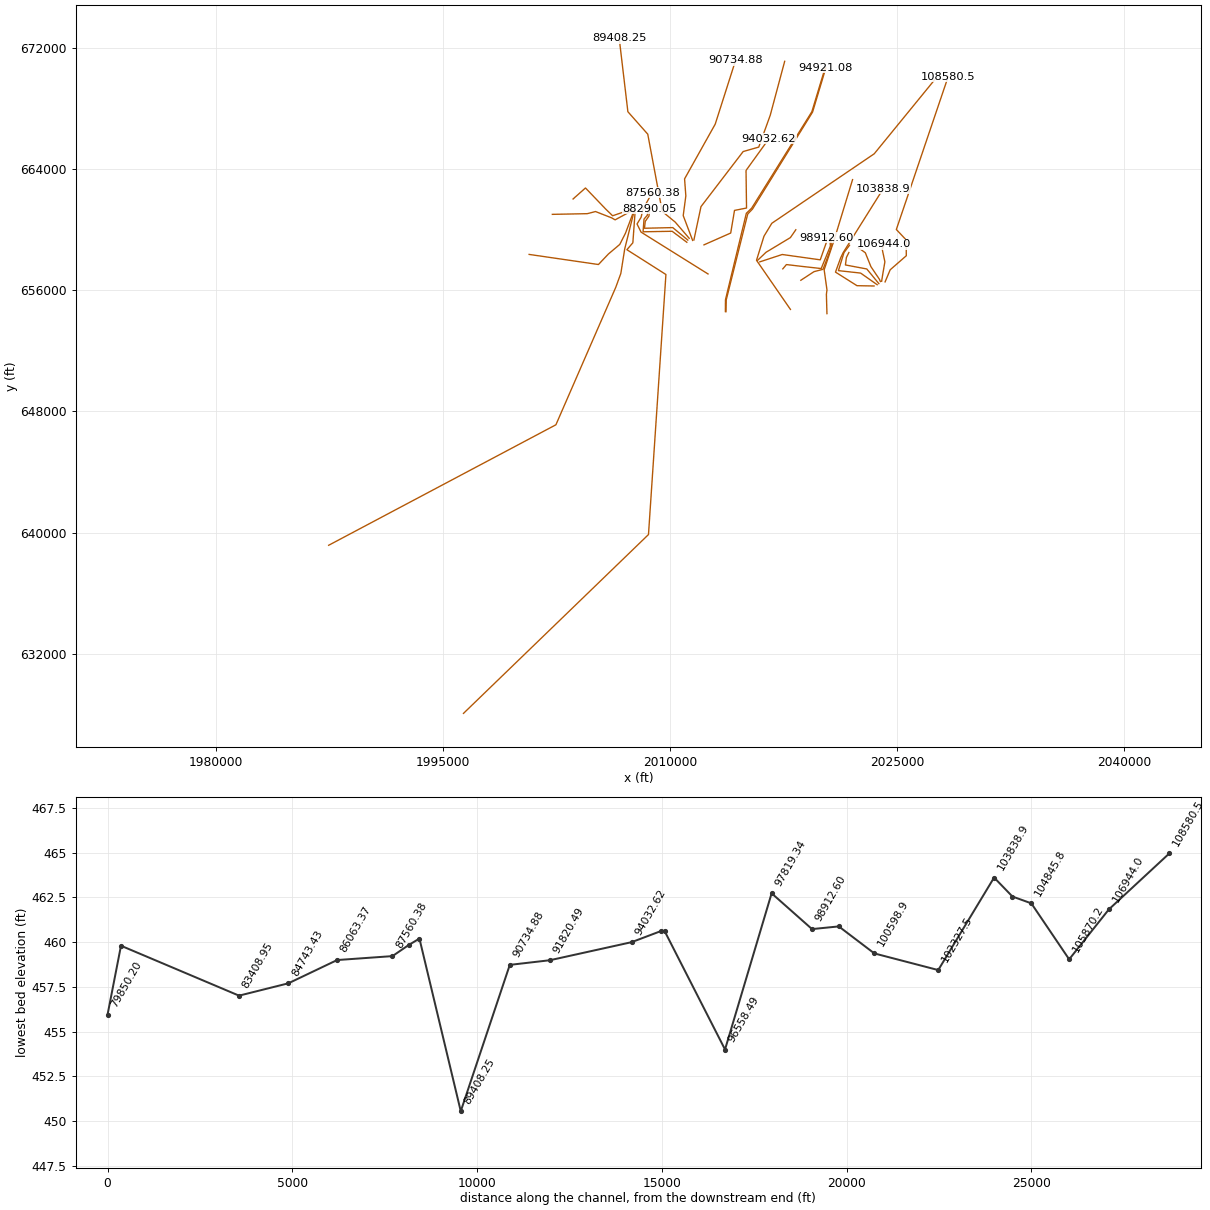
HEC-RAS study CaneyFork.prj: Caney Fork River- Smith County

--- CaneyFork.g02 (geometry) --- (continued)

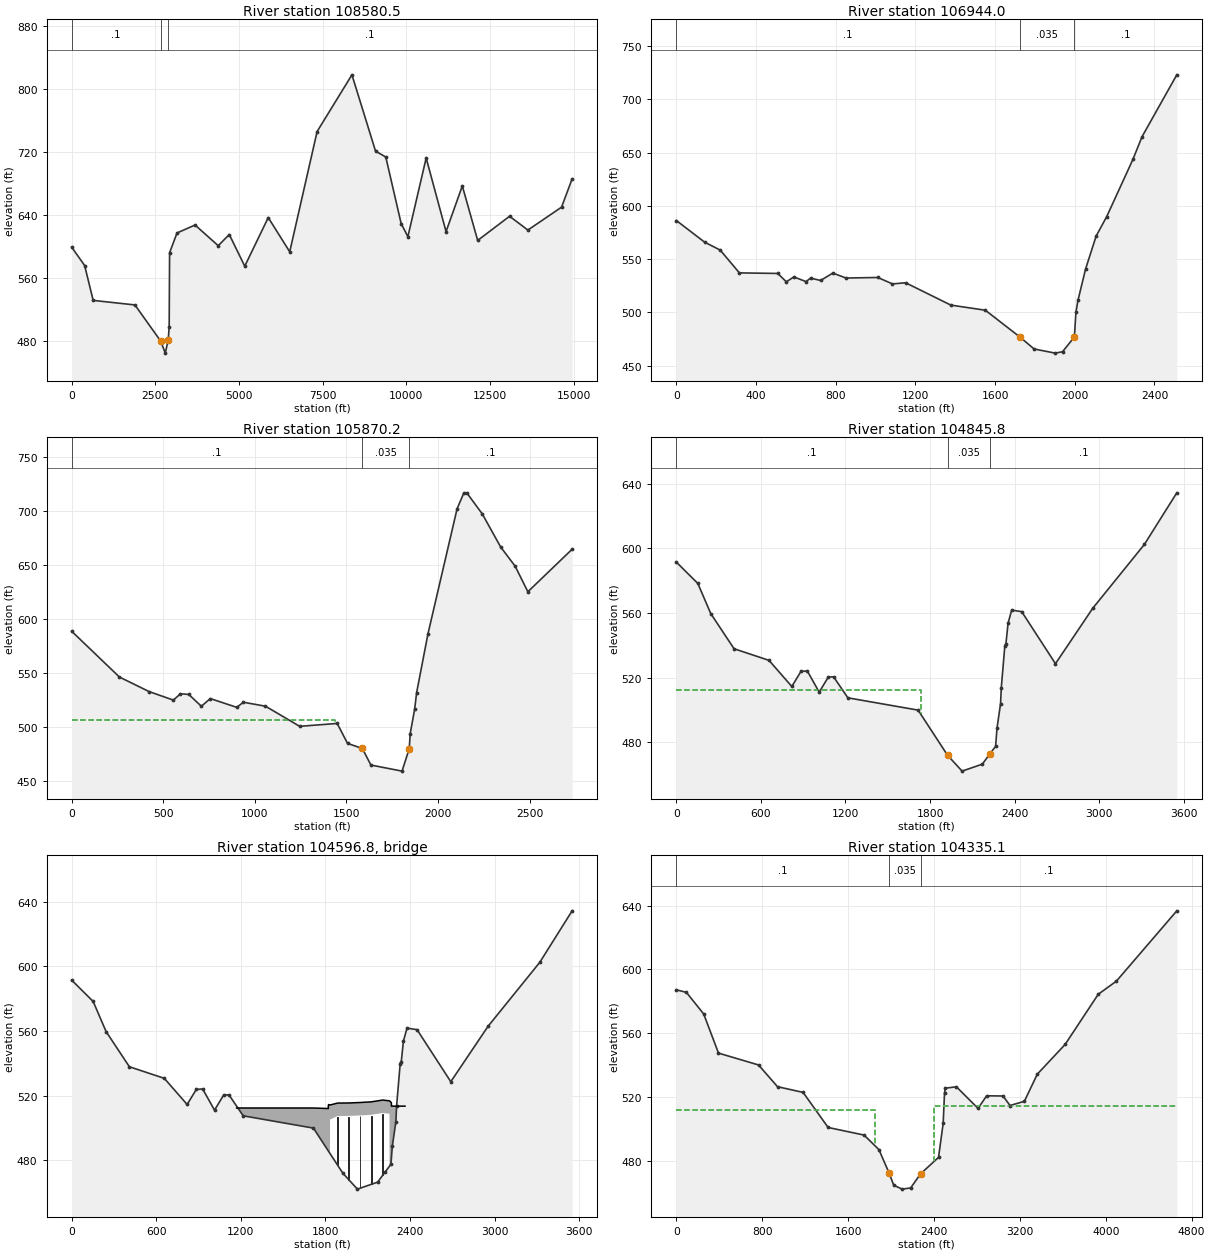
Type RM Length L Ch R = 1 ,108580.5,1575.1,1636.5,1668.7
BEGIN DESCRIPTION:
33700.5
END DESCRIPTION:
XS GIS Cut Line= 6
      2024198.14       656543.77      2024534.58       657343.05
      2025599.21       658272.55      2025590.41       659316.01
      2024941.04       660002.582028364.52899077670097.130292742
#Sta/Elev= 30
       0   599.2   386.9  575.96   641.9  531.76  1888.9  526.01  2656.3  480.35
 2796.14  464.96  2883.6481.7085  2912.2  498.01  2924.7  592.23  3146.6  617.19
    3685  627.26  4377.4  601.09  4707.4  615.22  5169.8  575.11  5871.7  636.67
    6513  593.34  7331.4  745.69  8371.5  817.53  9076.4  720.89  9382.6   713.4
  9841.5  629.17 10042.5   612.5   10589  712.12   11183  618.92 11668.7   676.8
   12128  607.73 13080.7  638.36 13627.5  620.88 14633.3  649.87 14949.2  685.73
#Mann= 3 , 0 , 0
       0      .1       0  2656.3    .035       0  2883.6      .1       0
Bank Sta=2656.3,2883.6
XS Rating Curve= 0 ,0
Exp/Cntr=0.3,0.1

Type RM Length L Ch R = 1 ,106944.0,1035.1,1073.8,1099.2
BEGIN DESCRIPTION:
33193.16
END DESCRIPTION:
XS GIS Cut Line= 6
      2023970.23       656585.37      2024044.55       657053.86
2024185.40904335657866.104276543      2024029.29       658606.51
      2024014.74       658710.85      2024143.15       659037.77
#Sta/Elev= 30
       0  586.25   141.8  565.96   220.2  558.49   316.4  537.12   508.9  536.59
     552  528.75   589.8  533.31     651  528.95   673.8  532.22   723.9     530
   785.4  536.93   851.4   532.3  1011.3   532.8  1084.8  526.77  1150.8  527.84
  1377.9  506.89  1550.9  502.09  1724.7  476.92 1795.63  465.73 1901.53  461.83
 1938.53  463.13    1998  477.02  2005.7  500.23  2015.9  511.33  2054.2   540.8
  2107.3  571.73  2160.3  589.97  2291.9  643.65  2337.3  664.83    2512  722.96
#Mann= 3 , 0 , 0
       0      .1       0  1724.7    .035       0    1998      .1       0
Bank Sta=1724.7,1998
XS Rating Curve= 0 ,0
Exp/Cntr=0.3,0.1

Type RM Length L Ch R = 1 ,105870.2,792.5,1024.4,1190
BEGIN DESCRIPTION:
32844.26
END DESCRIPTION:
XS GIS Cut Line= 5
      2023887.97       656568.39      2023837.67       656696.51
      2023262.99       657551.612022893.59298757658469.294965758
      2022426.73        658805.4
#Sta/Elev= 30
       0  588.77   260.6  546.31   422.2  532.86     555  524.91   594.1  530.79
   639.3  530.16   708.1   519.2   756.8  526.34   901.4  518.19   937.5  522.94
  1058.2  519.24  1244.9  500.59  1449.6  503.27  1506.1  484.76  1586.9  480.04
  1633.7  464.69  1803.7  459.04    1843  479.82  1848.4  493.83  1872.7  516.65
  1883.4  531.86  1945.4  586.49  2104.4  702.43  2140.3  716.68  2157.2  717.17
  2241.8  697.62  2342.1  666.95  2421.5  649.08  2490.7  625.41  2732.4  664.85
#Mann= 3 , 0 , 0
       0      .1       0  1586.9    .035       0    1843      .1       0
#XS Ineff= 2 , 0
         1436.34  506.71
Permanent Ineff=
       F       F
Bank Sta=1586.9,1843
XS Rating Curve= 0 ,0
Exp/Cntr=0.5,0.3

Type RM Length L Ch R = 1 ,104845.8,461.1,510.7,611.3
BEGIN DESCRIPTION:
32600.02
END DESCRIPTION:
XS GIS Cut Line= 5
      2023786.65       656430.26       2022990.5       657398.15
      2021581.39       657662.74      2021643.73       658151.81
      2021808.64       658483.53
#Sta/Elev= 30
       0  591.39   152.3  578.21   244.1  559.58   409.4  537.83     657  530.67
   819.1  514.51   883.9  523.79   928.9  524.12  1013.4  511.02  1078.1  520.32
  1115.6  520.48  1216.8  507.49  1715.1  499.89 1923.95     472  2027.2  462.17
 2170.71  466.48 2223.86   472.8  2265.1  477.52  2274.7  488.59  2300.2  503.94
  2305.3  513.73  2330.7  539.83  2338.3  540.97  2353.6  553.68    2379  561.73
  2450.3  560.76  2689.7   528.6  2954.3  562.88  3320.5  602.33  3550.5  634.24
#Mann= 3 , 0 , 0
       0      .1       0 1923.95    .035       0 2223.86      .1       0
#XS Ineff= 2 , 0
         1732.82  512.33
Permanent Ineff=
       F       F
Bank Sta=1923.95,2223.86
XS Rating Curve= 0 ,0
Exp/Cntr=0.5,0.3

Type RM Length L Ch R = 3 ,104596.8,,,
BEGIN DESCRIPTION:
I 40 Bridge # 2
2019 Update:
- Increased deck width to include both bridges
END DESCRIPTION:
Bridge Culvert--1,0,-1,-1, 0
Deck Dist Width WeirC Skew NumUp NumDn MinLoCord MaxHiCord MaxSubmerge Is_Ogee
96.62,260,2.61,0, 19, 17, , , 0.95, 0, 0,0,,
    1170    1235    1715 1820.72  1820.8 1820.81 1823.46 1832.82 1886.84 1965.08
 2046.53 2126.61 2206.37 2254.93 2265.63 2268.21 2268.22 2268.37    2365
  512.33  512.33  512.33  511.99  511.99  514.05  514.46  514.18  515.38  515.44
  515.72  516.15  517.24  516.75  515.89  515.47  513.48  513.48  513.48
                                                          505.18  507.38  507.44
  507.72  508.15  509.24  508.75
    1262    1742 1847.72 1898.71 1898.72 1901.23 1912.97 1952.34  2032.1 2110.69
 2190.96  2269.9 2324.36 2326.67 2335.74 2335.75 2571.81
  512.33  512.33  511.99  511.99  514.53  514.92  515.75  515.83  515.44  515.72
  516.15  517.24  516.75  516.28  517.32  514.74  514.74
                                                  507.45  507.83  507.44  507.72
  508.15  509.24  509.31  509.31  509.32
Pier Skew, UpSta & Num, DnSta & Num=  ,1886.84, 4 ,1952.34, 4 , 3 , 3 , 0 ,,
       3       3       4       4
  483.83  501.87  501.88  506.88
       3       3       4       4
  483.83  502.32  502.33  507.33
Pier Skew, UpSta & Num, DnSta & Num=  ,1965.08, 4 ,2032.1, 4 , 3 , 3 , 0 ,,
       3       3       4       4
  467.78  501.93  501.94  506.94
       3       3       4       4
  467.78  501.93  501.94  506.94
Pier Skew, UpSta & Num, DnSta & Num=  ,2046.53, 4 ,2110.69, 4 , 3 , 3 , 0 ,,
       3       3       4       4
  466.21  502.21  502.22  507.22
       3       3       4       4
  466.21  502.21  502.22  507.22
Pier Skew, UpSta & Num, DnSta & Num=  ,2126.61, 4 ,2190.96, 4 , 3 , 3 , 0 ,,
       3       3       4       4
     468  502.64  502.65  507.65
       3       3       4       4
     468  502.64  502.65  507.65
Pier Skew, UpSta & Num, DnSta & Num=  ,2206.37, 4 ,2269.9, 4 , 3 , 3 , 0 ,,
       3       3       4       4
   475.8  503.73  503.74  508.74
       3       3       4       4
   475.8  503.73  503.74  508.74
BR Coef=-1 , 1 , 0 ,, 0 ,,,0.8,0,1.33,0,
WSPro=,,,, 1 ,,,, 0 ,,,, 0 ,,,,-1 ,-1 ,-1 , 0 , 0 , 0 , 0 , 0
BC Design=,, 0 ,, 0 ,,,,,,
BC HTab HWMax=583
BC Use User HTab Curves=0
BC User HTab FreeFlow(D)= 0

Type RM Length L Ch R = 1 ,104335.1,644.1,496.1,402.4
BEGIN DESCRIPTION:
32472.85
END DESCRIPTION:
XS GIS Cut Line= 5
      2023675.33       656360.072022582.86140526657126.744215781
 2021118.2923421657288.360305242      2021486.93       658483.07
      2021851.36       658963.83
#Sta/Elev= 30
       0  587.25    93.2  585.68     255  572.11   392.5  547.65   765.7  540.24
   942.2  526.64  1180.5  523.08  1413.9  501.12  1748.4  496.38  1886.8  487.28
 1982.68  472.48 2024.65  465.01  2102.8  462.55 2182.51  463.29  2274.6   472.1
  2442.3  482.43  2485.4  503.66    2498  522.71  2505.7   525.7  2608.6  526.59
  2810.2  513.07  2890.3  520.94  3043.1  520.82  3108.2  514.87  3241.9   517.5
  3362.4  534.49  3621.3  553.07    3930  584.47  4098.9  592.67  4661.7  636.68
#Mann= 3 , 0 , 0
       0      .1       0 1982.68    .035       0  2274.6      .1       0
#XS Ineff= 2 , 0
         1852.97  512.33 2395.74          514.74
Permanent Ineff=
       F       F
Bank Sta=1982.68,2274.6
XS Rating Curve= 0 ,0
Exp/Cntr=0.5,0.3

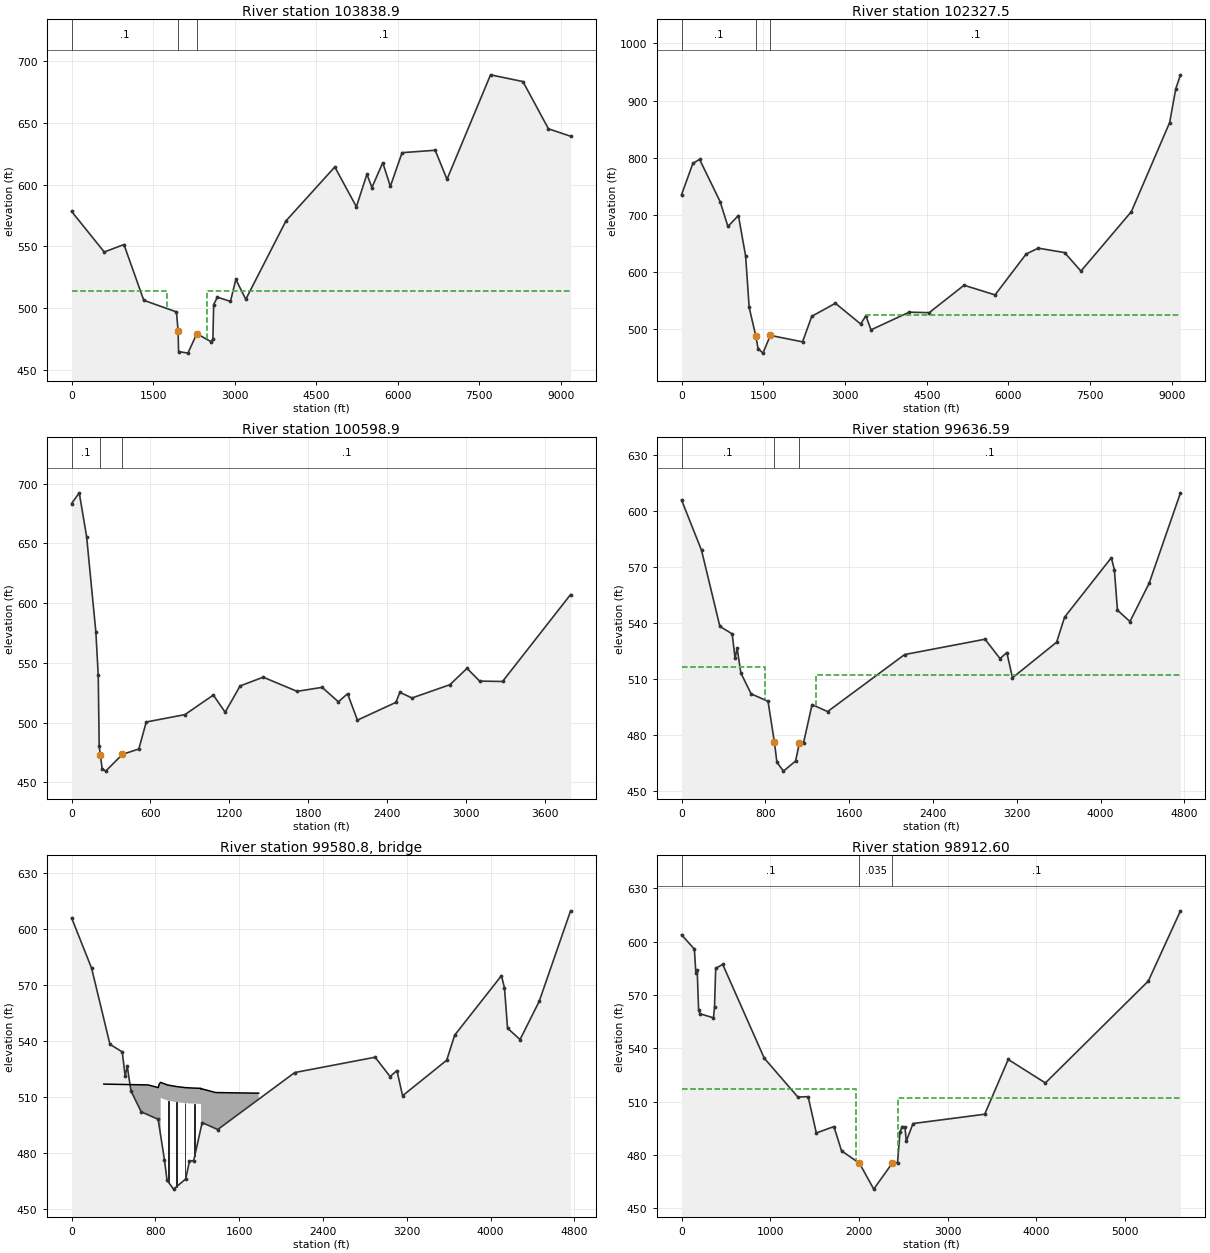
Type RM Length L Ch R = 1 ,103838.9,1720.6,1511.5,937.1
BEGIN DESCRIPTION:
32275.52
END DESCRIPTION:
XS GIS Cut Line= 6
      2023471.41       656274.56      2022343.03       656294.93
      2020925.23       657190.15      2021263.32       658124.46
      2021428.61       658471.95      2024081.77        662705.9
#Sta/Elev= 30
       0  578.37   600.5  545.51   963.2  551.55  1327.8  506.41  1929.2     497
  1959.4  481.78 1968.47   464.9 2140.32  463.61 2303.89  479.32 2573.02  472.73
 2600.24  475.36  2614.5  502.99  2683.3  508.94  2923.4  505.51  3022.4  523.31
  3205.5  507.21  3943.2  570.61  4843.7  614.39  5240.9  582.16  5435.1  608.52
  5526.6  597.75  5726.5  617.84  5865.9  598.66  6081.3  625.95  6691.7  627.93
  6908.2  604.39  7709.8  689.01  8305.8  683.56  8775.8  645.29  9182.6  639.28
#Mann= 3 , 0 , 0
       0      .1       0  1959.4    .035       0 2303.89      .1       0
#XS Ineff= 2 , 0
         1759.69  514.32 2493.37          514.02
Permanent Ineff=
       F       F
Bank Sta=1959.4,2303.89
XS Rating Curve= 0 ,0
Exp/Cntr=0.3,0.1

Type RM Length L Ch R = 1 ,102327.5,1847.7,1728.6,1282.8
BEGIN DESCRIPTION:
31773.59
END DESCRIPTION:
XS GIS Cut Line= 6
      2020361.14       654449.14      2020323.83       655733.21
2020362.96200761656012.174994587      2020176.42       657342.53
      2020840.39       659323.98      2022051.49       663295.01
#Sta/Elev= 30
       0  735.38   208.8   790.2   331.4  797.17     709  723.22   851.6  679.84
  1044.2  699.03  1176.7  628.13  1241.8  538.23 1362.14  488.98 1404.99  466.37
 1494.78  458.44  1630.4  489.45  2221.4  478.16  2390.8  522.82  2824.3  545.58
  3288.3  509.38  3383.3  523.63  3478.2  499.12  4176.9  530.03    4546   529.2
  5185.1  577.12  5754.9  560.27  6324.7  631.66  6546.9  641.96  7030.4  634.21
  7331.3  601.89  8256.6  705.81  8959.3  861.62  9071.7  920.75  9157.6  944.98
#Mann= 3 , 0 , 0
       0      .1       0 1362.14    .035       0  1630.4      .1       0
#XS Ineff= 2 , 0
                         3381.96          524.39
Permanent Ineff=
       F       F
Bank Sta=1362.14,1630.4
XS Rating Curve= 0 ,0
Exp/Cntr=0.3,0.1

Type RM Length L Ch R = 1 ,100598.9,1208.5,962.3,830.8
BEGIN DESCRIPTION:
31249.02
END DESCRIPTION:
XS GIS Cut Line= 6
      2018636.99       656651.99       2019504.2       657219.59
      2020096.21       657373.28      2020281.67       657843.71
      2020646.14       658833.31      2020634.83       659420.37
#Sta/Elev= 30
       0  683.32    58.1  692.29   114.1  655.66   184.5  575.77   202.5  539.56
   209.8  480.25  217.94  473.23  232.61  461.37  259.01  459.37  386.29  473.36
   511.4  477.93   567.7  500.49   861.8  506.66    1078  523.04    1168  508.68
  1281.7  530.66  1457.3     538  1714.8  526.15  1905.6  529.48  2029.2   517.4
  2099.1  524.16  2174.2  502.05  2467.2  516.93  2496.5  525.27  2589.8  520.62
  2877.5   531.7  3007.8  545.37    3104  534.72  3277.9  534.39  3795.5  607.15
#Mann= 3 , 0 , 0
       0      .1       0  217.94    .035       0  386.29      .1       0
Bank Sta=217.94,386.29
XS Rating Curve= 0 ,0
Exp/Cntr=0.5,0.3

Type RM Length L Ch R = 1 ,99636.59,965.4,724,725.8
BEGIN DESCRIPTION:
30943.32
END DESCRIPTION:
XS GIS Cut Line= 6
      2017446.46       657404.072017684.68895907657688.164684201
      2018733.66657565.5572865342019980.29416373657425.658847935
      2020587.83       658906.83      2020558.05       659386.43
#Sta/Elev= 30
       0   605.8   190.9  578.92   365.9  538.26   483.4  534.22   511.1  521.29
   531.2  526.52   566.4  513.34   664.6  502.17   825.8  498.19   886.5  476.42
  910.84  465.58973.3101  460.88 1088.69  466.27    1125  475.84  1165.5  476.16
  1246.1  496.43  1394.6  492.71  2129.9  523.18  2897.2  531.37  3040.4  521.03
  3105.3  524.25  3159.3  510.78  3580.8  529.78  3656.5  543.15  4103.2  574.95
  4132.1  568.37  4161.4  546.87  4280.7  540.82  4463.7  561.28  4762.8   609.6
#Mann= 3 , 0 , 0
       0      .1       0   886.5    .035       0    1125      .1       0
#XS Ineff= 2 , 0
             800  516.74    1285          512.15
Permanent Ineff=
       F       F
Bank Sta=886.5,1125
XS Rating Curve= 0 ,0
Exp/Cntr=0.5,0.3

Type RM Length L Ch R = 3 ,99580.8 ,,,
BEGIN DESCRIPTION:
I 40 Bridge #3
2019 Update:
-Included Momentum low flow modeling approach
-Increased deck width to include both directions of bridge
END DESCRIPTION:
Bridge Culvert--1,0,-1,-1, 0
Deck Dist Width WeirC Skew NumUp NumDn MinLoCord MaxHiCord MaxSubmerge Is_Ogee
50.54,575,2.61,0, 14, 15, , , 0.95, 0, 0,0,,
  307.69     731  826.64  836.65  850.12  915.17  997.41 1082.22 1165.37 1235.05
 1235.06 1249.21 1375.29 1785.29
     517  516.56  515.14  517.08  517.93  516.53  515.73  515.13  514.88  514.74
  514.29  514.37  512.49  512.15
                                  509.63  508.23  507.42  506.83  506.58  506.44
                                
    1210    1920 2012.56 2012.57 2014.78 2082.08 2163.66 2243.87 2325.43 2392.86
 2397.23 2397.24 2564.29    3110    3520
     517  516.56  516.06  518.28   518.6  517.36  516.53  515.93  515.54  515.56
  515.14  513.08  512.49  512.15  512.15
                                   510.3  509.06  508.23  507.62  507.24  507.26
                                        
Pier Skew, UpSta & Num, DnSta & Num=  ,925, 2 ,2090, 2 , 0 , 0 , 0 ,,
    6.84    6.84
  473.09  508.23
    6.84    6.84
  473.09  509.06
Pier Skew, UpSta & Num, DnSta & Num=  ,1001, 2 ,2165, 2 , 0 , 0 , 0 ,,
    6.84    6.84
  462.82  507.42
    6.84    6.84
  462.82  508.23
Pier Skew, UpSta & Num, DnSta & Num=  ,1081, 2 ,2240, 2 , 0 , 0 , 0 ,,
    6.84    6.84
  476.81     508
    6.84    6.84
  476.81     508
Pier Skew, UpSta & Num, DnSta & Num=  ,1176, 2 ,2340, 2 , 0 , 0 , 0 ,,
    6.84    6.84
  467.92  506.83
    6.84    6.84
  467.92  507.62
BR Coef=-1 , 1 , 0 ,, 0 ,,,0.8,0,1.33,0,
WSPro=,,,, 1 ,,,, 0 ,,,, 0 ,,,,-1 ,-1 ,-1 , 0 , 0 , 0 , 0 , 0
BC Design=,, 0 ,, 0 ,,,,,,
BC HTab HWMax=600
BC Use User HTab Curves=0
BC User HTab FreeFlow(D)= 0

Type RM Length L Ch R = 1 ,98912.60,650,1093.3,1215.4
BEGIN DESCRIPTION:
30763.88
END DESCRIPTION:
XS GIS Cut Line= 5
      2015930.71       657868.272017410.25802927658353.366467865
      2019917.91658000.978029265      2020319.34       659138.82
      2020329.64       659465.22
#Sta/Elev= 30
       0  603.88     145  595.79   161.4  582.32   176.7  583.92   192.6  561.57
   207.4  559.42   359.8  557.13   371.9  563.13     385  584.98   464.2  587.18
   932.3  534.42  1311.1  512.56  1426.9  512.76    1519  492.33  1717.4  495.93
  1803.2  482.27  2005.2  475.28 2166.16  460.73  2373.8  475.28  2434.4  475.63
  2462.2  492.99  2487.4  495.94  2517.7  495.74  2532.8  487.72  2608.6  497.63
  3416.4  502.88  3681.5  533.69  4100.3  520.48  5260.5  577.84  5622.5  617.33
#Mann= 3 , 0 , 0
       0      .1       0  2005.2    .035       0  2373.8      .1       0
#XS Ineff= 2 , 0
         1965.78  516.95 2441.86          512.15
Permanent Ineff=
       F       F
Bank Sta=2005.2,2373.8
XS Rating Curve= 0 ,0
Exp/Cntr=0.5,0.3

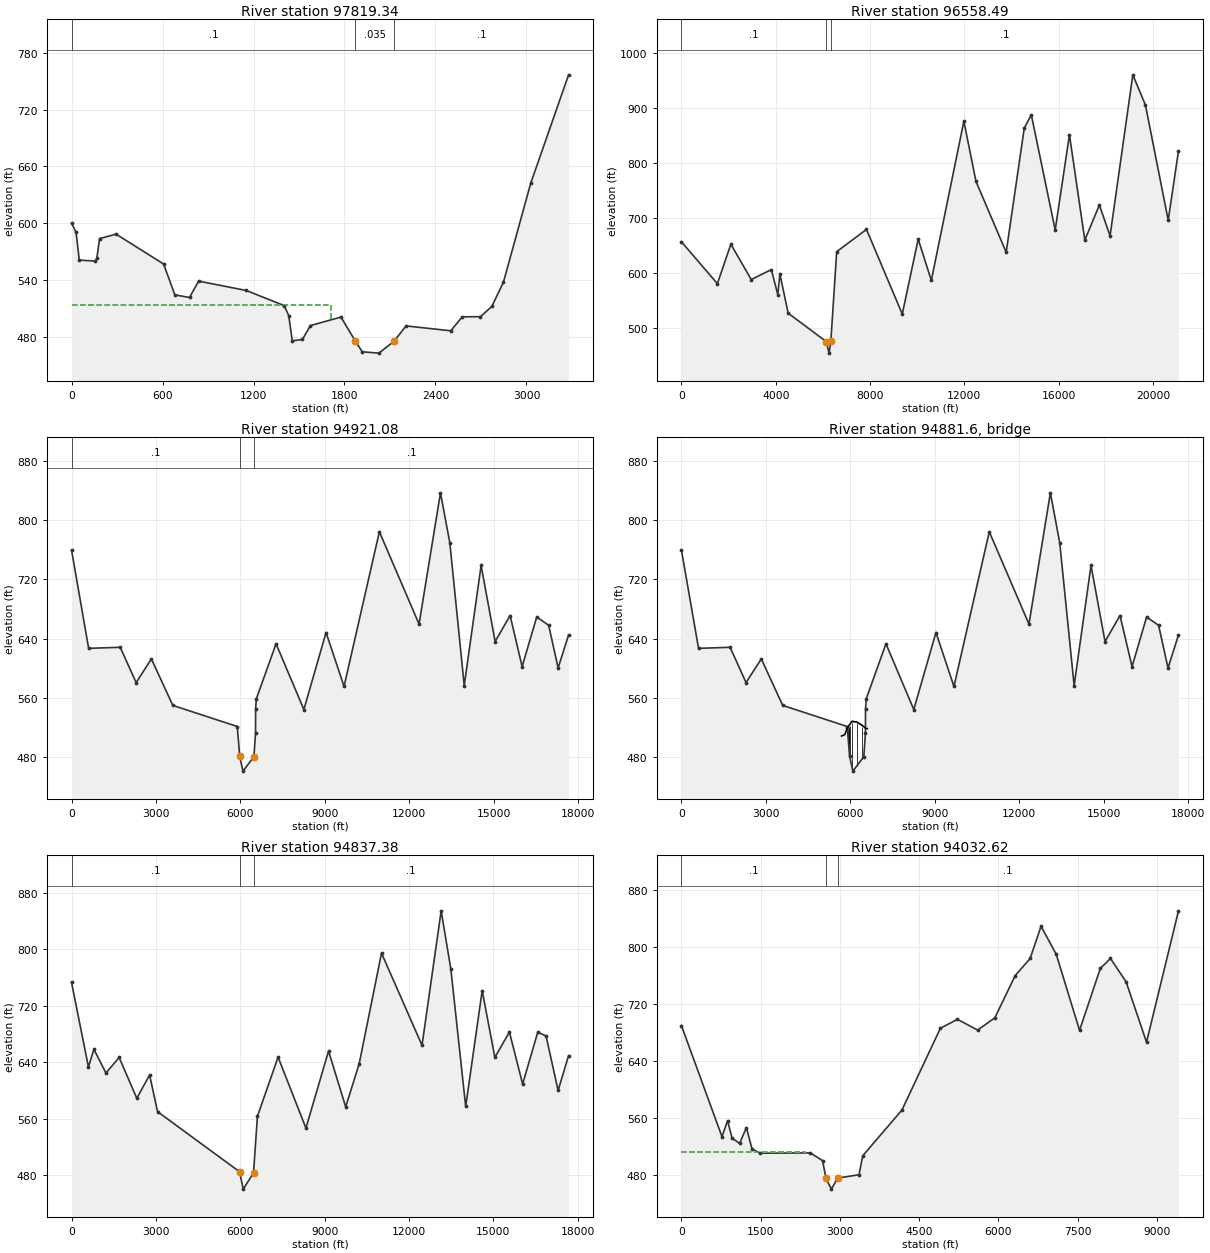
Type RM Length L Ch R = 1 ,97819.34,1036.1,1260.9,1360.3
BEGIN DESCRIPTION:
30403.94
END DESCRIPTION:
XS GIS Cut Line= 4
      2015782.29       657967.55      2016339.91       658499.52
      2017947.29       659468.57      2018306.49       659986.24
#Sta/Elev= 30
       0  600.25    30.1  590.37    51.2  561.01   157.9     560   167.1   563.3
   185.2  583.76   293.8  588.48   607.1  556.89   681.4  524.34     778  521.53
   838.1  538.83  1152.1  528.93  1402.6  512.94  1432.3  502.39  1455.7   475.7
  1522.9  477.22  1575.4  491.87  1776.8  500.82  1871.5  475.42 1917.32  464.13
 2027.12  462.73  2127.1  475.33  2205.8  491.49  2500.8  486.34  2576.7  501.11
  2696.8  501.24  2771.5  512.09    2848  537.66  3027.8  642.13  3277.6  756.83
#Mann= 3 , 0 , 0
       0      .1       0  1871.5    .035       0  2127.1      .1       0
#XS Ineff= 2 , 0
         1708.22  513.17
Permanent Ineff=
       F       F
Bank Sta=1871.5,2127.1
XS Rating Curve= 0 ,0
Exp/Cntr=0.3,0.1

Type RM Length L Ch R = 1 ,96558.49,1548.5,1637.4,1724.2
BEGIN DESCRIPTION:
30005.80
END DESCRIPTION:
XS GIS Cut Line= 6
      2017951.09       654727.48      2015711.72       657969.97
  2016203.976928659560.384405701      2016720.44       660412.46
      2023481.75       665001.23      2027463.72       669878.17
#Sta/Elev= 30
       0  656.75  1525.7  580.41  2096.9  652.31  2961.6  587.93  3813.4  606.09
  4086.7  560.68  4176.6  598.09  4527.3  526.69  6140.2  475.12  6263.1     454
 6337.38  475.21  6585.7  638.67  7849.3  679.21  9367.3  525.12 10042.9  661.44
 10599.5  586.28   11980  876.24 12492.5  766.76 13774.6  637.66 14541.8  863.61
 14840.5  887.84 15853.8  678.18 16457.9  851.43   17110  659.77 17727.4  723.51
 18180.9  667.51 19146.2  960.63 19681.7   905.6 20647.5  695.83 21082.8  822.01
#Mann= 3 , 0 , 0
       0      .1       0  6140.2    .035       0 6337.38      .1       0
Bank Sta=6140.2,6337.38
XS Rating Curve= 0 ,0
Exp/Cntr=0.5,0.3

Type RM Length L Ch R = 1 ,94921.08,79.7,83.7,96.5
BEGIN DESCRIPTION:
29486.64
END DESCRIPTION:
XS GIS Cut Line= 6
      2013697.65       654579.89      2013712.54        655356.2
2015131.42789681661025.156514782        2015447.       661353.12
      2019411.77        667752.3      2020289.37       670674.62
#Sta/Elev= 30
       0  759.96   608.4  626.82    1730  628.22  2295.4  580.46  2837.4  612.55
  3597.6  549.59  5889.3  521.03 5974.43  480.56  6090.9  460.63  6480.3  480.36
  6537.3  512.56  6539.9  545.02  6565.9  558.55  7266.1  632.99  8253.9     544
    9042  648.22  9681.2  575.21   10936   784.6 12345.8  659.61 13106.4  837.29
 13438.3   769.7 13950.2  576.38 14549.6  738.97 15048.2  636.01 15579.9  671.26
 16007.1  602.04 16524.8  669.19 16950.3  658.02 17285.4  600.25 17656.9  644.89
#Mann= 3 , 0 , 0
       0      .1       0 5974.43    .035       0  6480.3      .1       0
Bank Sta=5974.43,6480.3
XS Rating Curve= 0 ,0
Exp/Cntr=0.5,0.3

Type RM Length L Ch R = 3 ,94881.6 ,,,
BEGIN DESCRIPTION:
Betty's Island Bridge
2019 Update:
-Included Momentum low flow calculation
-Adjusted wall heights based on aerials
END DESCRIPTION:
Bridge Culvert--1,0,-1,-1, 0
Deck Dist Width WeirC Skew NumUp NumDn MinLoCord MaxHiCord MaxSubmerge Is_Ogee
26.47,22,2.61,0, 11, 11, , , 0.95, 0, 0,0,,
    5683 5800.24  5813.5 5864.62 5864.67 5981.62 6057.98 6229.32 6403.02 6576.24
 6607.34
  508.06  509.86  510.94  516.57  517.67     524   528.2  527.17  523.22  517.98
  518.21
                          515.23  515.23  521.56  525.88  525.86     521  515.76
  517.21
    5659 5776.24  5789.5 5840.62 5840.67 5957.62 6033.98 6205.32 6379.02 6557.79
 6583.34
  508.06  509.86  510.94  516.57  517.67     524   528.2  527.17  523.22  517.98
  518.21
                          515.23  515.23  521.56  525.88  525.86     521  515.57
  517.21
Pier Skew, UpSta & Num, DnSta & Num=  ,5895, 2 ,5874, 2 , 0 , 0 , 0 ,,
     .67     .67
  502.13     520
     .67     .67
  502.13     520
Pier Skew, UpSta & Num, DnSta & Num=  ,5917, 2 ,5894, 2 , 0 , 0 , 0 ,,
     .67     .67
  502.13     520
     .67     .67
  502.13     520
Pier Skew, UpSta & Num, DnSta & Num=  ,5939, 2 ,5915, 2 , 0 , 0 , 0 ,,
     .67     .67
  502.91     520
     .67     .67
  502.91     520
Pier Skew, UpSta & Num, DnSta & Num=  ,5960, 2 ,5936, 2 , 0 , 0 , 0 ,,
     .67     .67
   504.1    1320
     .67     .67
   504.1    1320
Pier Skew, UpSta & Num, DnSta & Num=  ,5981.62, 2 ,5957.62, 2 , 0 , 0 , 0 ,,
    1.74    1.74
  502.59  521.56
    1.74    1.74
  502.59  521.56
Pier Skew, UpSta & Num, DnSta & Num=  ,6057.98, 2 ,6033.98, 2 , 0 , 0 , 0 ,,
    1.42    1.42
  465.49  525.88
    1.42    1.42
  465.49  525.88
Pier Skew, UpSta & Num, DnSta & Num=  ,6229.32, 2 ,6205.32, 2 , 0 , 0 , 0 ,,
    1.42    1.42
  471.31  525.86
    1.42    1.42
  471.31  525.86
Pier Skew, UpSta & Num, DnSta & Num=  ,6403.02, 2 ,6379.02, 2 , 0 , 0 , 0 ,,
    1.42    1.42
  472.06  520.97
    1.42    1.42
  472.06  520.97
Pier Skew, UpSta & Num, DnSta & Num=  ,6581, 2 ,6557.79, 2 , 0 , 0 , 0 ,,
    1.74    1.74
  501.96  515.76
    1.74    1.74
  501.96  515.57
BR Coef=-1 , 1 , 0 ,, 0 ,,,0.8,-1,1.33,0,
WSPro=,,,, 1 ,,,, 0 ,,,, 0 ,,,,-1 ,-1 ,-1 , 0 , 0 , 0 , 0 , 0
BC Design=,, 0 ,, 0 ,,,,,,
BC HTab HWMax=600
BC Use User HTab Curves=0
BC User HTab FreeFlow(D)= 0

Type RM Length L Ch R = 1 ,94837.38,804.3,804.8,804.7
XS GIS Cut Line= 6
  2013656.264208654586.9263433062013662.40069462655366.260143762
2015040.04194031661073.1926982832015392.88992083661413.767705569
2019366.26500583667780.372571499 2020243.2273015670681.820160354
#Sta/Elev= 30
       0 753.417 600.973 633.703 796.456 658.5971223.376 625.0291694.018 647.044
2321.539 589.298 2776.75 622.2833059.649 570.3165973.774 485.299  6107.9  460.63
 6472.44 483.7086611.318 563.7387345.856 647.5958336.022 547.0599140.205 656.101
9750.545 577.04110230.89 638.24611024.24 794.77712464.66  664.25 13145.4 854.693
13489.76 772.26614017.78  577.6314604.13 741.67915055.42 647.13515572.54 683.044
16042.64  609.3716580.65  682.8616875.77 677.46617304.09 600.33917676.46 649.629
#Mann= 3 , 0 , 0
       0      .1       05973.774    .035       0 6472.44      .1       0
Bank Sta=5973.774,6472.44
XS Rating Curve= 0 ,0
Exp/Cntr(USF)=0,0
Exp/Cntr=0.5,0.3

Type RM Length L Ch R = 1 ,94032.62,2213.2,2212.1,2215.9
BEGIN DESCRIPTION:
29209.28
END DESCRIPTION:
XS GIS Cut Line= 6
       2012242.6       658989.37      2014008.06       659770.02
2014258.51575703661263.441364449      2015052.45       661421.11
      2015019.69       663900.59      2016535.48       666001.24
#Sta/Elev= 30
       0  689.95   767.5  533.72   873.2   556.2   958.3  531.74  1100.5  524.24
  1230.1  546.51  1335.4  516.52  1486.6  510.51  2439.8  510.94  2671.8  500.01
    2736  475.12  2837.8     460  2955.9   475.5  3361.4  480.25  3431.4  506.87
  4173.7  571.23  4901.3  686.17  5223.4  698.75  5605.7  683.66    5932  700.85
  6314.3  759.94  6599.7  784.35  6806.2  829.57  7093.8  790.13  7534.6  683.18
    7928  770.31  8120.4  784.31  8416.3  751.38  8802.2   666.6    9407  851.28
#Mann= 3 , 0 , 0
       0      .1       0    2736    .035       0  2955.9      .1       0
#XS Ineff= 2 , 0
         2339.75  512.03
Permanent Ineff=
       F       F
Bank Sta=2736,2955.9
XS Rating Curve= 0 ,0
Exp/Cntr=0.3,0.1

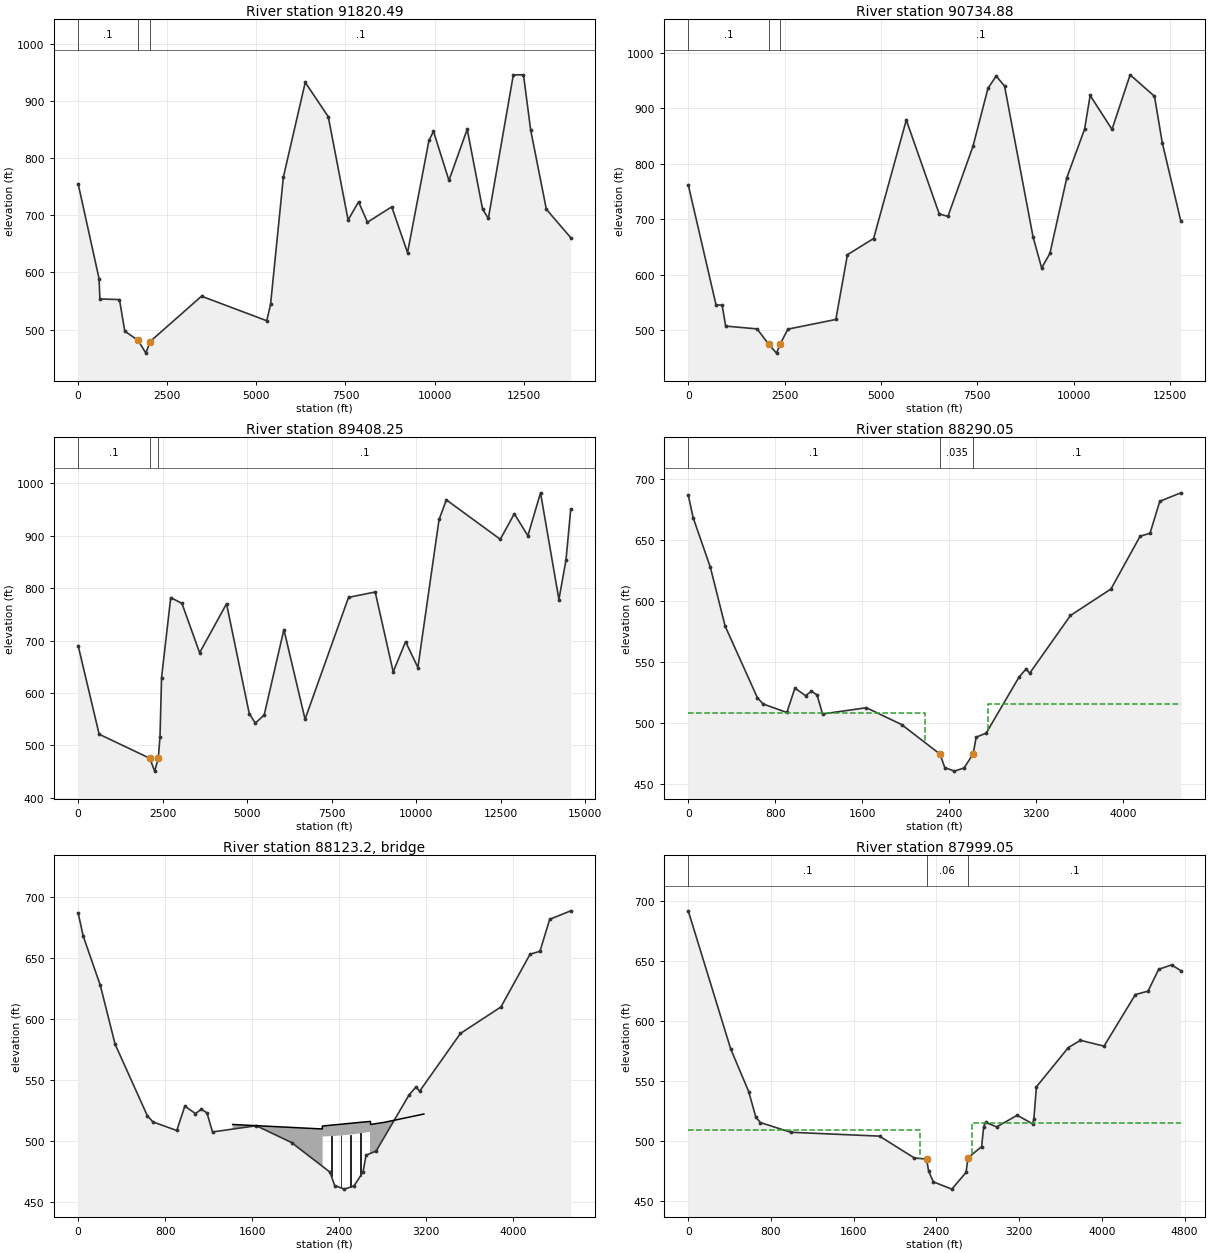
Type RM Length L Ch R = 1 ,91820.49,1065.3,1085.6,1120
BEGIN DESCRIPTION:
28551.80
END DESCRIPTION:
XS GIS Cut Line= 6
       2011579.1       659315.76      2012046.31       661512.98
      2014829.22       665148.12      2015858.86       665442.32
      2016617.17       667544.94      2017570.83       671105.56
#Sta/Elev= 30
       0  754.99   586.2  589.27     609  553.76  1159.3  552.62  1307.3  497.43
  1682.5   481.3  1898.9  458.99  2018.7  479.26  3460.9  558.55  5290.6  515.68
  5398.3  544.16  5757.2  766.72  6371.3   932.5  7017.4  872.47  7574.1  691.78
  7867.1  723.61  8117.4  687.99  8798.5  714.82  9241.6   634.7  9842.2  830.84
  9969.5  846.91 10403.7     761 10916.1  850.53 11345.8  711.19 11508.8  694.62
   12210  945.67 12494.9  945.69 12696.7  849.16 13136.9  710.49 13820.2  660.95
#Mann= 3 , 0 , 0
       0      .1       0  1682.5    .035       0  2018.7      .1       0
Bank Sta=1682.5,2018.7
XS Rating Curve= 0 ,0
Exp/Cntr=0.3,0.1

Type RM Length L Ch R = 1 ,90734.88,1123.3,1326.6,1546.9
BEGIN DESCRIPTION:
28220.98
END DESCRIPTION:
XS GIS Cut Line= 6
       2011495.4       659281.89       2010873.2        660920.7
      2011046.43       662224.86      2010962.97       663345.11
      2012985.05       666957.22      2014334.55       671180.63
#Sta/Elev= 30
       0  762.36   721.4  545.76   879.9  545.17   971.6   507.5  1788.1  502.41
  2083.4  475.12  2291.2  458.73  2387.6  475.28  2586.2     502  3830.7  519.43
  4131.5  636.21  4810.6   665.4    5659  879.05  6512.8  709.83  6739.1  705.26
  7389.5  831.69  7778.4  936.25  7991.2   958.4  8208.9  940.23  8947.6  668.64
  9171.7  612.27  9385.9  638.56  9824.2  774.92 10285.5  862.59 10430.5  923.38
 10997.4  862.19 11467.2  960.57 12099.5  921.93 12301.8  838.03 12782.3  697.16
#Mann= 3 , 0 , 0
       0      .1       0  2083.4    .035       0  2387.6      .1       0
Bank Sta=2083.4,2387.6
XS Rating Curve= 0 ,0
Exp/Cntr=0.3,0.1

Type RM Length L Ch R = 1 ,89408.25,977.7,1118.2,1289.2
BEGIN DESCRIPTION:
27816.72
END DESCRIPTION:
XS GIS Cut Line= 6
      2011267.62       659423.16      2010347.77       660488.49
      2009487.34       661195.52      2008532.52       666296.33
      2007220.58       667777.26      2006648.41       672621.97
#Sta/Elev= 30
       0  690.12   620.6  521.02  2117.5  475.12  2262.2  450.55  2369.7  475.12
  2420.2  516.06  2466.7  629.27  2737.3  782.07    3069  770.88  3591.9  676.63
  4387.8   770.2  5059.5  560.59    5240  542.23    5502  557.88  6084.5  720.93
  6710.2  549.75  7996.6  782.46  8784.9  792.63    9317  640.11  9683.6  697.72
 10047.2  648.47 10674.1  931.25 10890.6  968.59 12484.1  893.36 12899.4  942.09
 13300.2  900.14 13674.8  982.09 14218.5  778.34 14428.2  854.05 14567.5  950.41
#Mann= 3 , 0 , 0
       0      .1       0  2117.5    .035       0  2369.7      .1       0
Bank Sta=2117.5,2369.7
XS Rating Curve= 0 ,0
Exp/Cntr=0.5,0.3

Type RM Length L Ch R = 1 ,88290.05,268.8,291,302.5
BEGIN DESCRIPTION:
27480.75
END DESCRIPTION:
XS GIS Cut Line= 6
      2011176.11       659306.03       2010184.3       660128.98
      2008315.24       660085.73      2008368.59       660543.64
      2008609.72       660886.24      2008671.46       661376.69
#Sta/Elev= 30
       0  686.65      46  667.82   204.1  627.21   339.6  579.11   636.1  520.46
   688.1  515.31   907.3  508.28   981.7  528.28  1079.6  522.12  1133.7  525.72
  1185.2  522.73  1236.2  507.08  1639.1  512.19  1963.7  498.38    2317  474.15
 2360.26  463.17 2449.29   460.2 2538.73  462.84  2621.9  474.36  2649.4  488.05
  2741.9  491.38  3044.9  537.46  3109.5  544.03    3142  540.49  3517.6  587.86
  3890.1  609.57  4158.4  652.84  4249.5  655.28  4339.1  681.47  4532.6  688.43
#Mann= 3 , 0 , 0
       0      .1       0    2317    .035       0  2621.9      .1       0
#XS Ineff= 2 , 0
         2174.65  507.48 2760.48          515.03
Permanent Ineff=
       F       F
Bank Sta=2317,2621.9
XS Rating Curve= 0 ,0
Exp/Cntr=0.5,0.3

Type RM Length L Ch R = 3 ,88123.2 ,,,
BEGIN DESCRIPTION:
I 40 Bridge # 4
2019 Update:
-Increased deck width to encompass both lanes of bridge
-Included Momentum equation for low flow
END DESCRIPTION:
Bridge Culvert--1,0,-1,-1, 0
Deck Dist Width WeirC Skew NumUp NumDn MinLoCord MaxHiCord MaxSubmerge Is_Ogee
68.47,150,2.61,0, 16, 16, , , 0.95, 0, 0,0,,
 1421.56 2246.25 2246.59  2246.6 2249.16 2249.65 2335.94 2424.56  2513.6 2602.44
 2685.48 2687.43 2690.12 2690.13 2820.34 3181.27
  513.22  509.54  509.54  511.59  511.97  511.97  512.72  513.48  514.24  515.01
  515.72  515.74  515.33  513.22  515.03  521.79
                                          503.39  503.69  504.27  505.02  506.02
  507.22
 1410.56 2263.53 2264.74 2264.75 2267.67 2281.03 2357.67 2447.75 2533.56 2622.71
 2710.47 2720.31 2723.65 2723.66 2809.34 3170.27
  513.22   508.7   508.7  510.81  511.35  511.48  512.22   513.1  513.93  514.79
  515.64  515.74   515.3  513.19  515.03  521.79
                                          502.96  503.36  503.95   504.8  505.92
  507.11
Pier Skew, UpSta & Num, DnSta & Num=  ,2330.26, 2 ,2533.56, 2 , 0 , 0 , 0 ,,
    6.68    6.68
  462.84  505.02
    6.68    6.68
  462.84   504.8
Pier Skew, UpSta & Num, DnSta & Num=  ,2419.29, 2 ,2357.67, 2 , 0 , 0 , 0 ,,
    6.68    6.68
  463.17  505.69
    6.68    6.68
  463.17  503.36
Pier Skew, UpSta & Num, DnSta & Num=  ,2508.73, 2 ,2622.71, 2 , 0 , 0 , 0 ,,
    6.68    6.68
  476.08  506.02
    6.68    6.68
  476.08  505.92
Pier Skew, UpSta & Num, DnSta & Num=  ,2597.24, 2 ,2447.75, 2 , 0 , 0 , 0 ,,
    6.68    6.68
   460.2  507.27
    6.68    6.68
   460.2  503.95
BR Coef=-1 , 1 , 0 ,, 0 ,,,0.8,0,1.33,0,
WSPro=,,,, 1 ,,,, 0 ,,,, 0 ,,,,-1 ,-1 ,-1 , 0 , 0 , 0 , 0 , 0
BC Design=,, 0 ,, 0 ,,,,,,
BC HTab HWMax=610
BC Use User HTab Curves=0
BC User HTab FreeFlow(D)= 0

Type RM Length L Ch R = 1 ,87999.05,580.5,438.7,290.8
BEGIN DESCRIPTION:
27418.31
END DESCRIPTION:
XS GIS Cut Line= 6
      2011112.09       659160.812010144.10881309659885.762373828
2008222.72079128659852.714352017      2008286.75       660690.36
      2008510.66       660953.49      2008535.04       661399.13
#Sta/Elev= 30
       0  691.41   410.8  576.46   584.7  540.97   653.4  519.76   698.3  515.23
   991.2  507.16  1849.5  503.94    2187  485.74  2304.6  484.83  2324.6  474.86
 2369.67  465.93 2548.86  459.84  2687.1  473.81  2704.6   485.9  2837.1  495.16
  2857.1  511.94  2874.6  515.47  2982.2  511.61  3181.5  521.31  3329.3  514.22
  3342.1  518.04  3366.9  544.99  3675.3   577.6  3793.1  583.66  4020.7  578.82
  4323.5  621.72  4446.2   624.6  4548.9  642.73    4674  646.43  4762.9  641.66
#Mann= 3 , 0 , 0
       0      .1       0  2304.6     .06       0  2704.6      .1       0
#XS Ineff= 2 , 0
         2244.53     509 2746.97           514.5
Permanent Ineff=
       F       F
Bank Sta=2304.6,2704.6
XS Rating Curve= 0 ,0
Exp/Cntr=0.5,0.3

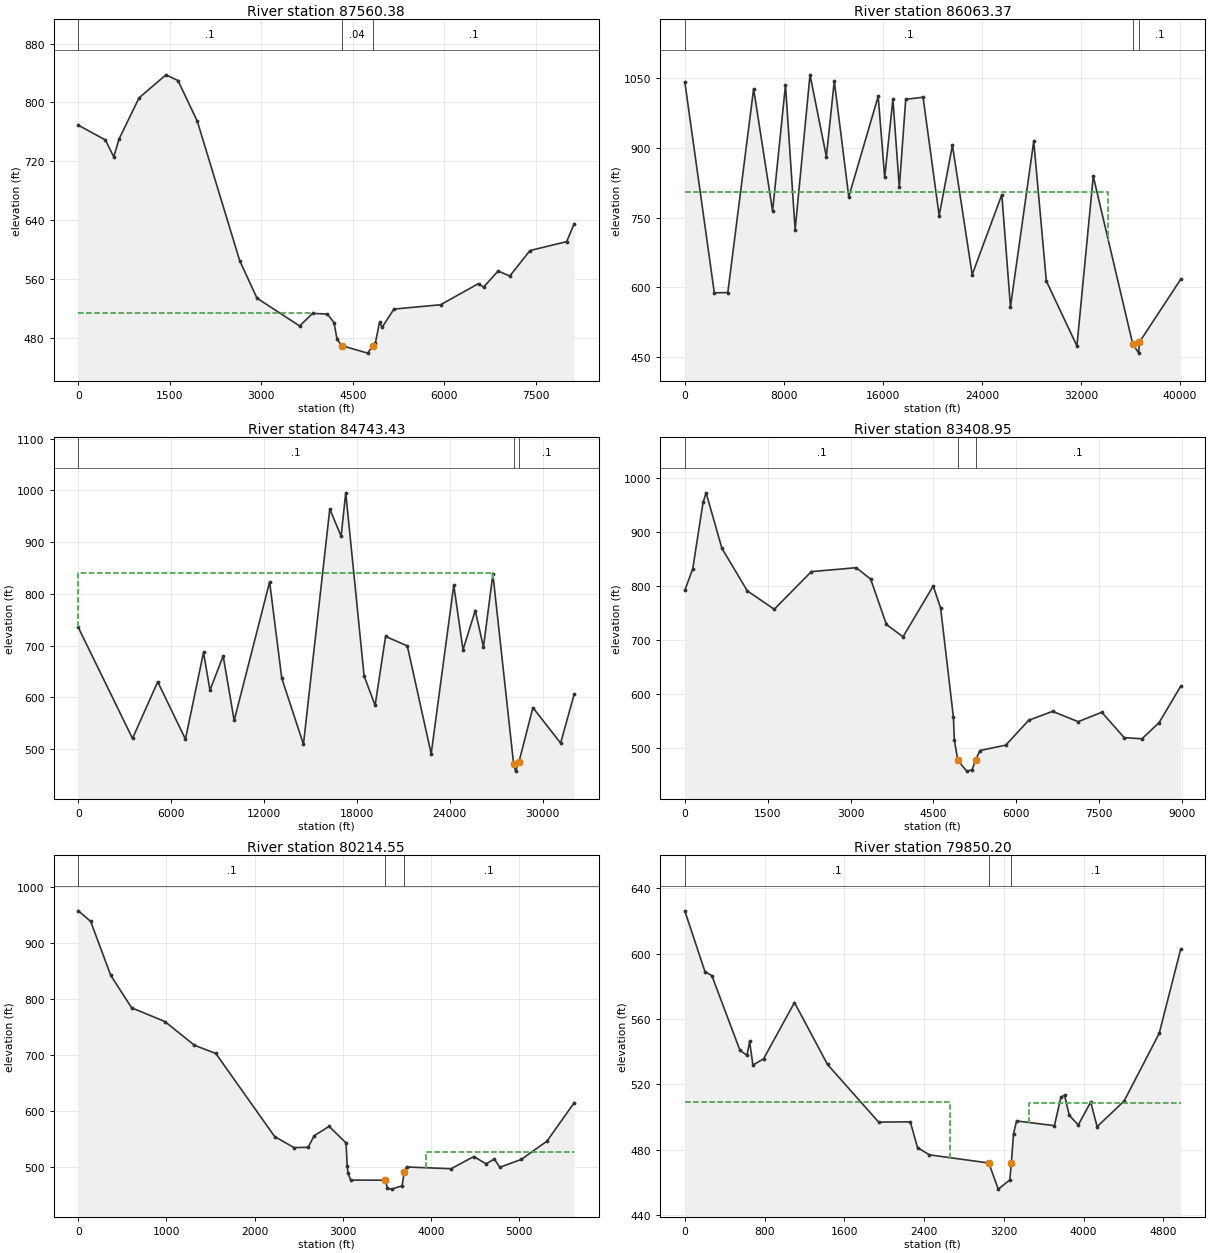
Type RM Length L Ch R = 1 ,87560.38,1501.4,1497,1490.3
BEGIN DESCRIPTION:
27234.64
END DESCRIPTION:
XS GIS Cut Line= 6
      2012510.91       657068.41      2008090.34       659831.01
      2007824.96       660368.65      2008093.47       660810.43
      2008219.25       661349.84       2008822.8       662432.92
#Sta/Elev= 30
       0  769.09   443.6  749.03   580.8  726.05   668.3  750.46   995.4  806.26
  1436.8  837.57  1633.7  829.78  1950.6  774.43  2645.8  584.88  2928.4  534.01
  3627.7  496.16  3840.4  513.25  4083.7  512.34  4191.8  500.69    4241  478.18
 4319.32  469.39    4742  459.22 4826.95  468.97    4871  473.66  4938.1  501.01
  4981.8  494.42  5174.2  519.12  5938.5     525    6561  553.75    6643  548.87
  6881.8  570.91  7073.2  564.01  7404.5  598.69  8005.5   610.8  8128.6  635.08
#Mann= 3 , 0 , 0
       0      .1       0 4319.32     .04       0 4826.95      .1       0
#XS Ineff= 2 , 0
         3832.89  514.02
Permanent Ineff=
       F       F
Bank Sta=4319.32,4826.95
XS Rating Curve= 0 ,0
Exp/Cntr=0.3,0.1

Type RM Length L Ch R = 1 ,86063.37,1701.7,1319.9,973.3
BEGIN DESCRIPTION:
26775.19
END DESCRIPTION:
XS GIS Cut Line= 6
1996369.48906474628063.1806890672008580.78482535639867.474943253
       2009731.4       657032.86      2007155.28       658669.85
      2007548.46       659126.21      2007702.02       661231.33
#Sta/Elev= 30
       0 1041.99  2384.7  588.58  3474.3  589.12  5559.3 1026.89  7092.7  764.27
  8132.4 1034.91  8912.1  723.92 10114.3 1056.91 11435.6  881.16 12074.7 1043.43
 13247.2  794.85 15621.3 1010.73 16146.8  836.46 16809.8 1004.15 17327.7     815
 17846.4 1004.27 19246.5  1008.8 20547.5  754.59 21619.8  905.57 23215.9  627.61
 25608.7  799.51 26307.8  558.39   28187  914.31 29204.3  613.88 31674.8   474.5
 32995.4  839.03 36181.5  478.8236669.77     459 36710.3  482.06 40051.9  617.37
#Mann= 3 , 0 , 0
       0      .1       0 36181.5    .035       0 36710.3      .1       0
#XS Ineff= 2 , 0
        34220.78  804.63
Permanent Ineff=
       F       F
Bank Sta=36181.5,36710.3
XS Rating Curve= 0 ,0
Exp/Cntr=0.3,0.1

Type RM Length L Ch R = 1 ,84743.43,1511.6,1334.5,1224.5
BEGIN DESCRIPTION:
26296.82
END DESCRIPTION:
XS GIS Cut Line= 6
1987468.82060636639158.791553708 2002469.6792999647112.779274863
      2006419.95       656185.49      2006755.24       657101.92
       2007012.3       658722.45      2007626.97       661192.38
#Sta/Elev= 30
       0  735.17  3500.6  520.87  5130.5  630.26    6921  519.36  8089.7  687.12
  8505.8  613.97  9358.3   680.3 10070.2  555.52 12360.4  823.18 13144.2  637.28
 14545.8  509.62 16248.3  964.05 16979.2  911.49 17279.2  995.31 18465.3  641.71
 19176.6  584.61 19853.2  717.94 21257.4  699.65 22800.7   491.2 24259.9  816.94
 24856.7     692 25647.4  767.98 26177.2  697.33 26787.2   838.2   28124   472.2
 28250.7   457.7 28471.5  475.48 29372.6  580.35 31164.6  511.88 32038.4  606.23
#Mann= 3 , 0 , 0
       0      .1       0   28124    .035       0 28471.5      .1       0
#XS Ineff= 2 , 0
        26822.43  839.76
Permanent Ineff=
       F       F
Bank Sta=28124,28471.5
XS Rating Curve= 0 ,0
Exp/Cntr=0.3,0.1

Type RM Length L Ch R = 1 ,83408.95,3433,3194.4,2943.1
BEGIN DESCRIPTION:
25907.71
END DESCRIPTION:
XS GIS Cut Line= 6
       2000699.5         658359.      2005278.42       657692.34
2005937.52870403658388.457557688      2006685.73       659018.87
      2007061.51       659758.26      2007618.58       661239.07
#Sta/Elev= 30
       0  791.99   143.6  831.78   330.5  954.96   386.1   972.7   671.6  869.92
  1131.4  791.08  1619.3  756.96    2291  826.73  3103.4  833.93  3364.7  812.81
  3650.3  728.73  3950.8  705.96  4497.2  800.06  4631.4   759.1  4862.1  557.43
  4880.9  514.34    4941  477.32  5102.6  457.01  5201.5  459.46  5264.9  477.94
  5344.2  495.19  5811.1  505.26  6225.3  551.19  6658.5   567.8  7121.2  548.62
  7549.9  566.09  7953.3  519.15  8277.1  516.91  8587.9  547.11  8976.2     614
#Mann= 3 , 0 , 0
       0      .1       0    4941    .035       0  5264.9      .1       0
Bank Sta=4941,5264.9
XS Rating Curve= 0 ,0
Exp/Cntr=0.3,0.1

Type RM Length L Ch R = 1 ,80214.55,613,364.3,301.6
BEGIN DESCRIPTION:
24879.73
END DESCRIPTION:
XS GIS Cut Line= 6
      2002234.15       661003.21      2004546.28       661048.43
      2005082.62       661188.812006147.12261221660773.084106521
      2006375.98       660640.58      2007563.46       661281.32
#Sta/Elev= 30
       0  956.66   139.9  937.81   367.5  841.56     605  783.52   982.6  758.95
  1317.7  716.69  1560.2  701.96  2227.8  553.63  2447.2  533.97  2607.5  534.45
  2675.7  555.04  2845.2  571.88    3038  542.24  3050.8  501.77  3060.3  488.59
  3089.9   475.9  3484.8  475.75  3507.8     461  3553.9   459.8  3673.4   465.7
  3698.7   490.5  3724.9  499.36  4229.8   496.2  4487.1  517.99  4627.7   504.9
  4720.5  513.65  4782.4  498.76  5027.1  512.91  5317.6  545.47  5626.1  614.03
#Mann= 3 , 0 , 0
       0      .1       0  3484.8    .055       0  3698.7      .1       0
#XS Ineff= 2 , 0
                         3946.95          525.85
Permanent Ineff=
       F       F
Bank Sta=3484.8,3698.7
XS Rating Curve= 0 ,0
Exp/Cntr=0.5,0.3

Type RM Length L Ch R = 1 ,79850.20,637.3,575,564.5
BEGIN DESCRIPTION:
24710.55
END DESCRIPTION:
XS GIS Cut Line= 6
      2003603.11       662018.37      2004421.27       662744.79
2005749.03387381661360.7431012522006213.43259904660909.494379411
      2007327.37       661290.71      2007446.12         661352.
#Sta/Elev= 30
       0   626.3   202.2  589.08   271.3  586.63   552.8     541   623.1  537.83
   650.2  546.38   683.3  531.87     790  535.69  1099.9  570.18  1431.5  532.24
  1944.2  496.96  2261.9  497.15  2334.5  481.31    2454  476.92  3048.8  471.94
 3144.21  455.94 3259.78  461.58  3275.3  471.94    3297  489.77  3327.6  497.67
  3707.2  494.81    3772  512.17  3809.1  513.46    3856  501.12  3946.4  495.22
  4071.3  509.27  4135.3  494.18  4406.1  509.87  4758.3   551.3    4973   602.7
#Mann= 3 , 0 , 0
       0      .1       0  3048.8    .045       0  3275.3      .1       0
#XS Ineff= 2 , 0
         2657.79     509 3456.36          508.37
Permanent Ineff=
       F       F
Bank Sta=3048.8,3275.3
XS Rating Curve= 0 ,0
Exp/Cntr=0.5,0.3