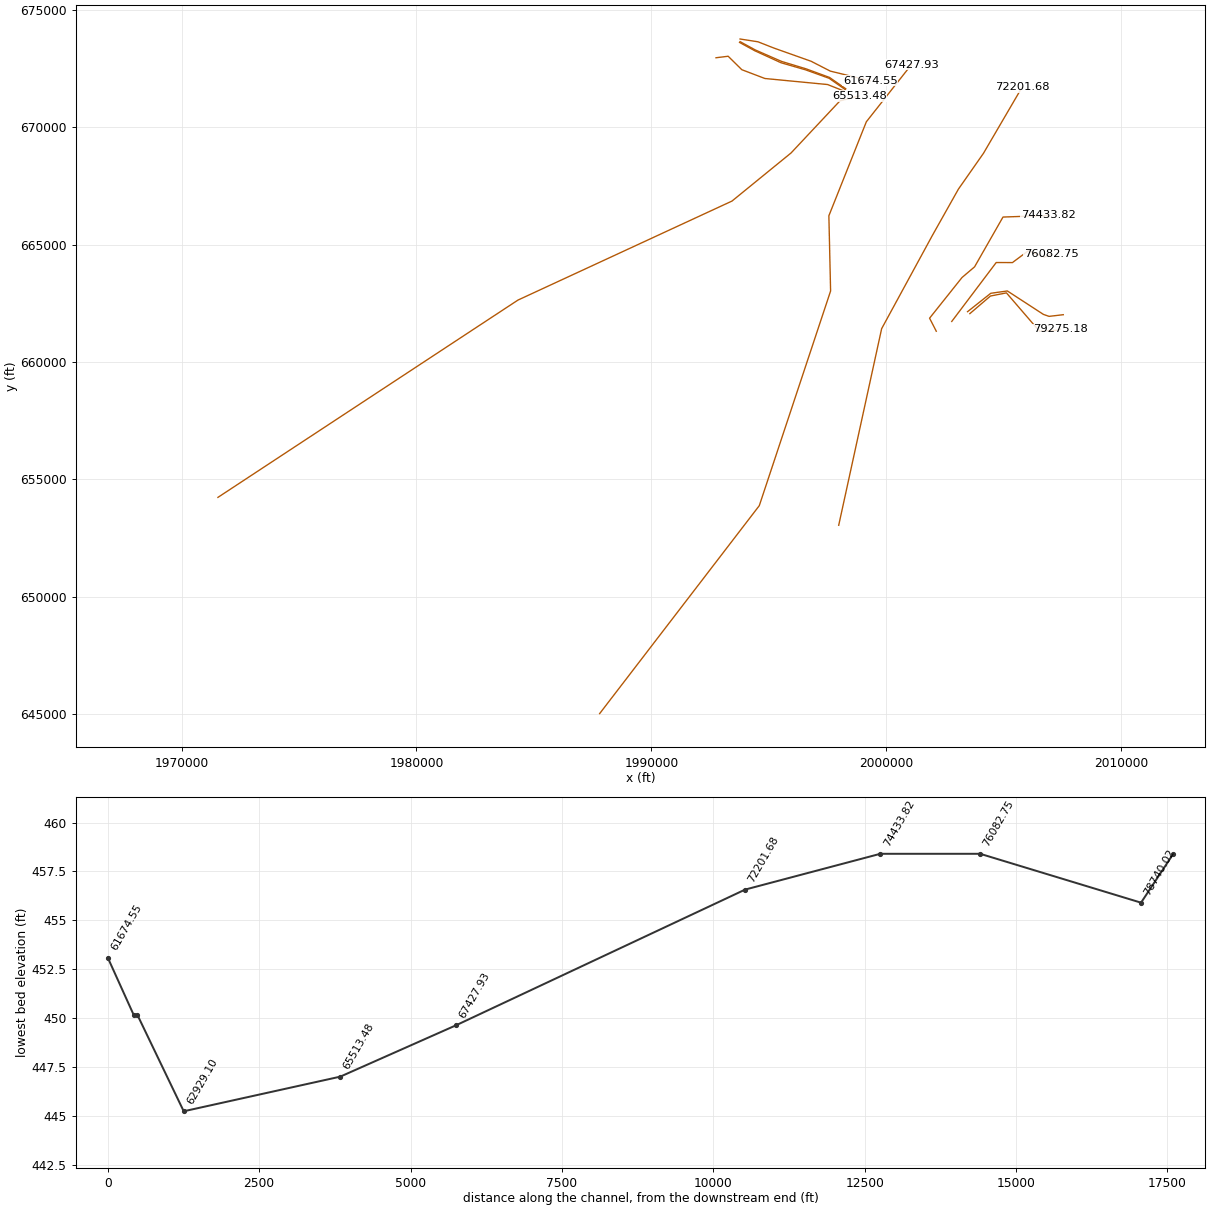
HEC-RAS study CaneyFork.prj: Caney Fork River- Smith County

--- CaneyFork.g02 (geometry) --- (continued)

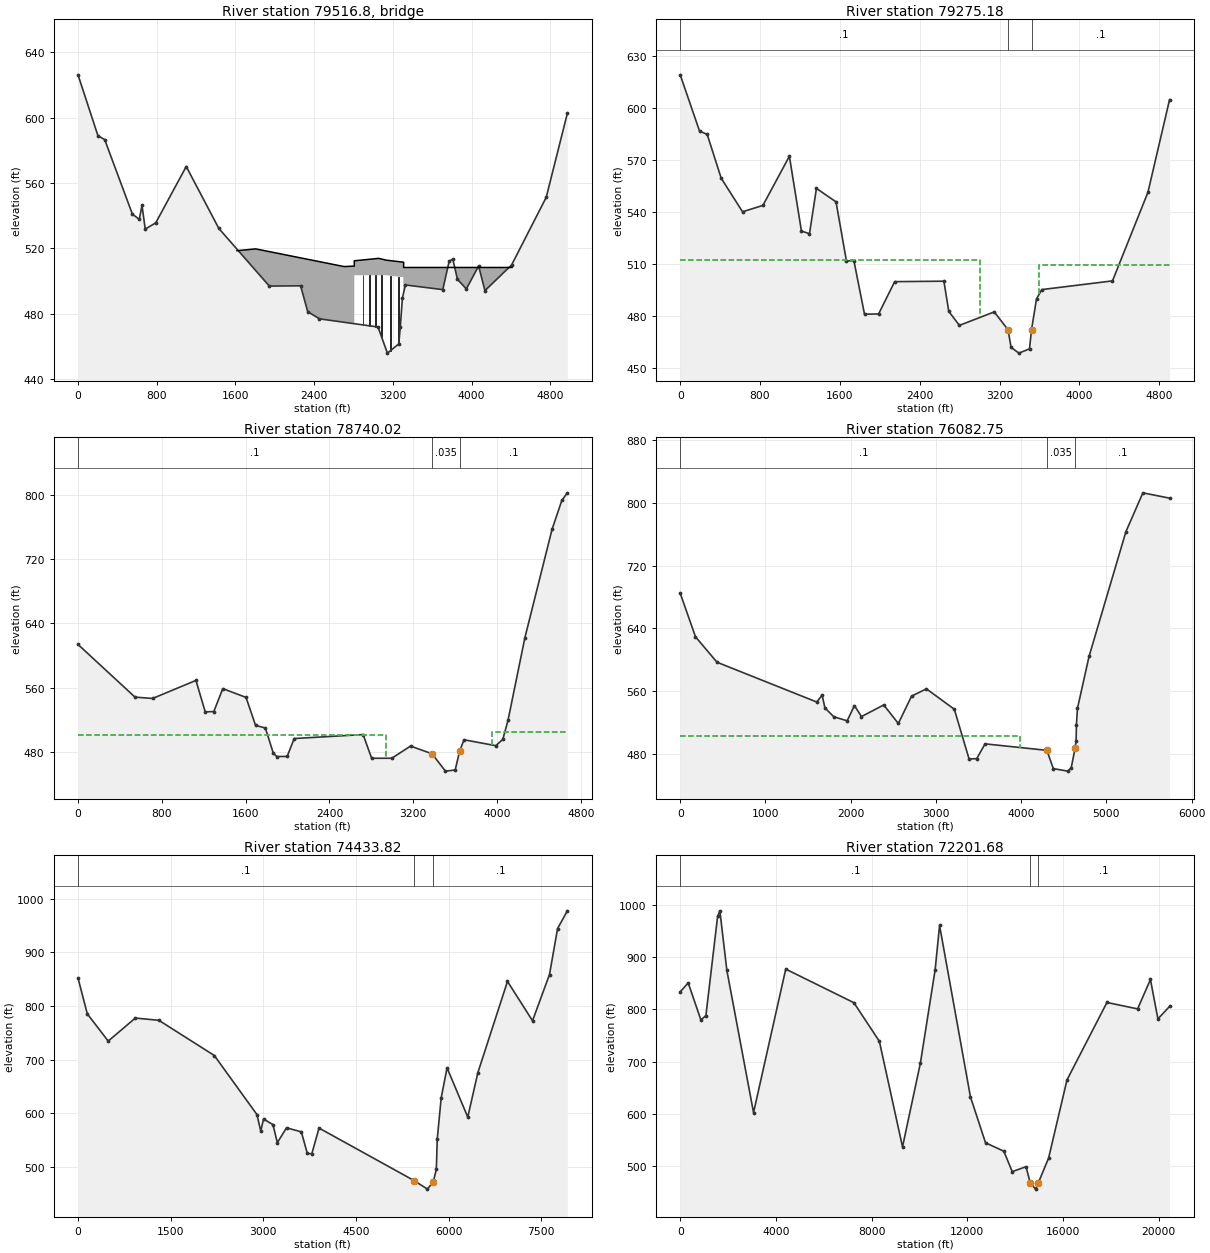
Type RM Length L Ch R = 3 ,79516.8 ,,,
Bridge Culvert--1,0,-1,-1, 0
Deck Dist Width WeirC Skew NumUp NumDn MinLoCord MaxHiCord MaxSubmerge Is_Ogee
136,330,2.6,0, 13, 12, , , 0.98, 0, 0,0,,
  1615.8    1805 2704.22 2807.77 2807.78 2807.79 3057.05 3132.56 3306.36 3309.28
 3309.29    4275    4410
  518.64  519.75  508.92  509.22  512.46  512.46  513.95  512.84  511.61  511.61
  508.37  508.37  508.37
                                          503.61  503.61  503.61  502.42
                        
    1727    2083 2962.22 3058.11 3058.11 3058.12 3262.27 3300.73  3545.6 3545.61
 3545.66    4533
  513.14  519.75  508.92  506.15  509.39  509.39  510.79  510.88  511.78  511.78
  509.58  509.58
                                          504.13  504.13  504.13  504.13
                
Pier Skew, UpSta & Num, DnSta & Num=  ,2898, 2 ,3146, 2 , 0 , 0 , 0 ,,
    6.68    6.68
   477.3  504.13
    6.68    6.68
  478.94  504.13
Pier Skew, UpSta & Num, DnSta & Num=  ,2960, 2 ,3208, 2 , 0 , 0 , 0 ,,
    6.68    6.68
  475.43  504.13
    6.68    6.68
  474.87  504.13
Pier Skew, UpSta & Num, DnSta & Num=  ,3020, 2 ,3268, 2 , 0 , 0 , 0 ,,
    6.68    6.68
  473.91  504.22
    6.68    6.68
  473.57  505.22
Pier Skew, UpSta & Num, DnSta & Num=  ,3085, 2 ,3333, 2 , 0 , 0 , 0 ,,
    6.68    6.68
  465.79  503.61
    6.68    6.68
  465.79  504.13
Pier Skew, UpSta & Num, DnSta & Num=  ,3174, 2 ,3423, 2 , 0 , 0 , 0 ,,
    6.68    6.68
  457.24  504.12
    6.68    6.68
  456.31  504.12
Pier Skew, UpSta & Num, DnSta & Num=  ,3259, 2 ,3502, 2 , 0 , 0 , 0 ,,
    6.68    6.68
  469.09  504.22
    6.68    6.68
  467.99  505.22
BR Coef=-1 , 1 , 0 ,, 0 ,,,0.8,0,1.33,0,
WSPro=,,,, 1 ,,,, 0 ,,,, 0 ,,,,-1 ,-1 ,-1 , 0 , 0 , 0 , 0 , 0
BC Design=,, 0 ,, 0 ,,,,,,
BC HTab HWMax=600
BC Use User HTab Curves=0
BC User HTab FreeFlow(D)= 0

Type RM Length L Ch R = 1 ,79275.18,327.9,535.2,577.2
BEGIN DESCRIPTION:
24643.94
END DESCRIPTION:
XS GIS Cut Line= 6
      2003556.87        662059.7      2004433.58       662808.83
2005114.22987673662943.1274075472006522.29548414661308.864795333
      2007286.34       661353.65      2007411.86       661400.96
#Sta/Elev= 30
       0  619.15   193.6  586.68   270.4  584.73   410.6  559.46   624.4  540.06
   828.3   543.7    1094  572.12  1214.8  528.94  1295.4  527.39  1365.2  553.55
  1561.4  545.78  1665.9   511.6  1740.2  511.89  1846.9  480.88  1987.9  481.04
    2149  499.69  2642.5  499.96  2691.2  482.53  2797.4  474.43  3146.9  482.22
    3285  471.94 3315.61  461.75 3393.92  458.41 3500.25  460.88  3520.6  471.94
  3570.7  489.76  3623.8  495.11  4331.8  500.13  4687.2   551.3  4903.8  604.82
#Mann= 3 , 0 , 0
       0      .1       0    3285    .035       0  3520.6      .1       0
#XS Ineff= 2 , 0
         3006.62     512  3597.1          509.58
Permanent Ineff=
       F       F
Bank Sta=3285,3520.6
XS Rating Curve= 0 ,0
Exp/Cntr=0.5,0.3

Type RM Length L Ch R = 1 ,78740.02,1955.6,2657.3,2824.3
BEGIN DESCRIPTION:
24510.33
END DESCRIPTION:
XS GIS Cut Line= 6
      2003458.57       662142.34      2004446.43       662925.33
2005152.83480851663024.9926122142006688.76686177662026.528219629
2006928.36794674661943.4102794772007533.96617296662014.374801919
#Sta/Elev= 30
       0   613.7   544.2  548.06     712  546.43  1125.4  568.88  1214.4  529.75
  1296.1   530.1  1381.9  558.67  1603.7  547.72  1694.9   512.8  1788.3  509.66
  1864.1  478.23  1896.9  474.12  1996.1  474.17  2063.5  496.51  2721.3  501.44
  2802.5  471.94  2994.7  471.94  3173.8   487.1  3379.5   477.5  3506.8   455.9
    3600   457.3  3641.8  480.49    3684     495  3987.4  487.59  4054.7  495.56
  4104.3  519.25  4265.3   622.1  4524.6  757.08  4618.1  793.18  4670.5  802.55
#Mann= 3 , 0 , 0
       0      .1       0  3379.5    .035       0  3641.8      .1       0
#XS Ineff= 2 , 0
         2937.67  501.22 3952.25          505.12
Permanent Ineff=
       F       F
Bank Sta=3379.5,3641.8
XS Rating Curve= 0 ,0
Exp/Cntr=0.3,0.1

Type RM Length L Ch R = 1 ,76082.75,1604.7,1648.9,1719.4
XS GIS Cut Line= 6
      2002786.39       661726.092004678.98044038664234.936028246
2005369.80351687664232.8143551892006051.33485251664740.437349382
2006739.77555667664462.616116704      2007015.35       664591.17
#Sta/Elev= 30
       0  684.72   179.2  629.37   431.2  596.97  1601.1  546.36  1664.8  555.04
  1697.7  538.88  1801.5  527.54  1958.7  522.46  2043.8  541.77  2126.3  527.81
  2387.3  542.59  2559.1  519.01  2714.1  553.83  2888.4   563.1  3215.6  537.16
  3388.7  473.92  3478.7  474.29  3576.2  493.11  4301.3  484.85  4377.3   461.6
  4545.7   458.4  4586.7   462.5  4632.2  487.32  4644.7  497.24  4648.1  517.36
  4660.4  538.27  4796.3  604.37  5228.5  763.04  5427.8  812.51  5740.7  805.73
#Mann= 3 , 0 , 0
       0      .1       0  4301.3    .035       0  4632.2      .1       0
#XS Ineff= 2 , 0
         3986.74  503.17
Permanent Ineff=
       F       F
Bank Sta=4301.3,4632.2
XS Rating Curve= 0 ,0
Exp/Cntr=0.3,0.1

Type RM Length L Ch R = 1 ,74433.82,2214.2,2232.1,2234.7
BEGIN DESCRIPTION:
23165.45
END DESCRIPTION:
XS GIS Cut Line= 6
      2002127.87       661310.83      2001842.49       661865.31
       2003223.9       663597.64      2003757.56       664050.51
      2004967.27       666170.62      2006892.41       666238.39
#Sta/Elev= 30
       0  851.87   150.3  785.13   488.8  734.34   927.5  777.21    1308   773.1
  2206.3  707.44  2895.6  597.49  2958.2  566.53  3002.7  589.07  3156.1   578.6
    3226  544.94    3375  572.67  3614.9  565.16  3711.4  525.01  3784.3  524.24
  3901.2  572.21  5441.5  474.22  5656.7   458.4  5750.4  471.94  5799.9  495.12
  5814.5  551.42  5878.5  628.44  5973.5  684.47  6308.8  592.62  6471.8  675.32
  6951.7  845.57  7356.9  772.22  7631.8  858.41  7762.2  943.99  7920.6  977.11
#Mann= 3 , 0 , 0
       0      .1       0  5441.5    .035       0  5750.4      .1       0
Bank Sta=5441.5,5750.4
XS Rating Curve= 0 ,0
Exp/Cntr=0.3,0.1

Type RM Length L Ch R = 1 ,72201.68,4740,4773.8,4783.2
BEGIN DESCRIPTION:
22483.99
END DESCRIPTION:
XS GIS Cut Line= 6
      1997974.74       653051.45      1999802.02       661418.86
      2001957.97       665381.57      2003068.87       667357.51
      2004136.43       668883.65      2005774.91       671687.55
#Sta/Elev= 30
       0  833.58   334.1  850.61   863.8   779.8  1073.7  788.13  1562.4  977.49
  1657.1  988.29  1949.7  874.54  3064.5   602.8  4410.5  876.97  7258.6  812.78
  8323.1  739.08  9291.6  537.29 10040.6  697.88 10655.3  875.76 10840.3  960.35
 12129.6     633 12761.4  545.04 13525.4  529.04 13876.6  489.99 14453.6  499.41
14632.91   467.7 14854.7  456.5714957.33  467.53 15395.5  515.65 16167.5  665.38
 17835.6  813.21 19118.2  800.92   19654  857.12 19966.7  781.77 20452.8  805.67
#Mann= 3 , 0 , 0
       0      .1       014632.91    .035       014957.33      .1       0
Bank Sta=14632.91,14957.33
XS Rating Curve= 0 ,0
Exp/Cntr=0.3,0.1

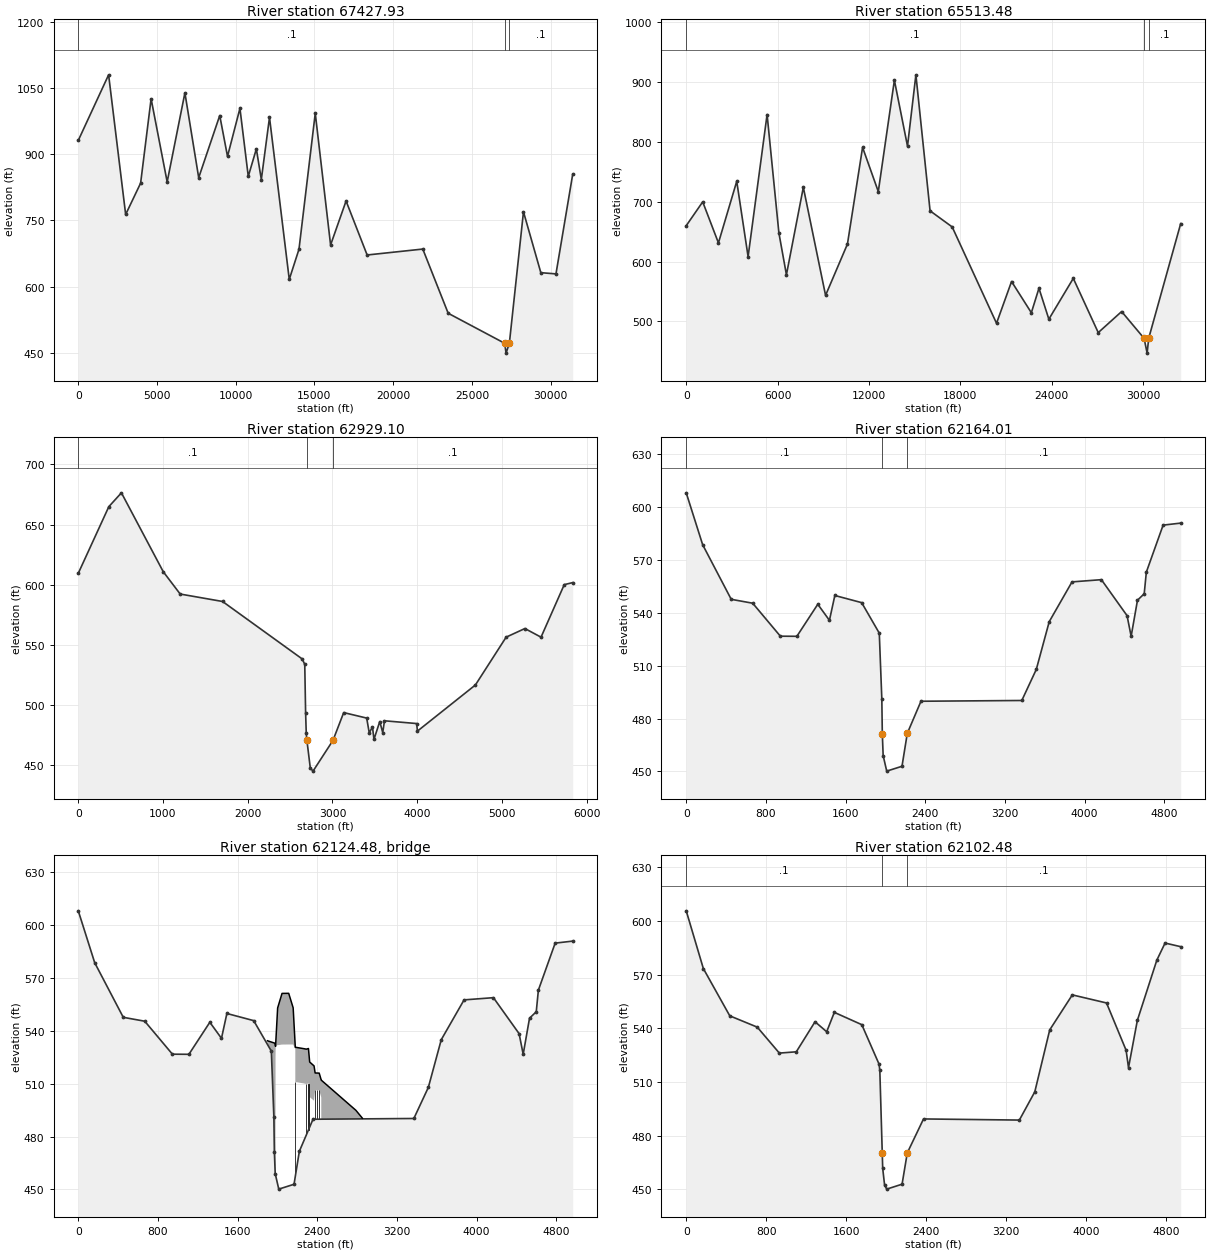
Type RM Length L Ch R = 1 ,67427.93,2217.2,1914.4,1836.6
BEGIN DESCRIPTION:
21021.50
END DESCRIPTION:
XS GIS Cut Line= 6
1987797.90025874645033.0687828431994594.39003842653886.176211691
      1997629.28       663022.96      1997555.78       666224.57
      1999150.55       670225.52      2001063.94       672651.23
#Sta/Elev= 30
       0  930.97  1927.4 1079.53  3010.3  763.47  3960.7  834.42  4626.5 1025.34
  5646.9  837.15  6772.9 1038.69    7649  846.76  8985.4  987.39  9478.9  894.96
 10268.1 1003.61 10797.6  849.67 11310.4  911.79 11626.5  842.59 12145.5  983.16
 13400.7  616.49 14018.5  684.79 15051.9   992.5 16025.8   694.5 17008.4  793.97
 18346.6  671.75 21881.3  685.17 23494.4  539.84   27081  471.9427170.17  449.63
 27379.9  471.95 28276.4  769.49 29378.6  631.72 30340.2  628.97 31404.8  854.76
#Mann= 3 , 0 , 0
       0      .1       0   27081    .035       0 27379.9      .1       0
Bank Sta=27081,27379.9
XS Rating Curve= 0 ,0
Exp/Cntr=0.3,0.1

Type RM Length L Ch R = 1 ,65513.48,3143.7,2584.4,2379.7
XS GIS Cut Line= 6
1971549.61863933 654238.039323671984320.86454094662636.497613336
1993432.25855297666851.5123511011995947.14431988668900.076763601
1998027.47445826671116.412523446      1998849.93       671326.65
#Sta/Elev= 30
       0  660.08  1082.5  699.96  2115.5  631.29  3316.7  734.29  4062.6  608.31
  5309.6  845.99  6085.3  647.85    6579  578.06  7689.2  724.23  9149.2  543.61
 10585.5  629.39 11579.1  791.02 12611.1  717.16 13667.6  903.29 14528.6   793.1
 15079.6  912.37 16010.5  684.94 17461.9  658.03 20373.6  496.91 21359.8  566.77
   22660  514.56 23158.5  555.45 23809.3  503.77 25413.8     572 27052.1  481.32
 28587.5  516.53 30062.5  471.7230261.51     447 30364.1  471.72   32465  663.58
#Mann= 3 , 0 , 0
       0      .1       0 30062.5    .035       0 30364.1      .1       0
#XS Ineff= 2 , 0
        28569.15  515.29
Permanent Ineff=
       F       F
Bank Sta=30062.5,30364.1
XS Rating Curve= 0 ,0
Exp/Cntr=0.3,0.1

Type RM Length L Ch R = 1 ,62929.10,813.9,765.1,751.7
BEGIN DESCRIPTION:
19619.32
END DESCRIPTION:
XS GIS Cut Line= 6
      1992751.15       672951.51      1993269.16       673015.71
      1993850.63       672442.98      1994834.05       672068.49
       1997498.9        671811.8      1998204.54       671533.59
#Sta/Elev= 30
       0   609.5   360.7  664.87   509.3  676.36    1003  610.84  1202.9   592.3
    1703  586.12  2642.7   538.4    2673  533.92  2683.1  493.61  2690.7  476.71
  2698.3  470.81  2738.4  447.83  2770.6  445.23    3006  470.75  3132.6  493.85
  3403.8  489.29  3434.2  476.96  3472.1  481.99  3489.8   471.6  3558.1  486.38
  3593.3  477.25  3613.8  487.04  3993.2  484.75  4003.3  478.49    4687  516.78
  5049.7   556.5    5271  563.65  5461.5  556.48  5735.5  600.12  5835.6   601.8
#Mann= 3 , 0 , 0
       0      .1       0  2698.3    .035       0    3006      .1       0
Bank Sta=2698.3,3006
XS Rating Curve= 0 ,0
Exp/Cntr=0.5,0.3

Type RM Length L Ch R = 1 ,62164.01,60.2,61.5,61.1
BEGIN DESCRIPTION:
19376.14
END DESCRIPTION:
XS GIS Cut Line= 6
      1993752.34       673604.42      1994401.67       673250.41
1995515.07957397672740.215069996      1996567.56       672436.16
      1997564.17       672078.54      1998256.75       671594.22
#Sta/Elev= 30
       0  608.18   165.1  578.71   451.9  547.71   667.6   545.5   945.3  526.78
    1111  526.71  1321.1   544.9    1438  535.78  1492.3  549.89  1761.6  545.83
  1938.6  528.51  1964.1  491.14    1969471.4267 1977.48  458.99 2013.35  450.16
 2166.65  452.92  2219.9  471.62  2357.2  489.84  3369.7  490.27  3515.3  507.93
  3645.1  535.03  3873.9  557.61  4168.8  558.87  4426.5  538.45  4467.6  526.73
  4531.2  547.21  4598.8  550.87  4620.1  563.14  4788.6  589.84  4965.1  590.99
#Mann= 3 , 0 , 0
       0      .1       0    1969    .035       0  2219.9      .1       0
Bank Sta=1969,2219.9
XS Rating Curve= 0 ,0
Exp/Cntr=0.5,0.3

Type RM Length L Ch R = 3 ,62124.48,,,
Bridge Culvert--1,0,-1,-1, 0
Deck Dist Width WeirC Skew NumUp NumDn MinLoCord MaxHiCord MaxSubmerge Is_Ogee
12,19,2.61,0, 23, 23, , , 0.95, 0, 0,0,,
    1900    1975 1981.03 1982.31 1982.32 2001.94 2046.05 2113.03 2157.872179.289
 2179.29 2268.22 2290.84 2311.36 2323.64 2367.48 2378.45    2400 2419.34 2439.93
2439.931  2787.5  2852.6
   534.4  533.01  531.23  532.56  532.57  553.03  561.29  561.34   553.1  530.73
  530.73  529.88  529.63     530  522.33  520.13  516.11  516.07  516.03  512.05
  512.05  494.92  490.46
                  530.18  525.87  531.89  531.89  532.24  532.29  532.29  529.68
     511  510.15  509.85  510.22  502.45  500.35  506.28  506.28  506.28   502.3
                        
    1475    1950 1970.13 1970.71 1970.72 1976.94 2021.05 2088.03 2132.872154.769
 2154.77 2243.22 2265.84 2286.36 2298.64 2342.48 2353.45    2375 2394.34 2414.93
2414.931  2762.5  2847.5
   534.4  533.01  531.05  532.92  532.93  553.03  561.29  561.34   553.1  530.73
  530.73  529.88  529.63     530  522.33  520.13  516.11  516.07  516.03  512.05
  512.05  494.92  491.06
                     530   525.2  531.89  531.89  532.24  532.29  532.29  529.68
     511  510.15  509.85  510.22  502.45  500.35  506.28  506.28  506.28   502.3
                        
Pier Skew, UpSta & Num, DnSta & Num=  ,2179.29, 2 ,2154.77, 2 , 0 , 0 , 0 ,,
       3       3
  453.72     511
       3       3
  453.72  510.91
Pier Skew, UpSta & Num, DnSta & Num=  ,2291.11, 2 ,2266.11, 2 , 0 , 0 , 0 ,,
       1       1
  474.76  509.85
       1       1
  474.76  509.85
Pier Skew, UpSta & Num, DnSta & Num=  ,2311.36, 2 ,2286.36, 2 , 0 , 0 , 0 ,,
       1       1
  474.76  509.85
       1       1
  474.76  509.85
Pier Skew, UpSta & Num, DnSta & Num=  ,2378.45, 2 ,2353.45, 2 , 0 , 0 , 0 ,,
       1       1
  487.87  506.28
       1       1
  487.87  506.28
Pier Skew, UpSta & Num, DnSta & Num=  ,2400.4, 2 ,2375.4, 2 , 0 , 0 , 0 ,,
       1       1
  487.87  506.28
       1       1
  487.87  506.28
Pier Skew, UpSta & Num, DnSta & Num=  ,2419.34, 2 ,2394.34, 2 , 0 , 0 , 0 ,,
       1       1
  490.71  506.28
       1       1
  490.71  506.28
BR Coef=-1 , 0 , 0 ,, 0 ,,,0.8,-1,,0,
WSPro=,,,, 1 ,,,, 0 ,,,, 0 ,,,,-1 ,-1 ,-1 , 0 , 0 , 0 , 0 , 0
BC Design=,, 0 ,, 0 ,,,,,,
BC HTab HWMax=590
BC Use User HTab Curves=0
BC User HTab FreeFlow(D)= 0

Type RM Length L Ch R = 1 ,62102.48,426.9,427.9,429.5
XS GIS Cut Line= 6
1993779.87721611673634.9062702461994424.20600128673283.747082328
1995537.78142461672797.1336706521996581.30836507 672481.12915597
1997581.80277282672114.7509221471998272.28482887671633.292345649
#Sta/Elev= 30
       0  605.56   171.4  573.32   435.8  546.92   710.9  540.61   931.6  526.12
  1101.4  526.84  1288.8  543.62  1405.3  538.04  1481.9  548.86  1756.6  541.99
  1929.3  519.96    1937  516.43  1961.3  470.38 1965.66  461.81 1984.62  452.46
 2006.35  450.16 2159.65  452.92  2211.7  470.38  2374.2  489.35  3333.1  488.72
  3487.5  504.49    3637  539.09  3862.9  558.62  4205.3  554.11  4401.1   527.7
  4425.1  517.99  4513.5  544.37  4708.6  578.03  4790.8  587.57  4947.2  585.54
#Mann= 3 , 0 , 0
       0      .1       0  1961.3    .035       0  2211.7      .1       0
Bank Sta=1961.3,2211.7
XS Rating Curve= 0 ,0
Exp/Cntr(USF)=0,0
Exp/Cntr=0.5,0.3

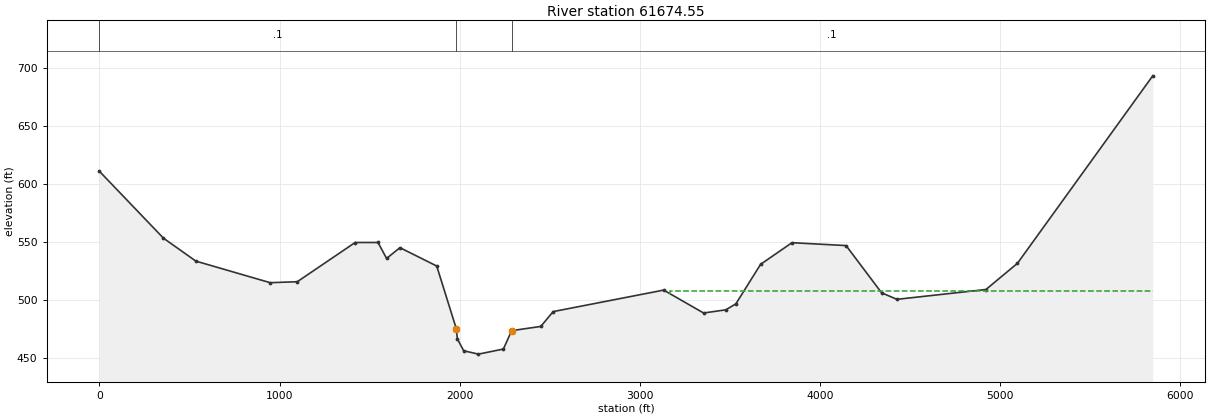
Type RM Length L Ch R = 1 ,61674.55,1241.7,1275.8,1243
BEGIN DESCRIPTION:
19233.20
END DESCRIPTION:
XS GIS Cut Line= 6
      1993774.68       673750.06      1994537.56       673631.04
      1995208.67       673367.12      1996800.56       672801.91
      1997615.92       672383.67      1999313.33       671968.24
#Sta/Elev= 30
       0   610.9   356.1  553.09   535.8  533.33   948.3  514.71  1098.8  515.57
  1419.7  549.38  1546.7   549.4  1594.3  535.65  1668.5  544.92  1872.5   529.1
  1981.1  475.05 1987.09  466.23  2022.3  455.99  2103.9  453.09 2242.55  457.48
  2288.4  473.34    2450  476.98    2519  489.79    3132  508.33  3353.6  488.58
    3477  491.29  3532.9  496.49  3670.1  530.56  3844.1  549.22  4144.4  546.74
  4341.6     506  4426.6  500.36  4920.7  508.84  5095.7  531.45  5846.5  693.18
#Mann= 3 , 0 , 0
       0      .1       0  1981.1    .035       0  2288.4      .1       0
#XS Ineff= 2 , 0
                         3167.11          507.93
Permanent Ineff=
       F       F
Bank Sta=1981.1,2288.4
XS Rating Curve= 0 ,0
Exp/Cntr=0.3,0.1