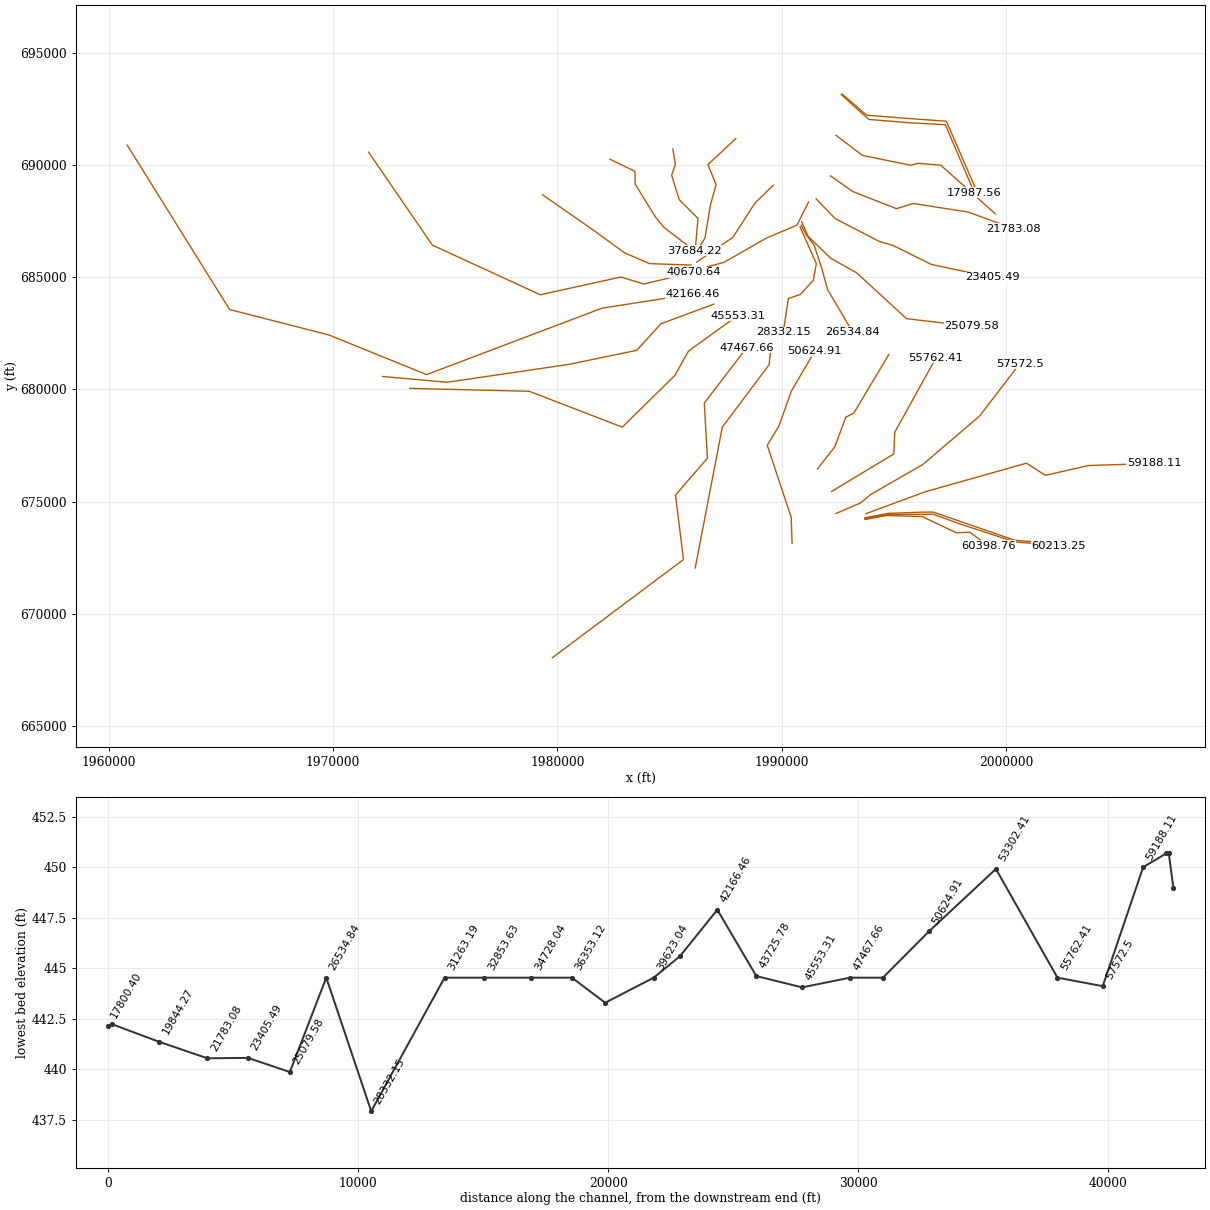
HEC-RAS study CaneyFork.prj: Caney Fork River- Smith County

--- CaneyFork.g02 (geometry) --- (continued)

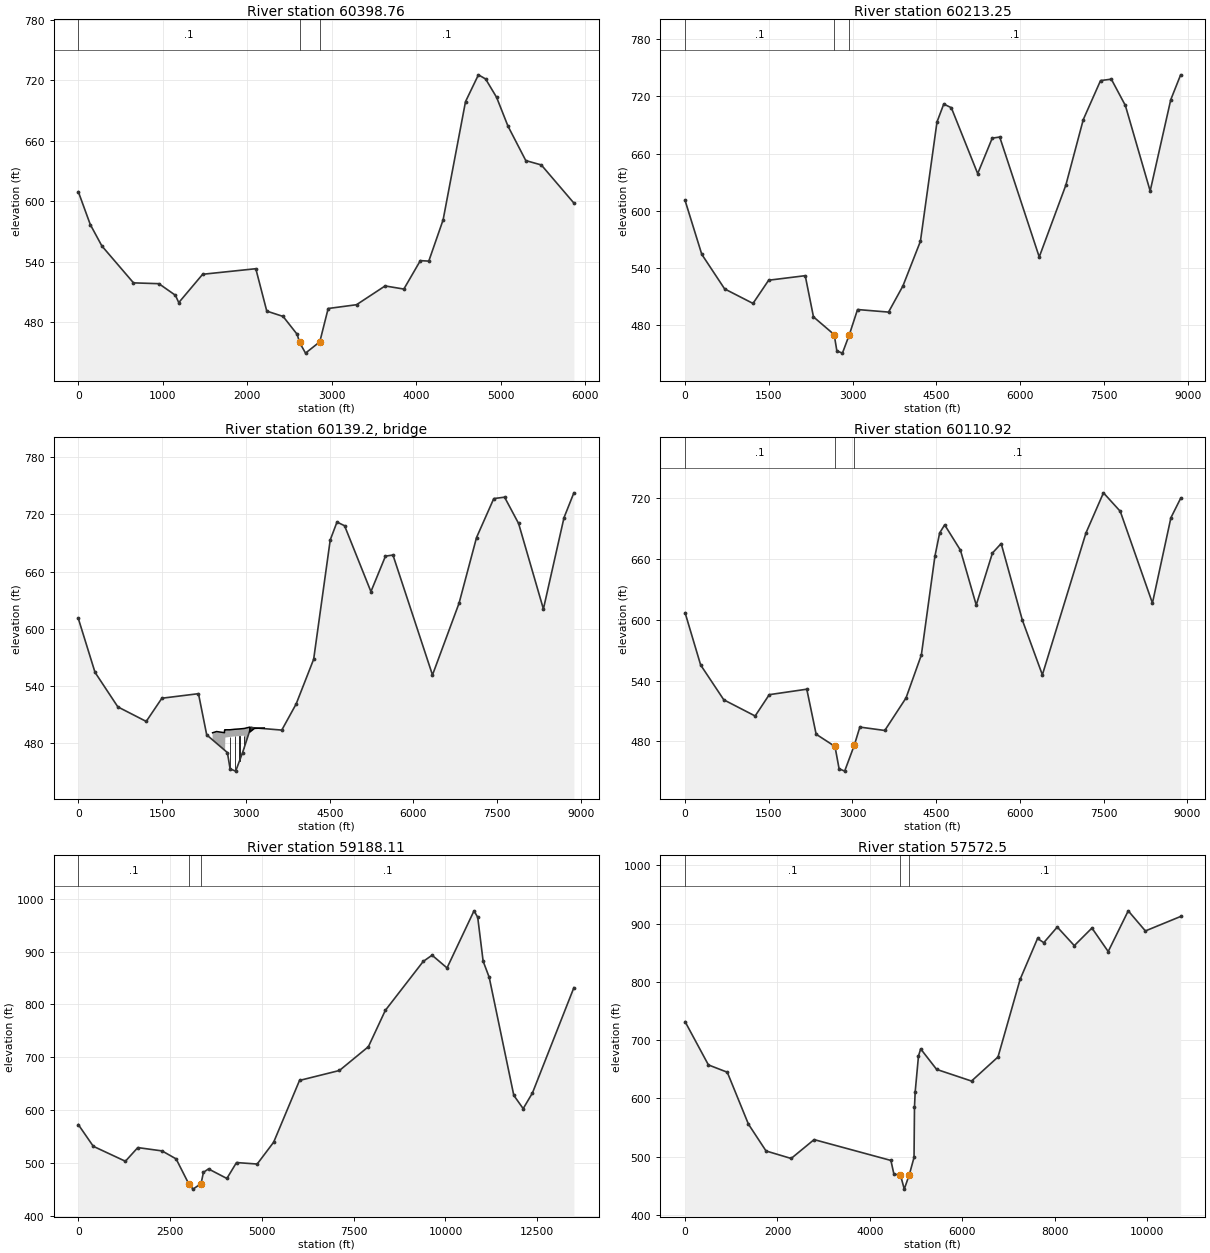
Type RM Length L Ch R = 1 ,60398.76,113.4,185.5,277.1
BEGIN DESCRIPTION:
18843.96
END DESCRIPTION:
XS GIS Cut Line= 6
      1993727.33        674212.5      1994680.87       674390.22
  1996262.187807674342.226877199      1997778.05       673621.94
      1998388.06       673642.98      1999209.16       673037.55
#Sta/Elev= 30
       0  609.35   141.6  576.72     279  555.42   652.8  518.78   952.9  517.97
  1148.3  506.48  1188.4  499.16    1471  527.31  2099.8  532.84  2229.6  490.73
  2422.7  485.42 2589.11  467.64 2617.51  459.59    2688  448.96 2856.86  460.19
    2956   493.3  3291.3  497.06  3629.6  515.72  3851.3  512.62  4046.5  540.87
  4146.4  540.39  4315.9  581.39    4581  698.89  4733.6   725.5  4818.7  721.38
    4949  703.08  5083.1  674.55    5294  640.29  5477.6  635.95  5862.9  598.08
#Mann= 3 , 0 , 0
       0      .1       0 2617.51    .035       0 2856.86      .1       0
Bank Sta=2617.51,2856.86
XS Rating Curve= 0 ,0
Exp/Cntr=0.5,0.3

Type RM Length L Ch R = 1 ,60213.25,98.6,102.3,100.2
BEGIN DESCRIPTION:
18775.39
END DESCRIPTION:
XS GIS Cut Line= 6
      1993699.93        674247.51994732.34832747  674434.3331228
1996747.53709946674444.817807001      1998024.93       673987.58
      2000384.35       673216.72      2002345.02       673046.43
#Sta/Elev= 30
       0 610.771 298.915 554.291 707.952 518.0431215.914 502.8121495.926 527.143
2150.956 531.9062298.463 488.7182669.026 470.125 2717.19  453.03 2816.96  450.69
 2940.78 470.0993087.333 496.4043642.298 493.7213899.865 521.1524213.194 568.036
 4509.74 693.1114630.722 711.8934766.406 708.0365238.263 638.9285498.638 676.147
 5632.77 677.2936340.252 551.5216816.291 626.8537128.943 695.6757437.601 736.514
7630.826 737.9867881.767 710.4188325.933 620.7038694.816 716.4868871.432 742.543
#Mann= 3 , 0 , 0
       0      .1       02669.026    .035       0 2940.78      .1       0
Bank Sta=2669.026,2940.78
XS Rating Curve= 0 ,0
Exp/Cntr=0.5,0.3

Type RM Length L Ch R = 3 ,60139.2 ,,,
Bridge Culvert--1,0,-1,-1, 0
Deck Dist Width WeirC Skew NumUp NumDn MinLoCord MaxHiCord MaxSubmerge Is_Ogee
28,29,2.61,0, 15, 15, , , 0.95, 0, 0,0,,
 2403.47    2475 2616.62 2616.63 2622.26 2627.72 2631.74 2713.72 2799.52  2885.4
 2970.49 3071.163071.161 3153.73  3329.3
  490.93  492.22     491  492.95  494.05  494.05  494.05  494.05  494.59  494.94
  495.43  496.86   491.7   495.5  495.92
                                          452.72  485.88  486.55  487.09  487.44
  487.93
    2300    2325    2525 2683.21 2683.21 2688.71 2695.02 2777.31 2862.09  2946.5
 3032.09 3127.223127.221 3203.73  3979.3
  490.93  492.92  492.22     491  494.41  495.47  495.47  495.47   494.6  495.03
  495.45  495.93   491.7   495.5  495.92
                                                  486.51  486.79   487.1  487.53
  487.95
Pier Skew, UpSta & Num, DnSta & Num=  ,2713.72, 2 ,2777.31, 2 , 2 , 2 , 0 ,,
      .4      .6
  470.11  486.55
      .4      .6
  470.11  486.79
Pier Skew, UpSta & Num, DnSta & Num=  ,2799.52, 2 ,2862.09, 2 , 2 , 2 , 0 ,,
      .4      .6
  450.63  487.09
      .4      .6
  450.63   487.1
Pier Skew, UpSta & Num, DnSta & Num=  ,2885.4, 2 ,2946.5, 2 , 2 , 2 , 0 ,,
      .4      .6
  453.87  487.44
      .4      .6
  453.87  487.53
Pier Skew, UpSta & Num, DnSta & Num=  ,2969.49, 2 ,3032.09, 2 , 2 , 2 , 0 ,,
      .4      .6
   467.4  487.93
      .4      .6
   467.4  487.95
BR Coef=-1 , 0 , 0 ,, 0 ,,,0.8,0,,0,
WSPro=,,,, 1 ,,,, 0 ,,,, 0 ,,,,-1 ,-1 ,-1 , 0 , 0 , 0 , 0 , 0
BC Design=,, 0 ,, 0 ,,,,,,
BC HTab HWMax=600
BC Use User HTab Curves=0
BC User HTab FreeFlow(D)= 0

Type RM Length L Ch R = 1 ,60110.92,921.8,922.8,879.3
XS GIS Cut Line= 6
1993695.15939903674283.8345869961994734.41239648674484.151886339
 1996326.6781092674540.6516374361996752.04323867 674541.03210714
2000394.73802469673287.5666925752002340.28879151673128.095318245
#Sta/Elev= 30
       0 606.793 278.949 555.297  693.95 520.9691255.661 505.031 1508.32 526.042
2181.243 531.4362348.849  487.072686.539 474.997 2760.19  453.03 2859.96  450.69
3033.427 476.3453132.033   494.13578.847 490.7553959.564 522.7944234.527 565.148
4477.387 662.3984562.367 685.4314652.258 693.4054935.152 668.4185218.046 614.411
5508.381 665.622 5664.86 674.9896042.934 599.7896403.372 545.5967184.522 685.415
 7498.07 724.9727799.076 706.7828376.004 616.2938707.111 700.4188881.415 719.578
#Mann= 3 , 0 , 0
       0      .1       02686.539    .035       03033.427      .1       0
Bank Sta=2686.539,3033.427
XS Rating Curve= 0 ,0
Exp/Cntr(USF)=0,0
Exp/Cntr=0.5,0.3

Type RM Length L Ch R = 1 ,59188.11,1292,1615.6,1754.8
BEGIN DESCRIPTION:
18473.60
END DESCRIPTION:
XS GIS Cut Line= 6
      1993752.94        674471.31996395.67756006675445.466062076
      2000910.27       676719.53      2001749.79       676178.82
       2003684.2       676615.63      2006599.02       676709.57
#Sta/Elev= 30
       0  572.36   407.9  531.19  1282.1  502.84  1620.1  528.76  2280.7  522.44
  2663.7  507.32 3004.27  460.53  3124.2  450.01 3342.72  460.45  3407.9  481.86
  3545.7  488.32    4046  470.23  4308.3  500.39  4871.5  497.56  5321.1  539.07
  6024.6  656.04  7111.4  674.89  7900.5     720  8361.4  788.84  9393.5  881.62
    9635  893.41   10042  869.29 10776.9  977.54 10877.8   965.3 11025.4  882.07
 11190.5  851.59 11860.9  627.71   12116   602.6 12368.3  632.28 13496.7  831.88
#Mann= 3 , 0 , 0
       0      .1       0 3004.27    .035       0 3342.72      .1       0
Bank Sta=3004.27,3342.72
XS Rating Curve= 0 ,0
Exp/Cntr=0.3,0.1

Type RM Length L Ch R = 1 ,57572.5 ,1665.9,1810.1,1959.5
BEGIN DESCRIPTION:
17986.65
END DESCRIPTION:
XS GIS Cut Line= 6
       1992412.6       674476.31      1993521.95       674952.96
      1993961.08       675321.551996296.51536002676666.726841486
      1998818.21       678816.28      2000604.69       681142.87
#Sta/Elev= 30
       0  731.69     505  657.38   913.1  644.85  1370.6  555.76    1752  509.65
  2295.7  496.75  2792.3  529.15  4454.4  493.36  4519.9  469.57    4660  468.72
  4743.5  444.12  4853.4  469.16  4954.8   498.5  4964.6  584.74  4979.4  610.88
  5051.1   672.7  5098.7   684.9  5443.5  649.71  6198.8  629.68    6772  671.04
  7250.2  804.24  7628.2  874.52  7762.8  867.29  8054.7  894.14  8423.5  862.19
  8804.9  892.41  9156.8  852.06  9590.4  921.96  9961.6  887.44 10724.4  912.28
#Mann= 3 , 0 , 0
       0      .1       0    4660     .05       0  4853.4      .1       0
Bank Sta=4660,4853.4
XS Rating Curve= 0 ,0
Exp/Cntr=0.3,0.1

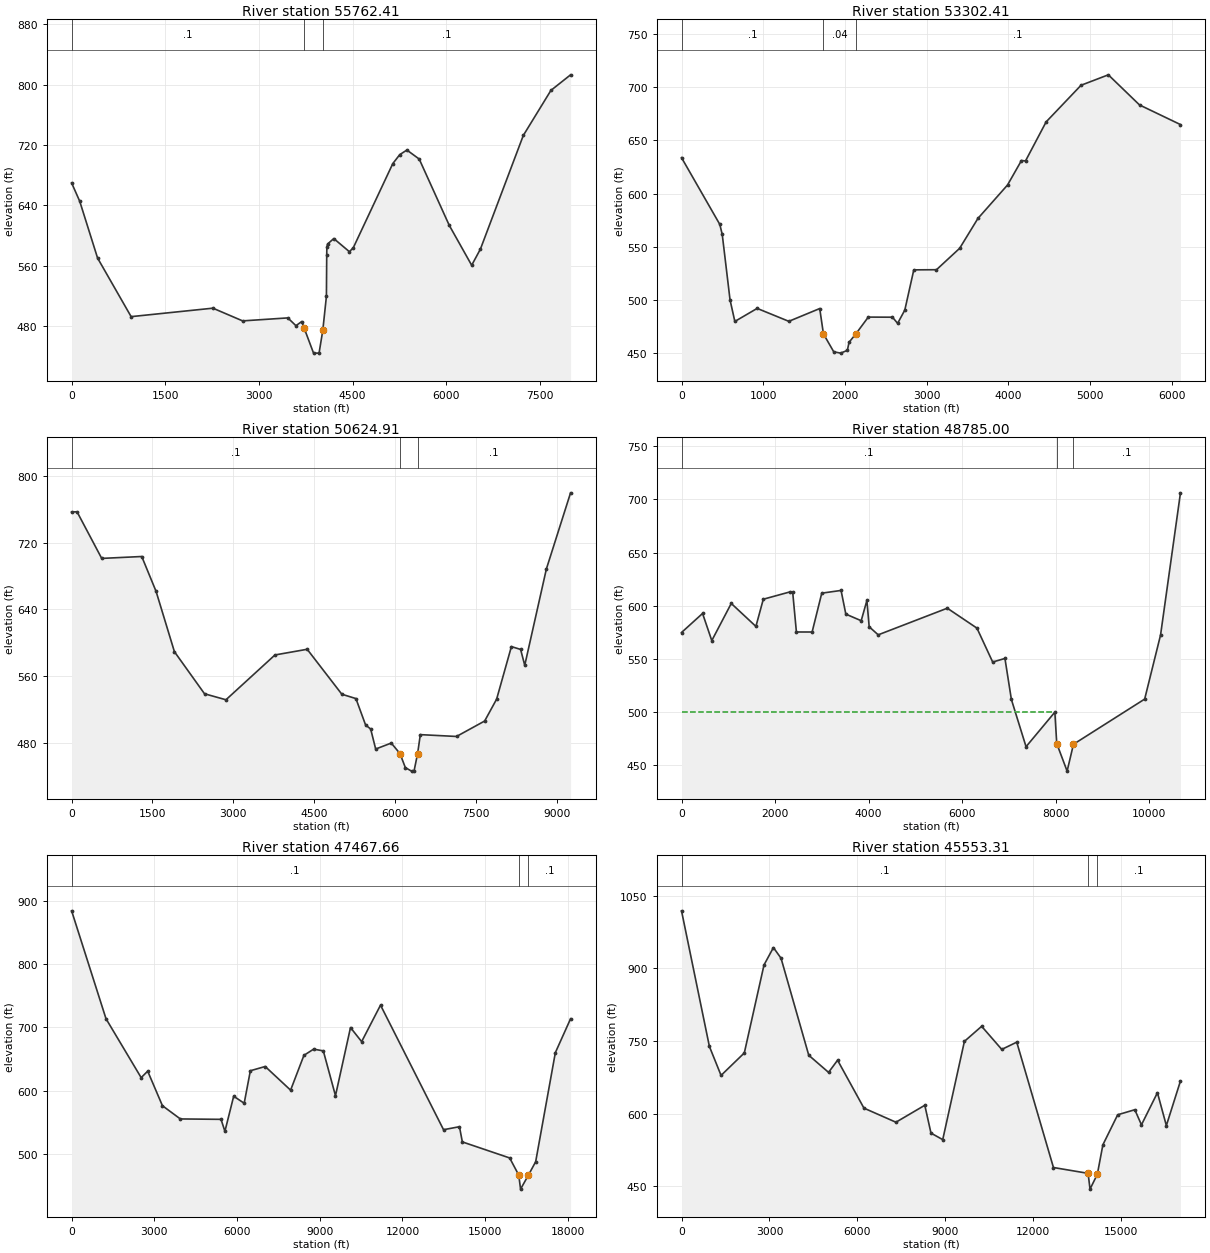
Type RM Length L Ch R = 1 ,55762.41,2532.5,2460,2368.5
XS GIS Cut Line= 4
      1992223.05       675460.751994997.52120022677131.630171987
      1995036.46       678092.01      1996873.19       681408.32
#Sta/Elev= 30
       0  669.84   130.1  645.48     416  570.34   953.1  492.83  2262.9  504.03
  2738.6  487.21  3462.7  491.16  3592.8  480.84  3685.4  486.35  3726.1  477.27
 3874.73  444.54 3962.94  444.55 4022.57  474.53  4080.7  519.67  4085.7   574.4
  4088.2  585.03  4100.7     589  4198.5  596.18  4449.5  578.72  4512.4  584.22
    5144  695.38  5255.5  707.26  5369.8   713.3    5567  701.38  6047.4  613.77
  6407.2  560.83  6547.2  582.25  7234.2  732.65    7676  792.24  7990.9  812.86
#Mann= 3 , 0 , 0
       0      .1       0  3726.1    .045       0 4022.57      .1       0
Bank Sta=3726.1,4022.57
XS Rating Curve= 0 ,0
Exp/Cntr=0.3,0.1

Type RM Length L Ch R = 1 ,53302.41,2668.7,2677.5,2686.9
BEGIN DESCRIPTION:
16626.80
END DESCRIPTION:
XS GIS Cut Line= 5
1991589.42382875676458.7653711021992369.21211441677455.414628898
1992852.93102823678766.569027865      1993210.03       678944.96
      1994773.22       681558.12
#Sta/Elev= 30
       0  633.77   468.7  570.97   498.4  561.56   593.9  500.03   652.7  479.72
   925.8  491.99  1313.4  479.83  1691.6  491.85  1737.1  468.03  1863.2  451.15
  1948.1  449.92 2029.96  452.53 2050.57  460.11  2134.1  468.03    2286  483.81
  2581.8  483.71  2645.4  477.92  2733.1  490.42  2843.1  528.23  3120.9  528.37
  3404.5  548.51  3627.8  576.57  3990.4  608.04  4160.9  631.06  4210.4  630.66
  4462.8  667.38    4890  701.84  5224.2  711.66  5605.9  683.34  6107.2  664.87
#Mann= 3 , 0 , 0
       0      .1       0  1737.1     .04       0  2134.1      .1       0
Bank Sta=1737.1,2134.1
XS Rating Curve= 0 ,0
Exp/Cntr=0.3,0.1

Type RM Length L Ch R = 1 ,50624.91,1919.9,1839.9,1769.1
BEGIN DESCRIPTION:
15807.77
END DESCRIPTION:
XS GIS Cut Line= 6
      1990460.85       673152.28       1990420.7       674309.29
      1989353.86       677519.031989875.06372574678377.252160399
1990427.29646832679929.412216497      1991471.12       681706.82
#Sta/Elev= 30
       0  756.57   100.7  756.74   558.4  701.04  1301.1  703.31  1567.2  661.59
    1907  589.58  2465.6  539.27  2863.4   532.1  3772.3  585.65  4370.3  592.44
  5013.2  538.73  5274.4  533.54  5453.8  501.98  5548.4  497.11    5641  473.23
  5930.5  480.38  6092.4  467.72  6191.1  451.07  6305.9  446.83  6354.3  447.47
  6418.8  467.72  6469.3  490.44  7140.6  488.25  7662.8  506.72  7884.9  532.88
  8158.9  595.65  8329.9  592.26  8406.4  573.31  8808.2   688.5  9256.5  779.41
#Mann= 3 , 0 , 0
       0      .1       0  6092.4    .035       0  6418.8      .1       0
Bank Sta=6092.4,6418.8
XS Rating Curve= 0 ,0
Exp/Cntr=0.3,0.1

Type RM Length L Ch R = 1 ,48785.00,1317.7,1317.3,1313.3
XS GIS Cut Line= 4
      1986140.37       672053.65      1987350.31       678326.05
      1989436.62       681104.41      1989526.75       681904.01
#Sta/Elev= 30
       0  574.83   449.9  592.74   647.1  567.23  1063.5  602.14  1590.5  580.56
  1748.4  606.12  2320.4  613.03  2377.3  612.52  2456.2  575.32  2792.3  575.31
  2998.5  611.83  3411.1  614.38  3512.8  592.13  3841.3  585.92  3963.5  604.98
  4011.9  580.23  4205.1  572.65  5682.1  597.69  6316.1  578.95  6652.4  547.08
  6914.7  550.45  7052.1  511.95  7365.8  467.49  7981.6  499.98  8022.2  470.48
 8243.95  444.54  8379.4  469.78  9901.8  512.25 10241.5  572.46 10667.2  706.13
#Mann= 3 , 0 , 0
       0      .1       0  8022.2    .035       0  8379.4      .1       0
#XS Ineff= 2 , 0
         7981.23  499.98
Permanent Ineff=
       F       F
Bank Sta=8022.2,8379.4
XS Rating Curve= 0 ,0
Exp/Cntr=0.3,0.1

Type RM Length L Ch R = 1 ,47467.66,1886.3,1914.4,1980.5
BEGIN DESCRIPTION:
14857.42
END DESCRIPTION:
XS GIS Cut Line= 6
1979772.62082924668057.8368607941985618.17771665672428.004044132
      1985262.81       675300.72      1986685.82       676942.43
      1986545.92       679395.72      1988443.09       681868.92
#Sta/Elev= 30
       0  884.24  1247.8  713.73    2523  620.69  2759.9  630.92  3294.3  576.34
  3944.1  555.43  5420.1  554.79    5561  535.89  5879.1  591.32  6260.2  580.21
  6484.2  631.59  7022.3  638.28  7943.8   600.9  8427.2  655.91  8780.2  665.73
  9130.7  662.93    9572  592.15 10116.8  699.79 10520.9  677.55 11205.7  735.23
 13491.6  538.41 14069.3  543.16 14174.1  519.14 15890.9  493.79 16219.3  466.81
16286.25  444.54 16572.4  466.81   16834  487.85   17548   660.2 18099.7   713.7
#Mann= 3 , 0 , 0
       0      .1       0 16219.3    .035       0 16572.4      .1       0
Bank Sta=16219.3,16572.4
XS Rating Curve= 0 ,0
Exp/Cntr=0.3,0.1

Type RM Length L Ch R = 1 ,45553.31,1887.6,1827.5,1788.3
BEGIN DESCRIPTION:
14274.22
END DESCRIPTION:
XS GIS Cut Line= 6
      1973413.14       680048.95      1978737.88       679921.31
      1982888.56       678324.39      1985238.82       680632.07
      1985840.91       681709.33      1988031.57       683288.38
#Sta/Elev= 30
       0 1018.48   951.2  738.48  1348.8  678.78  2141.8  725.16  2814.2  906.89
  3134.3  942.63  3394.4  920.61  4339.7  720.38  5014.9  685.04  5322.5  710.15
  6222.2  611.22  7312.6  582.15  8297.2  617.13  8508.1  559.71  8908.9  546.22
  9648.2  749.04 10236.3  780.14 10921.9  732.42 11433.3  747.42 12685.1  488.67
 13867.6  476.62 13932.2  444.06 14181.7   474.7 14371.4  535.58 14875.9  597.52
 15460.1  607.94 15686.7  576.75 16231.6  643.09 16535.9  575.26 17017.1  667.32
#Mann= 3 , 0 , 0
       0      .1       0 13867.6    .035       0 14181.7      .1       0
Bank Sta=13867.6,14181.7
XS Rating Curve= 0 ,0
Exp/Cntr=0.3,0.1

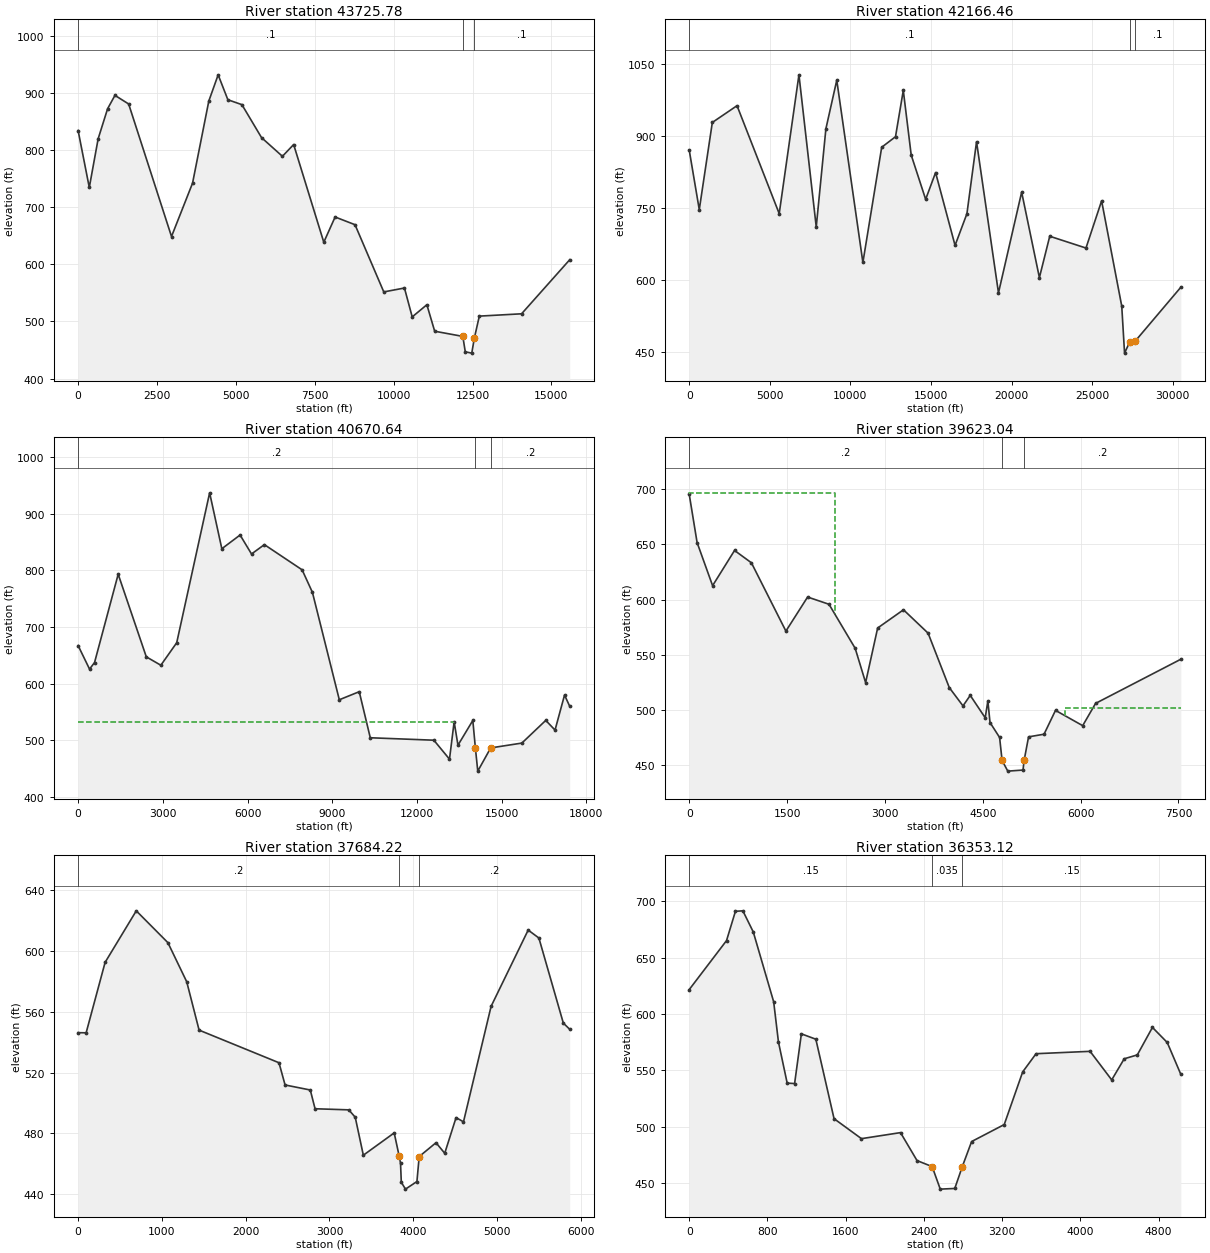
Type RM Length L Ch R = 1 ,43725.78,1896.7,1559.3,1493.8
XS GIS Cut Line= 6
      1972201.53       680579.03      1975085.88       680323.84
      1980484.03       681114.071983538.17171434 681744.55291456
1984609.40262853682926.305599188       1986967.2       683800.21
#Sta/Elev= 30
       0  834.08   353.9   734.5     635  819.76   933.7  872.24  1167.1   895.7
  1601.3  880.62  2959.5  648.69  3626.5  742.07  4141.9  885.81  4437.6  931.64
  4745.8  888.01  5190.5  879.45  5813.1  821.71    6474  789.07  6830.3  809.64
  7785.4  638.68  8144.2  682.84  8775.1  669.35  9686.4  551.74 10341.4  558.57
 10587.5     508 11052.1   529.3 11299.7  482.95 12191.4   473.9 12269.2  446.89
12474.75  444.62 12557.5   471.1 12714.5  509.38 14053.7  513.45 15579.4  608.09
#Mann= 3 , 0 , 0
       0      .1       0 12191.4    .035       0 12557.5      .1       0
Bank Sta=12191.4,12557.5
XS Rating Curve= 0 ,0
Exp/Cntr=0.3,0.1

Type RM Length L Ch R = 1 ,42166.46,1661.7,1495.8,1288.8
BEGIN DESCRIPTION:
13144.98
END DESCRIPTION:
XS GIS Cut Line= 6
      1960814.12       690884.11      1965382.51       683560.99
      1969809.43       682427.32      1974167.64        680663.1
      1981985.32       683620.73      1986032.69       684250.52
#Sta/Elev= 30
       0  870.13   623.2  746.38  1433.5  927.68  2965.7  962.57  5582.9  738.04
  6807.3 1026.74  7880.6  710.39  8479.4  914.53  9154.1 1015.49 10774.8  636.41
 11941.3  876.05 12798.1  898.01 13281.5   994.3 13772.3  859.93   14669  767.76
 15284.9  823.47 16493.7  671.94 17229.8  737.92 17826.1   887.6 19187.5  573.26
 20625.3   782.7   21726  604.98 22368.1     691   24616  666.48 25586.3  764.61
 26835.6  545.66 27009.6   447.927321.93   470.427672.03   472.9 30501.6  584.95
#Mann= 3 , 0 , 0
       0      .1       027321.93    .035       027672.03      .1       0
Bank Sta=27321.93,27672.03
XS Rating Curve= 0 ,0
Exp/Cntr=0.3,0.1

Type RM Length L Ch R = 1 ,40670.64,1057,1047.6,1032.5
XS GIS Cut Line= 6
      1971575.33       690568.37      1974422.64       686427.82
      1979233.48       684217.831982823.88372574685007.708365676
1983854.91780669684697.896985142      1986081.16       685227.15
#Sta/Elev= 30
       0   667.2   404.5  625.67   581.4  637.27  1418.9  793.14  2414.5  647.32
  2929.8  632.51  3491.6  672.23  4657.4  936.83  5089.5  838.13  5735.7  862.38
  6140.5  828.89  6596.2  845.39  7932.5  800.92  8297.9  761.11  9249.8  571.57
  9955.6  585.81 10346.7  504.49 12598.3  500.19 13151.8  466.71 13316.7  532.72
 13451.6  491.38   13978  535.02 14069.6  486.1614153.25   445.6   14611  486.57
 15715.3  495.11   16561  535.16 16889.6  518.07 17226.3   579.9   17410  559.96
#Mann= 3 , 0 , 0
       0      .2       0 14069.6     .05       0   14611      .2       0
#XS Ineff= 2 , 0
        13320.96  533.17
Permanent Ineff=
       F       F
Bank Sta=14069.6,14611
XS Rating Curve= 0 ,0
Exp/Cntr=0.3,0.1

Type RM Length L Ch R = 1 ,39623.04,2025.5,1938.8,1779.7
XS GIS Cut Line= 5
      1979337.02       688666.83       1981704.4        687021.7
      1982988.14       686086.65 1984099.2322165685605.269348847
      1985952.59       685538.22
#Sta/Elev= 30
       0  695.36   120.8  651.63   358.2  612.58   694.7  644.49   953.2  633.32
  1482.1  571.42  1814.9  602.29  2142.7  595.74  2544.1  555.81    2704  524.76
  2888.6  574.22  3284.5  590.73    3662  569.55  3986.6  520.24    4197  503.65
    4308  513.18  4537.4  492.87  4578.3  508.11    4611   488.6  4758.1  475.06
 4796.24  454.19  4883.7  444.54 5116.94  445.51 5134.34  454.31  5202.2  475.59
  5439.3  477.98  5615.2  499.59  6031.7  485.74  6229.6  505.92  7536.5  545.92
#Mann= 3 , 0 , 0
       0      .2       0 4796.24    .045       0 5134.34      .2       0
#XS Ineff= 2 , 0
         2232.31  696.71 5767.49          501.72
Permanent Ineff=
       F       F
Bank Sta=4796.24,5134.34
XS Rating Curve= 0 ,0
Exp/Cntr=0.3,0.1

Type RM Length L Ch R = 1 ,37684.22,1311.4,1331.1,1342
BEGIN DESCRIPTION:
11729.94
END DESCRIPTION:
XS GIS Cut Line= 6
      1982336.32       690252.69      1983456.59       689713.15
      1983464.51       689145.48      1984373.47       687670.47
      1984758.11        687208.2      1986096.38        686185.8
#Sta/Elev= 30
       0  546.29    95.6  546.21   322.2   592.6     694  626.51  1071.4  605.55
  1296.2   579.8  1443.7  547.98  2397.2   526.5    2470  511.87  2770.9  508.55
  2827.8  496.21  3230.3  495.49  3307.2  490.63  3403.9  465.63  3772.2  480.31
  3831.3  465.13  3847.7   460.4  3857.1   447.8  3906.9   443.3  4043.4   448.3
  4070.6464.7505  4271.3  473.86  4375.3   466.9  4510.5  490.38  4599.2   487.6
  4928.7  563.64  5371.2  613.84  5499.1  608.61  5790.8   552.6  5867.1  548.52
#Mann= 3 , 0 , 0
       0      .2       0  3831.3     .04       0  4070.6      .2       0
Bank Sta=3831.3,4070.6
XS Rating Curve= 0 ,0
Exp/Cntr=0.3,0.1

Type RM Length L Ch R = 1 ,36353.12,1824.2,1625.1,1434.9
XS GIS Cut Line= 6
      1985143.32       690711.82        1985255.       690023.81
      1985091.83       689535.64      1985427.94       688452.77
1986263.78423894687613.524514855      1986137.99       686138.65
#Sta/Elev= 30
       0  621.62   381.4   665.1   472.5   691.1   548.5  691.51   654.9  672.75
   863.4  610.78   912.2  575.17  1001.6   538.6  1077.5  538.23  1146.7  582.34
  1294.6  577.58  1480.8  507.05    1761  489.33  2160.4  494.69  2329.2  469.88
  2483.9  464.53 2566.77  444.54 2715.16  445.13  2792.2  464.53  2887.4  486.76
  3220.8  501.84  3409.6  548.57  3546.3  564.72  4098.7  566.82  4319.8  541.48
  4447.7  560.21  4581.5  563.65  4736.3  588.05  4887.6  574.67  5026.6  546.38
#Mann= 3 , 0 , 0
       0     .15       0  2483.9    .035       0  2792.2     .15       0
Bank Sta=2483.9,2792.2
XS Rating Curve= 0 ,0
Exp/Cntr=0.3,0.1

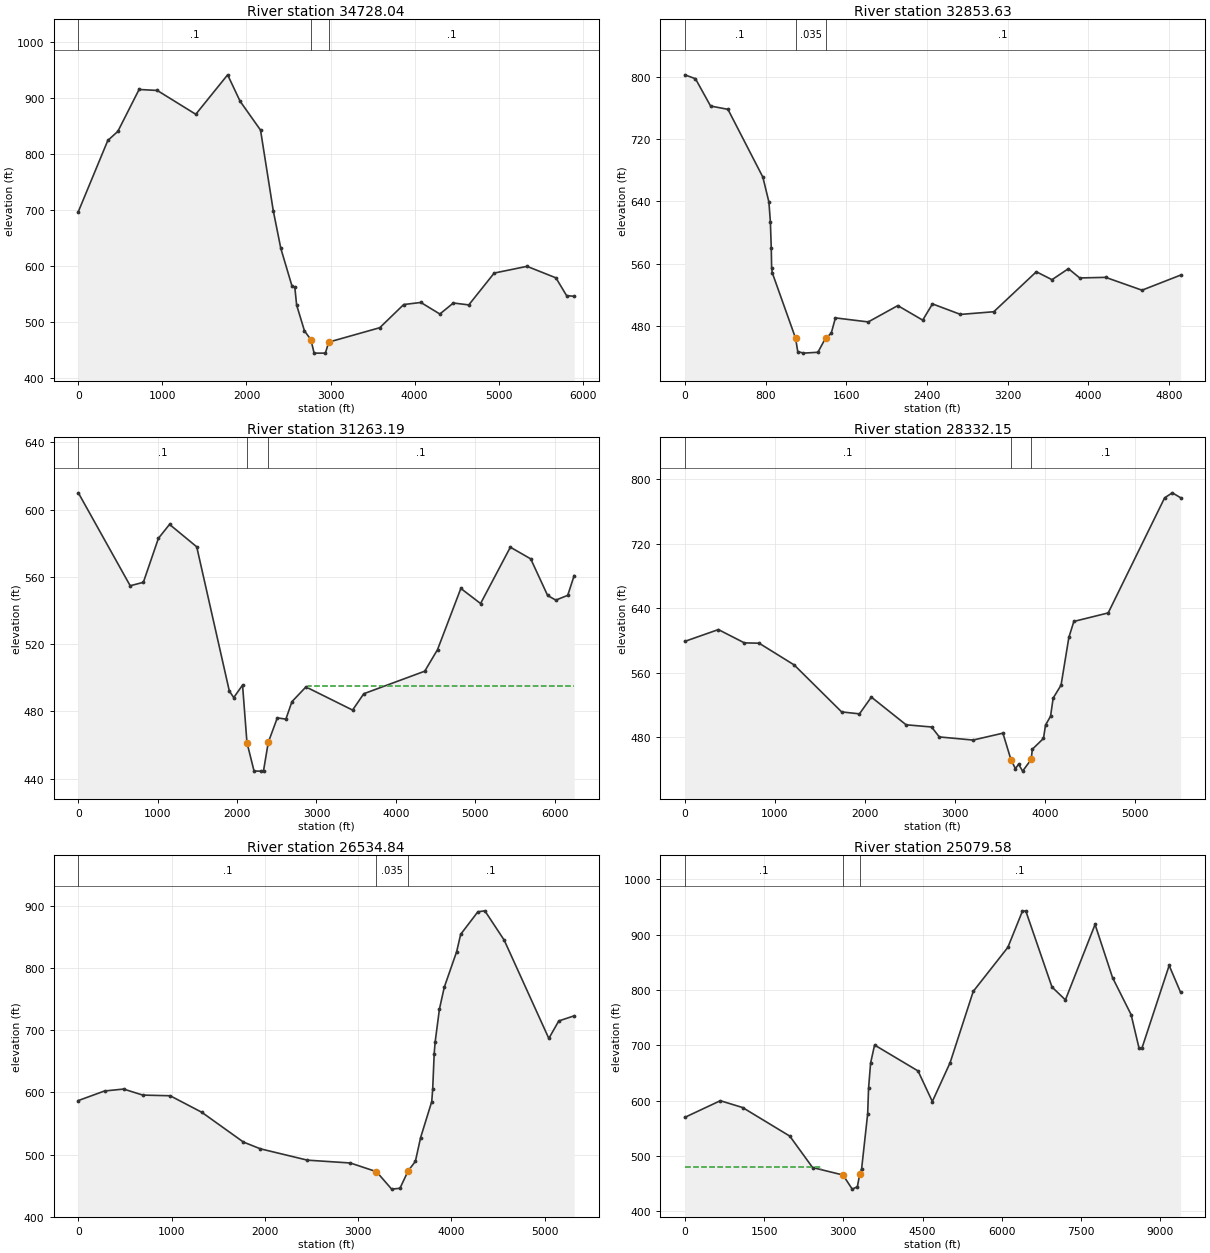
Type RM Length L Ch R = 1 ,34728.04,1946.4,1874.4,1821.1
BEGIN DESCRIPTION:
10887.60
END DESCRIPTION:
XS GIS Cut Line= 6
      1987950.32       691170.96      1986709.21       690012.52
1987073.06993102689122.406274257      1986825.28       688243.15
      1986573.96       686738.01      1986145.15       686073.15
#Sta/Elev= 30
       0     697   350.5  823.98     470  840.23   722.6     915   938.7  913.26
    1397  870.74    1776  941.13  1924.2  894.02  2167.3  842.52  2318.5  698.92
  2408.6  631.42  2540.9  564.58  2575.1  562.05  2596.7   530.4    2690   484.2
  2766.3  468.66 2804.62  444.54 2938.85  444.54  2978.3  464.19  3585.6   489.9
  3870.6  531.25  4074.6  534.96  4300.4  514.33  4461.1     534  4644.4  530.57
  4946.8   587.4  5337.3  599.41  5681.2  578.86  5807.8  547.16    5898  545.97
#Mann= 3 , 0 , 0
       0      .1       0  2766.3    .035       0  2978.3      .1       0
Bank Sta=2766.3,2978.3
XS Rating Curve= 0 ,0
Exp/Cntr=0.3,0.1

Type RM Length L Ch R = 1 ,32853.63,1670.5,1590.4,1491.4
XS GIS Cut Line= 5
      1989624.98       689096.55       1988863.4       688357.61
      1988693.68       688129.13      1987822.35       686775.94
      1986202.52        685672.7
#Sta/Elev= 30
       0  803.12   105.8  798.09   255.6  762.91   427.6  758.67   773.6  671.39
   833.8  639.23   848.3  613.75   857.2  579.61   860.7  554.56   866.9  548.16
  1098.2  463.75 1119.58  446.56 1176.66  444.54 1319.36  445.64  1394.8  463.75
  1451.3  470.02    1493  489.94  1818.5  484.74  2111.4  505.78  2358.2  487.05
  2455.2  507.97  2732.9  494.42  3062.8  497.86  3484.7  549.37  3639.8  539.17
  3803.1  553.35    3915   541.4  4172.1  542.17  4532.1  525.63  4915.1  545.08
#Mann= 3 , 0 , 0
       0      .1       0  1098.2    .035       0  1394.8      .1       0
Bank Sta=1098.2,1394.8
XS Rating Curve= 0 ,0
Exp/Cntr=0.3,0.1

Type RM Length L Ch R = 1 ,31263.19,2954.5,2931,2891.2
BEGIN DESCRIPTION:
9747.548
END DESCRIPTION:
XS GIS Cut Line= 6
      1991194.59       688347.04      1990677.92        687318.7
      1989324.14       686744.77      1987418.98       685659.15
      1986686.21       685461.16      1986082.88       685174.04
#Sta/Elev= 30
       0  609.91   653.4  554.69   819.1  556.74  1009.1  582.91    1149  591.15
  1491.3  577.83  1902.1  492.12  1957.6  488.24  2068.6  495.66 2124.16  461.49
 2213.55  444.57 2302.93  444.54 2332.73  444.76 2392.32  461.57  2506.3  476.19
  2614.5  475.44  2690.6  485.82    2867  494.58  3454.4  480.82  3595.6  490.53
  4363.3  503.92  4524.3  516.72  4818.2   553.1  5066.8  544.13  5441.9  577.61
  5698.4  570.67  5911.5  548.91  6014.2  546.16  6164.7     549  6245.6  560.74
#Mann= 3 , 0 , 0
       0      .1       0 2124.16    .035       0 2392.32      .1       0
#XS Ineff= 2 , 0
                         2899.12          494.84
Permanent Ineff=
       F       F
Bank Sta=2124.16,2392.32
XS Rating Curve= 0 ,0
Exp/Cntr=0.3,0.1

Type RM Length L Ch R = 1 ,28332.15,1545.5,1797.3,2133.6
BEGIN DESCRIPTION:
8852.190
END DESCRIPTION:
XS GIS Cut Line= 6
      1990815.21       687236.61      1991542.08       685603.12
1991407.49896967684858.8013253091990827.65426256 684229.72191109
1990296.54617782       684051.99      1990065.13       682554.04
#Sta/Elev= 30
       0  598.88   373.1  613.53   661.9  597.04   825.5  596.63  1215.5  569.64
  1742.4  511.39  1940.3  508.98  2072.4  529.77  2458.6  495.42  2741.9  492.67
  2827.4  480.36  3202.1  476.46    3534  485.02 3623.53   452.1    3673     441
  3708.4  446.48    3753  437.93 3848.07   452.4    3861   465.1  3984.8  478.49
  4007.3     495  4063.3  506.07  4092.4  528.54  4180.2  544.69  4266.8  603.87
  4322.2  623.64  4703.6  634.18  5330.6  776.97  5416.2  783.17  5508.3   777.1
#Mann= 3 , 0 , 0
       0      .1       0 3623.53    .035       0 3848.07      .1       0
Bank Sta=3623.53,3848.07
XS Rating Curve= 0 ,0
Exp/Cntr=0.3,0.1

Type RM Length L Ch R = 1 ,26534.84,1373.8,1455.3,1532.5
XS GIS Cut Line= 6
      1990864.89       687311.28      1991082.07       686896.25
      1991442.87       686429.461991781.07911924685404.495151662
1992042.22617782684449.240145402      1993156.19       682564.79
#Sta/Elev= 30
       0  586.93   280.8  602.32   485.4   605.4   691.5  595.71   984.6  594.66
  1323.4  568.15  1771.3  520.14  1952.6  509.36    2457  491.11    2917  486.56
  3197.7  472.58 3360.25  444.54  3449.2  445.89  3537.5  473.93  3614.6  489.13
  3670.8  527.39  3790.3  585.27  3800.5   605.6  3816.5  662.52  3826.7  681.05
  3872.8  734.09  3924.7  769.14  4057.3  826.23  4100.5  854.18    4285  890.41
    4360  891.94  4567.5  844.76    5046   686.8  5152.6  714.91  5317.6  723.12
#Mann= 3 , 0 , 0
       0      .1       0  3197.7    .035       0  3537.5      .1       0
Bank Sta=3197.7,3537.5
XS Rating Curve= 0 ,0
Exp/Cntr=0.3,0.1

Type RM Length L Ch R = 1 ,25079.58,1665.1,1674.1,1706.5
BEGIN DESCRIPTION:
7819.111
END DESCRIPTION:
XS GIS Cut Line= 6
      1990886.55       687465.44      1991167.36       686830.62
      1992176.82       685846.29      1993336.92       685196.02
      1995561.08       683154.27      1998472.23        682808.6
#Sta/Elev= 30
       0  569.59   672.5  599.71  1095.6  587.32  1987.2  535.73  2418.7   478.9
  2994.6   465.4  3169.4  439.87 3266.69  444.19  3312.9   467.9  3347.1  476.59
  3461.5  575.96  3478.3  621.81  3516.9  667.76  3592.3   700.4    4415  653.52
  4685.8  598.25    5022  668.48  5460.2  797.38  6115.2  876.97  6390.1  942.16
  6453.9  942.99  6950.3  805.28  7204.6  781.95    7766  918.31  8096.1  822.41
  8448.3  755.28  8596.8  695.32  8652.2   694.4  9168.3  844.18  9385.5  795.52
#Mann= 3 , 0 , 0
       0      .1       0  2994.6    .035       0  3312.9      .1       0
#XS Ineff= 2 , 0
         2577.59  480.64
Permanent Ineff=
       F       F
Bank Sta=2994.6,3312.9
XS Rating Curve= 0 ,0
Exp/Cntr=0.3,0.1

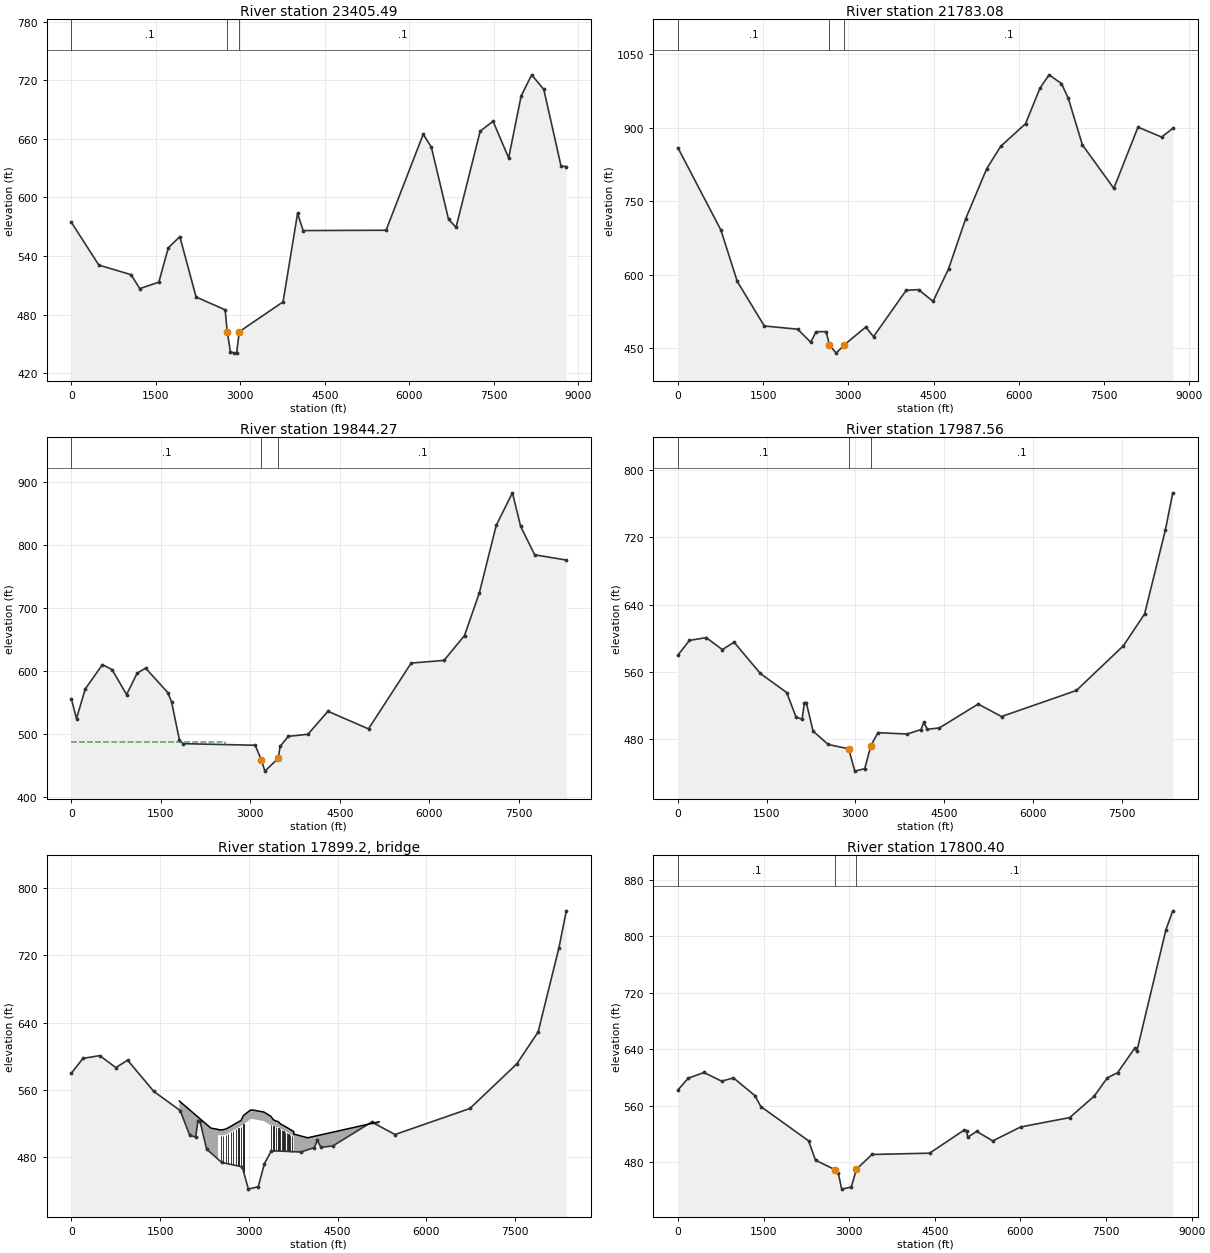
Type RM Length L Ch R = 1 ,23405.49,1621.7,1622.4,1644.9
XS GIS Cut Line= 6
      1991529.53       688488.64      1992381.92       687610.26
1994345.14271002686592.827955558       1994948.3       686418.69
      1996657.53       685571.01       1999397.9       684987.02
#Sta/Elev= 30
       0  574.45   486.7  530.69    1060  520.85  1213.2  506.61  1552.2  513.23
  1720.3  548.36  1924.9  559.82  2213.1  498.05  2729.4   484.9  2766.3  462.53
 2823.02  442.08 2894.45  440.57 2934.03  441.01  2980.5  462.53  3757.5  493.03
  4015.1  583.62  4114.1  566.02  5586.3  566.36  6245.8  664.65  6389.9   651.5
  6694.8  577.73  6828.3  569.28    7257  667.79  7485.5  677.95  7762.8  640.35
  7983.6  703.63    8171  725.45  8386.8  710.48  8692.6   632.1    8786  631.49
#Mann= 3 , 0 , 0
       0      .1       0  2766.3    .035       0  2980.5      .1       0
Bank Sta=2766.3,2980.5
XS Rating Curve= 0 ,0
Exp/Cntr=0.3,0.1

Type RM Length L Ch R = 1 ,21783.08,1900.4,1938.8,2022.6
BEGIN DESCRIPTION:
6797.347
END DESCRIPTION:
XS GIS Cut Line= 6
      1992173.48       689511.66      1993159.08       688816.59
 1995114.4886029688050.853500289      1995862.71       688281.61
      1998316.82       687898.74      2000323.75       687165.99
#Sta/Elev= 30
       0  859.28     757  691.51  1045.4  586.77  1521.2  495.89  2107.6   489.4
  2338.6   462.7  2431.5  484.17  2609.2  484.35 2668.61  457.02  2785.7  440.55
 2928.02  457.32  3307.2  493.67  3443.2  474.15  4018.7  568.63  4236.2  570.05
  4491.8  546.06  4765.3  612.62  5066.1   714.7  5436.8  816.75  5684.1  862.41
  6118.7  908.21  6374.3     981  6533.7 1007.93  6751.9  990.17  6873.2  959.69
  7119.7  865.18  7673.3  776.45  8099.1  901.31  8514.3  881.11  8710.9  898.71
#Mann= 3 , 0 , 0
       0      .1       0 2668.61    .035       0 2928.02      .1       0
Bank Sta=2668.61,2928.02
XS Rating Curve= 0 ,0
Exp/Cntr=0.3,0.1

Type RM Length L Ch R = 1 ,19844.27,1849.7,1856.7,1875.8
XS GIS Cut Line= 6
      1992415.39       691318.78      1993600.33       690421.52
1995743.57058744689984.861323671      1996088.64        690071.6
      1997088.67       689986.19      1999522.36        687821.2
#Sta/Elev= 30
       0  555.67    85.6  524.59   231.9  571.61   519.9   610.2   682.3  602.29
   924.6  562.69  1102.2  596.66  1243.9  604.61  1614.8  565.98  1678.7  551.33
  1811.5   490.6  1870.2  484.92  3081.3   482.4  3181.6  459.77 3243.79  441.37
  3467.9  461.81  3498.4  480.43  3635.2   496.5  3965.2  499.78  4300.7  536.21
  4980.6  508.33  5695.4  612.65  6246.8  616.92  6590.2  656.37  6838.8  723.93
  7122.4  831.13  7393.7  882.55  7530.8  829.42    7766  784.33  8296.4     776
#Mann= 3 , 0 , 0
       0      .1       0  3181.6    .035       0  3467.9      .1       0
#XS Ineff= 2 , 0
         2572.76  487.51
Permanent Ineff=
       F       F
Bank Sta=3181.6,3467.9
XS Rating Curve= 0 ,0
Exp/Cntr=0.5,0.3

Type RM Length L Ch R = 1 ,17987.56,186.9,187.2,186.5
BEGIN DESCRIPTION:
5611.002
END DESCRIPTION:
XS GIS Cut Line= 5
       1992657.3       693125.891993880.59813086692023.670682225
       1995764.3       691870.491997292.27356074691787.986330207
  1998590.503421688757.649514727
#Sta/Elev= 30
       0   580.1     195  597.61   478.8  600.94   751.5  586.66   949.4   595.5
  1393.8  558.28  1838.2  535.68  1998.7  506.21  2099.1  504.09  2139.2  523.63
  2170.2  523.73  2284.7  489.76  2540.5  473.91  2886.7  468.75  2990.4  442.23
  3157.3  445.13 3261.68472.4565  3380.5  487.95  3876.8  486.32  4107.1  491.62
  4154.7  500.04  4217.3  491.94  4420.1  493.62    5075  521.99  5469.4  507.13
  6734.1  538.07  7528.3  591.19  7887.2  629.02  8239.2  729.12  8363.5  773.03
#Mann= 3 , 0 , 0
       0      .1       0  2886.7    .035       0 3261.68      .1       0
Bank Sta=2886.7,3261.68
XS Rating Curve= 0 ,0
Exp/Cntr=0.5,0.3

Type RM Length L Ch R = 3 ,17899.2 ,,,
BEGIN DESCRIPTION:
Cookeville Hwy
2019 Update:
-Removed tressle as this is open space.
END DESCRIPTION:
Bridge Culvert--1,0,-1,-1, 0
Deck Dist Width WeirC Skew NumUp NumDn MinLoCord MaxHiCord MaxSubmerge Is_Ogee
77,50,2.61,0, 35, 35, , , 0.95, 0, 0,0,,
    1825 2358.25 2478.152478.151 2479.84 2522.13 2565.04 2608.01 2651.05 2694.04
 2737.04 2779.82 2822.92 2865.51  2907.8 3025.29 3070.73  3255.3 3369.15 3414.01
 3456.91 3499.33 3527.37 3556.11 3584.75 3612.97 3641.48 3669.92 3698.52 3726.73
 3756.65 3756.66 3756.67 3992.86 5200.19
  546.89  514.71  513.27  513.27  512.76  512.66  512.87   513.7  515.14  516.88
  518.64  520.36  522.08  523.82  529.81   536.2   536.2  533.81  528.84  524.62
  523.21  522.32  520.02  518.84  517.77   516.6  515.48  514.32  513.15  511.91
  510.77  510.77  507.67  503.25  522.26
                          506.67  506.67  506.06  506.27   507.1  508.54  510.28
  512.04  513.76  515.48  517.22  519.06  525.45  525.45  523.06  518.09  518.01
  516.21  515.67  514.01  513.33  512.16  511.05  509.93  508.77   507.6  506.36
  504.87
    1668 2201.25 2321.152321.151 2322.84 2365.23 2408.08 2450.85 2494.08 2536.98
 2580.03 2623.06 2665.93 2708.85 2751.06 2868.29 2913.73 3098.85 3212.44 3255.89
 3298.88 3341.97 3370.47 3398.63 3426.99 3455.98 3484.31 3513.01  3541.7 3570.26
 3599.89  3599.9 3599.91 3835.86 5667.19
  546.89  514.71  513.27  513.27  512.76  512.67  512.89  513.69  515.15  516.93
  518.68  520.39  522.08  523.77  529.81   536.2   536.2  533.81  528.95  523.89
  522.57   521.2  521.12  518.84   518.3   516.6   515.5  514.29  513.12  512.03
   510.8   510.8  507.67  503.25     521
                          506.67  506.67  506.07  506.29  507.09  508.55  510.33
  512.08  513.79  515.47  517.17  519.07  525.45  525.45  523.03  518.09  517.29
  515.57  514.55  514.52  513.33   512.2  511.05  509.95  508.74  507.57  506.48
  504.87
Pier Skew, UpSta & Num, DnSta & Num=  ,2522.13, 2 ,2365.23, 2 , 2 , 2 , 0 ,,
     2.5       3
   491.5  505.57
     2.5       3
   491.5  505.57
Pier Skew, UpSta & Num, DnSta & Num=  ,2565.04, 2 ,2408.08, 2 , 2 , 2 , 0 ,,
     2.5       3
  484.95  505.79
     2.5       3
  484.95  505.79
Pier Skew, UpSta & Num, DnSta & Num=  ,2607.85, 2 ,2451.01, 2 , 2 , 2 , 0 ,,
     2.5       3
  482.41  506.59
     2.5       3
  482.41  506.59
Pier Skew, UpSta & Num, DnSta & Num=  ,2651.05, 2 ,2494.08, 2 , 2 , 2 , 0 ,,
       2       3
  481.17  508.04
       2       3
  481.17  508.04
Pier Skew, UpSta & Num, DnSta & Num=  ,2694.04, 2 ,2536.98, 2 , 2 , 2 , 0 ,,
       2       3
  480.34  509.78
       2       3
  480.34  509.78
Pier Skew, UpSta & Num, DnSta & Num=  ,2737.04, 2 ,2580.03, 2 , 2 , 2 , 0 ,,
       2       3
  478.48  511.58
       2       3
  478.48  511.58
Pier Skew, UpSta & Num, DnSta & Num=  ,2780.06, 2 ,2622.82, 2 , 2 , 2 , 0 ,,
       2       3
  475.71  513.26
       2       3
  475.71  513.26
Pier Skew, UpSta & Num, DnSta & Num=  ,2822.92, 2 ,2665.93, 2 , 2 , 2 , 0 ,,
       2       3
  474.11  514.97
       2       3
  474.11  514.97
Pier Skew, UpSta & Num, DnSta & Num=  ,2865.51, 2 ,2708.85, 2 , 2 , 2 , 0 ,,
       2       3
  473.78  516.67
       2       3
  473.78  516.67
Pier Skew, UpSta & Num, DnSta & Num=  ,2909.22, 3 ,2751.8, 3 , 0 , 0 , 0 ,,
    3.42    3.42       2
  474.46  518.47  520.33
    3.42    3.42       2
  474.46  518.47  520.33
Pier Skew, UpSta & Num, DnSta & Num=  ,3369.44, 3 ,3212.15, 3 , 0 , 0 , 0 ,,
    3.27    3.27       2
  476.95  518.98  521.84
    3.27    3.27       2
  476.95  519.01  521.95
Pier Skew, UpSta & Num, DnSta & Num=  ,3414.01, 2 ,3255.89, 2 , 2 , 2 , 0 ,,
       2       3
  481.16  517.51
       2       3
  481.16  516.79
Pier Skew, UpSta & Num, DnSta & Num=  ,3456.91, 2 ,3298.88, 2 , 2 , 2 , 0 ,,
       2       3
  487.97  515.71
       2       3
  487.97  515.07
Pier Skew, UpSta & Num, DnSta & Num=  ,3499.33, 2 ,3341.97, 2 , 2 , 2 , 0 ,,
       2       3
  491.03  515.17
       2       3
  491.03  515.17
Pier Skew, UpSta & Num, DnSta & Num=  ,3527.37, 2 ,3370.47, 2 , 2 , 2 , 0 ,,
       2       3
  490.88  514.01
       2       3
  490.88  514.02
Pier Skew, UpSta & Num, DnSta & Num=  ,3555.63, 2 ,3399.11, 2 , 2 , 2 , 0 ,,
       2       3
  490.43  512.83
       2       3
  490.43  512.83
Pier Skew, UpSta & Num, DnSta & Num=  ,3584.75, 2 ,3426.99, 2 , 2 , 2 , 0 ,,
       2       3
  490.64  511.66
       2       3
  490.64   511.7
Pier Skew, UpSta & Num, DnSta & Num=  ,3612.97, 2 ,3455.98, 2 , 2 , 2 , 0 ,,
       2       3
  491.05  510.55
       2       3
  491.05  510.55
Pier Skew, UpSta & Num, DnSta & Num=  ,3641.48, 2 ,3484.31, 2 , 2 , 2 , 0 ,,
       2       3
  490.54  509.43
       2       3
  490.54  509.45
Pier Skew, UpSta & Num, DnSta & Num=  ,3670.01, 2 ,3512.92, 2 , 2 , 2 , 0 ,,
       2       3
  490.27  508.24
       2       3
  490.27  508.27
Pier Skew, UpSta & Num, DnSta & Num=  ,3698.52, 2 ,3541.7, 2 , 2 , 2 , 0 ,,
       2       3
  489.82   507.1
       2       3
  489.82  507.07
Pier Skew, UpSta & Num, DnSta & Num=  ,3726.73, 2 ,3570.26, 2 , 2 , 2 , 0 ,,
     2.5       3
  489.45  505.86
     2.5       3
  489.45  505.68
BR Coef=-1 , 1 , 0 ,, 0 ,,,0.8,0,1.33,0,
WSPro=,,,, 1 ,,,, 0 ,,,, 0 ,,,,-1 ,-1 ,-1 , 0 , 0 , 0 , 0 , 0
BC Design=,, 0 ,, 0 ,,,,,,
BC HTab HWMax=600
BC Use User HTab Curves=0
BC User HTab FreeFlow(D)= 0

Type RM Length L Ch R = 1 ,17800.40,451.9,481.9,505.7
XS GIS Cut Line= 5
1992689.66657572693156.5951667011993782.95683978692212.239768405
1995656.31051694692065.4817999741997337.89266705691943.355722033
1998798.08853691688588.876682762
#Sta/Elev= 30
       0  582.59   180.9  599.09     457  607.26   766.8     595   973.7  599.62
  1347.5  574.58  1454.4     559  2288.4  510.56  2411.2  483.09  2759.7 469.402
    2810  464.72  2869.4442.1654  3036.3445.0654  3128.4  470.39  3398.9  491.21
  4409.4  493.06  5009.8  525.55  5056.7  524.89  5075.7  515.67  5233.9  523.88
  5515.4  510.45  6002.7  530.14  6863.2  543.44  7292.5  573.82  7520.5  599.59
  7701.4  606.94  7998.6  641.33  8039.5  637.66  8549.4  809.62  8668.3   836.1
#Mann= 3 , 0 , 0
       0      .1       0  2759.7    .035       0  3128.4      .1       0
Bank Sta=2759.7,3128.4
XS Rating Curve= 0 ,0
Exp/Cntr(USF)=0,0
Exp/Cntr=0.5,0.3