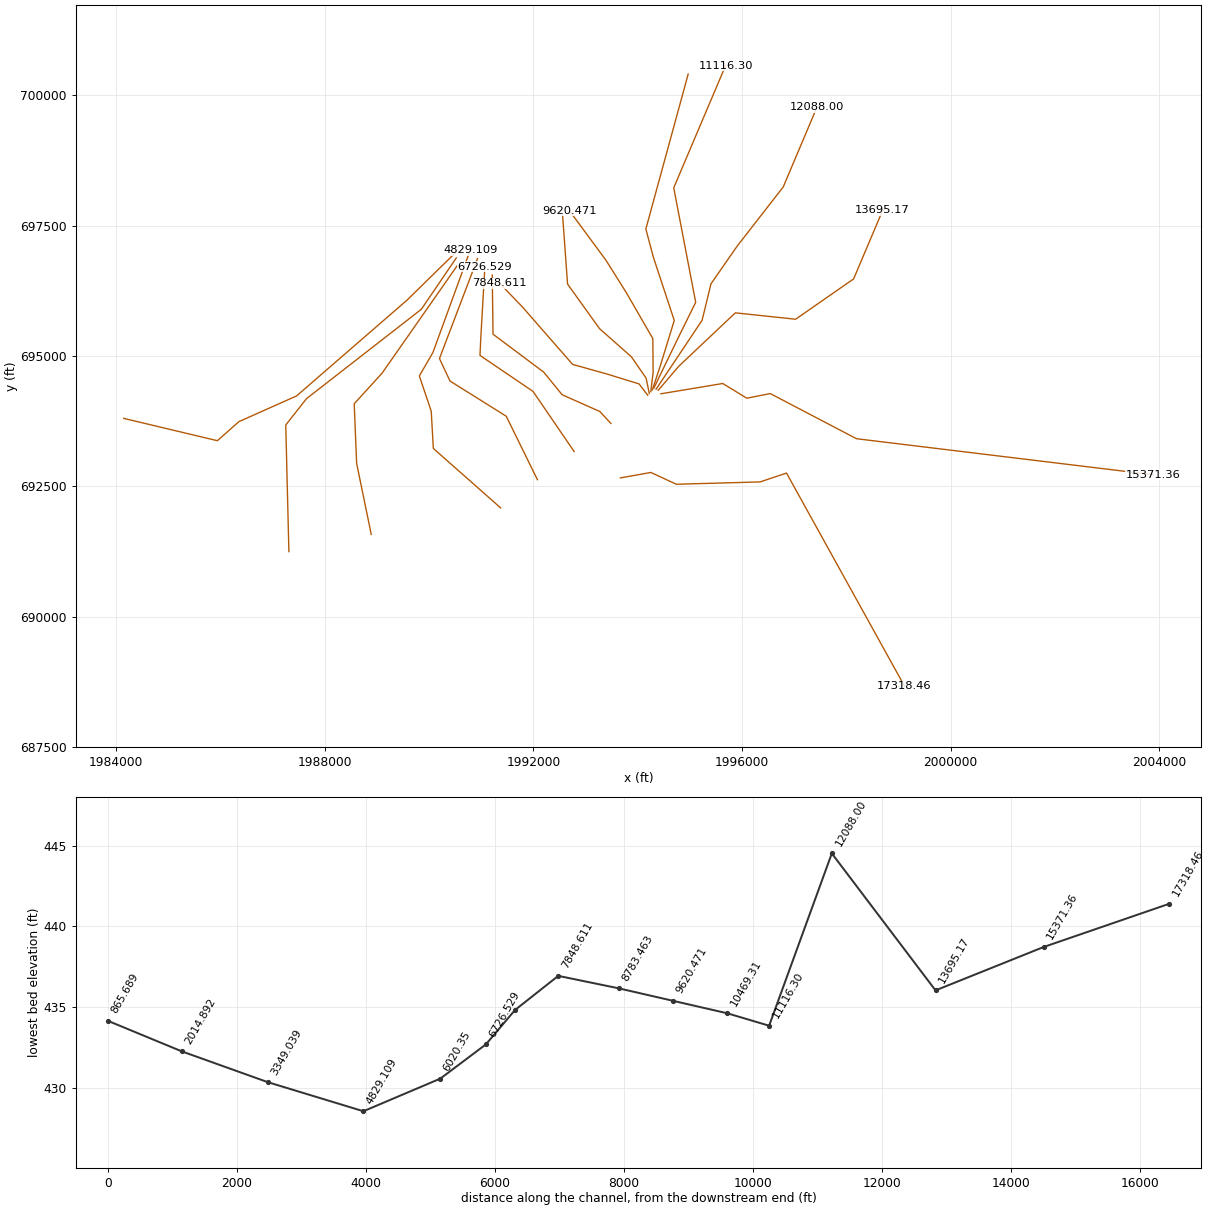
HEC-RAS study CaneyFork.prj: Caney Fork River- Smith County

--- CaneyFork.g02 (geometry) --- (continued)

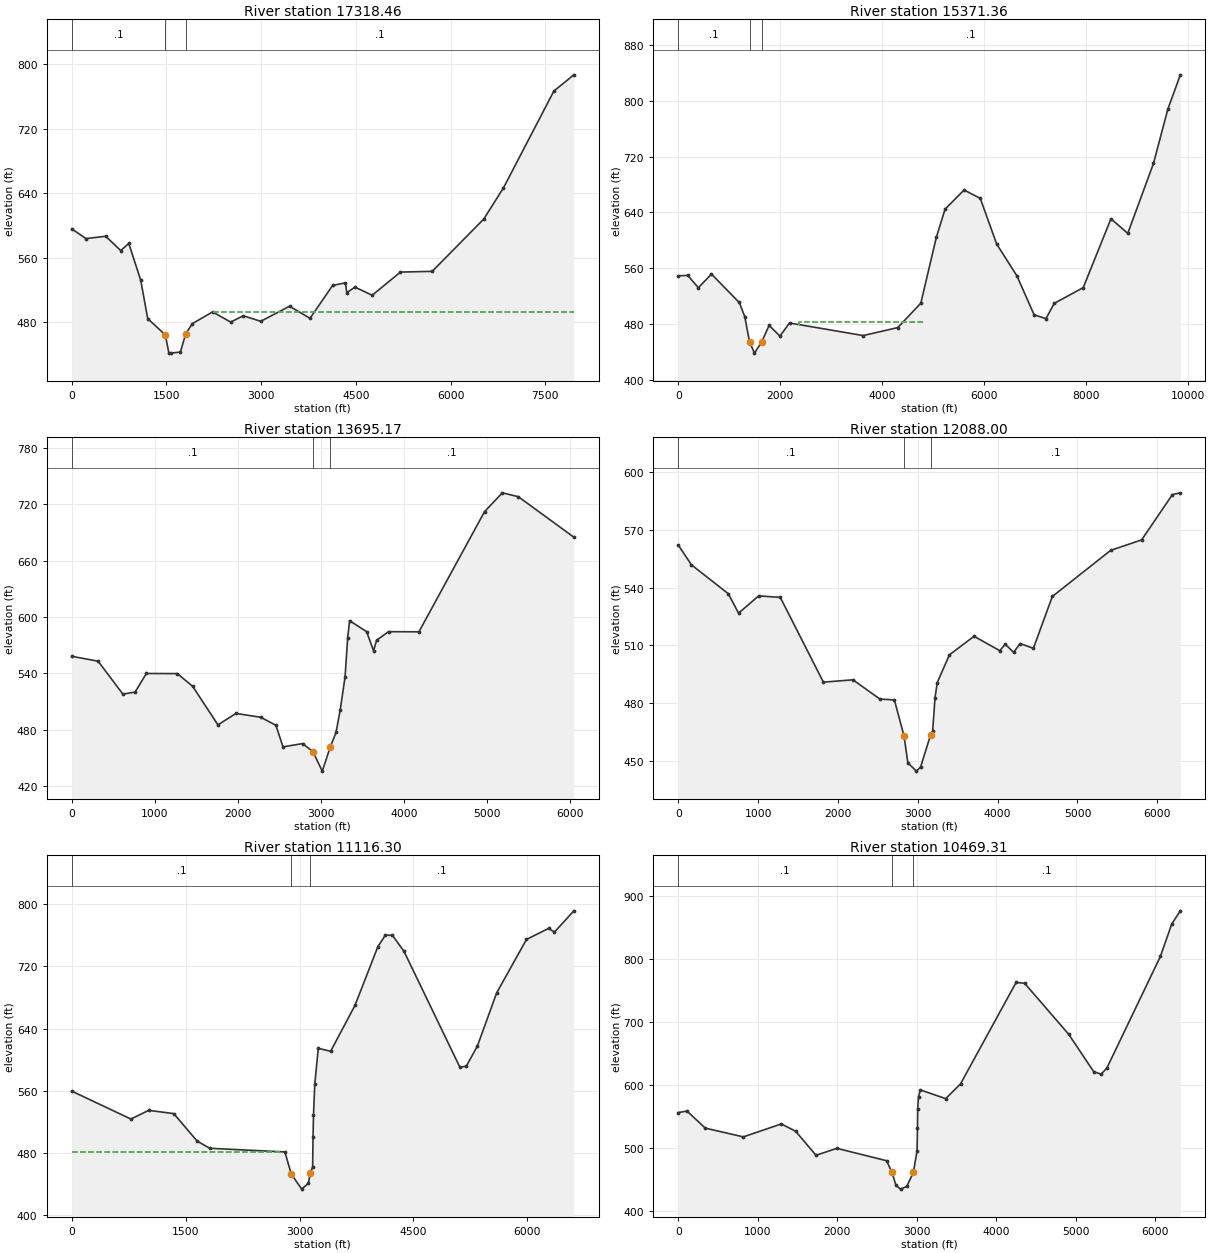
Type RM Length L Ch R = 1 ,17318.46,2074.7,1947.1,1801.4
BEGIN DESCRIPTION:
5451.291
END DESCRIPTION:
XS GIS Cut Line= 6
      1993667.76       692663.28      1994252.47       692768.04
1994741.59985877692541.607793933      1996348.09       692586.63
      1996854.54       692756.28      1999117.35       688669.28
#Sta/Elev= 30
       0  595.68   224.8  583.54   537.1  586.45   775.5  568.73     903  577.51
  1092.2  531.94  1203.2  484.21  1481.1   464.1 1538.17  441.69 1570.42  441.39
 1720.88  442.74  1803.8  465.01  1910.2     478  2229.9  492.54  2517.6  479.94
  2718.1  487.79  2993.3  480.88  3449.4   499.6  3774.6  484.63  4133.4   525.5
  4335.1   528.6  4356.6  516.46  4486.2  523.29  4758.9  513.24  5206.7  541.99
  5709.8  542.89  6527.2  607.86  6839.3  646.57  7637.7   766.7  7953.8  786.81
#Mann= 3 , 0 , 0
       0      .1       0  1481.1    .045       0  1803.8      .1       0
#XS Ineff= 2 , 0
                         2231.01          492.54
Permanent Ineff=
       F       F
Bank Sta=1481.1,1803.8
XS Rating Curve= 0 ,0
Exp/Cntr=0.3,0.1

Type RM Length L Ch R = 1 ,15371.36,1487,1676.2,1770.9
XS GIS Cut Line= 6
1994445.59647476694277.2105808861995631.25529237694474.360580886
      1996093.61       694192.02      1996542.66       694280.95
      1998197.18       693415.052003889.22207685692723.906209724
#Sta/Elev= 30
       0  549.37   187.2  549.86     395  532.31   651.3  551.83    1197  511.16
  1304.6  491.07 1398.09455.0192 1495.31  438.71 1640.11  455.12    1782  478.36
  1994.9  463.07  2182.5  481.86    3627  463.86  4304.7  475.22    4758  510.16
  5062.7  604.47    5234  644.73  5606.7   672.1    5924   660.2  6246.5  594.71
  6644.3  549.11  6980.8  493.43  7213.4  488.15  7374.6  509.87  7943.7  532.46
  8487.4  630.95  8817.4  610.06  9321.3  710.08  9603.3  787.77  9847.8  836.92
#Mann= 3 , 0 , 0
       0      .1       0 1398.09     .04       0 1640.11      .1       0
#XS Ineff= 1 ,-1
 2360.74  4847.3     483
Permanent Ineff=
       F
Bank Sta=1398.09,1640.11
XS Rating Curve= 0 ,0
Exp/Cntr=0.3,0.1

Type RM Length L Ch R = 1 ,13695.17,1335.3,1607.2,1803.5
BEGIN DESCRIPTION:
4262.708
END DESCRIPTION:
XS GIS Cut Line= 6
       1994393.6       694343.78      1994787.37       694805.11
      1995873.12       695829.451997029.06117208695707.059412674
      1998141.69       696480.43      1998697.31       697792.71
#Sta/Elev= 30
       0  558.19   317.6  552.93     615  517.96   761.8  520.08     898  539.88
  1271.1  539.76  1455.8  526.16  1759.2  485.27  1976.8  497.41  2274.3   493.3
  2457.2  484.83  2542.6  461.81  2778.9  465.34 2902.79  456.71  3015.2  436.02
 3111.58  461.72    3181  477.13  3231.5  501.27  3289.4  536.08  3321.4  577.94
  3344.2  596.02    3549   584.4  3632.7  564.11  3669.9  575.32  3812.5  584.37
  4178.5  584.21  4968.6  712.05  5183.1  732.07  5375.8  727.93  6043.5  684.88
#Mann= 3 , 0 , 0
       0      .1       0 2902.79    .035       0 3111.58      .1       0
Bank Sta=2902.79,3111.58
XS Rating Curve= 0 ,0
Exp/Cntr=0.3,0.1

Type RM Length L Ch R = 1 ,12088.00,819.9,971.7,1097.5
XS GIS Cut Line= 6
      1994352.28       694364.59      1995235.61       695687.64
      1995405.11       696385.351995910.27529238697112.131763266
      1996791.77       698244.97      1997435.93       699769.14
#Sta/Elev= 30
       0  562.21   165.9  551.91   625.8  536.92   755.8  526.76  1007.1  535.76
  1278.1  534.98    1818  490.84  2188.5  492.06  2525.5  482.04  2707.4  481.58
  2828.8  462.61 2875.57  448.82 2982.79  444.51 3035.16  446.62  3161.9  463.51
  3186.2   465.2  3216.4  482.78    3244   490.6  3396.7  505.07  3705.1  514.73
  4027.3  507.22  4095.3  510.59  4200.6  506.38  4283.1  510.94  4447.7  508.42
  4685.6  535.45  5415.7  559.45  5803.8   564.9  6189.2  588.49  6288.3  589.41
#Mann= 3 , 0 , 0
       0      .1       0  2828.8    .035       0  3161.9      .1       0
Bank Sta=2828.8,3161.9
XS Rating Curve= 0 ,0
Exp/Cntr=0.3,0.1

Type RM Length L Ch R = 1 ,11116.30,636.7,647,661.9
BEGIN DESCRIPTION:
3432.218
END DESCRIPTION:
XS GIS Cut Line= 6
      1994310.65       694386.32      1994523.65        694828.7
      1994828.83       695457.67      1995112.63       696031.33
      1994691.09       698227.411995685.94891032700572.606112642
#Sta/Elev= 30
       0  559.73   779.1  523.88  1013.1  535.04  1343.7  530.86  1650.5  495.62
  1817.9  486.31  2807.3  481.61 2890.91  453.37  3029.1  433.83 3116.21  441.36
 3141.37  454.02  3172.8  462.57  3178.3  500.93  3184.2     529  3201.2  568.71
  3247.1  614.73    3410  610.94    3731  669.93  4032.1  745.33  4131.5  760.21
  4224.3  759.94  4375.9  739.47  5112.3  590.52  5196.5  591.76  5343.1  617.58
  5597.5  686.07  5989.5  754.58    6280  768.77  6358.9  764.16  6613.8  791.41
#Mann= 3 , 0 , 0
       0      .1       0 2890.91    .035       0 3141.37      .1       0
#XS Ineff= 2 , 0
         2748.06   481.9
Permanent Ineff=
       F       F
Bank Sta=2890.91,3141.37
XS Rating Curve= 0 ,0
Exp/Cntr=0.3,0.1

Type RM Length L Ch R = 1 ,10469.31,802.2,848.8,901
XS GIS Cut Line= 6
       1994280.9       694352.07      1994429.69       694800.88
      1994701.28       695683.26      1994298.66       696902.53
      1994156.39        697438.3      1994968.49        700409.5
#Sta/Elev= 30
       0  556.07     110  558.58   340.5  531.44   818.6  517.54  1296.2  538.09
    1477  526.45  1732.6  488.31  1995.8  499.35  2619.9  479.71  2688.2  461.31
 2738.23  440.71 2796.78   434.6 2873.73   438.8  2957.2  461.31  3003.8  495.66
  3009.1   531.3  3011.6  562.41  3021.9  581.03  3045.2  592.19  3363.6  578.23
  3550.3  601.68  4249.2  762.77  4356.6   761.4  4911.4  680.37  5225.1  621.13
  5318.3  617.07  5390.9  626.83  6064.3   804.1  6206.8  855.63  6314.6  876.45
#Mann= 3 , 0 , 0
       0      .1       0  2688.2    .035       0  2957.2      .1       0
#XS Ineff= 2 , 0
         2573.31  479.94
Permanent Ineff=
       F       F
Bank Sta=2688.2,2957.2
XS Rating Curve= 0 ,0
Exp/Cntr=0.3,0.1

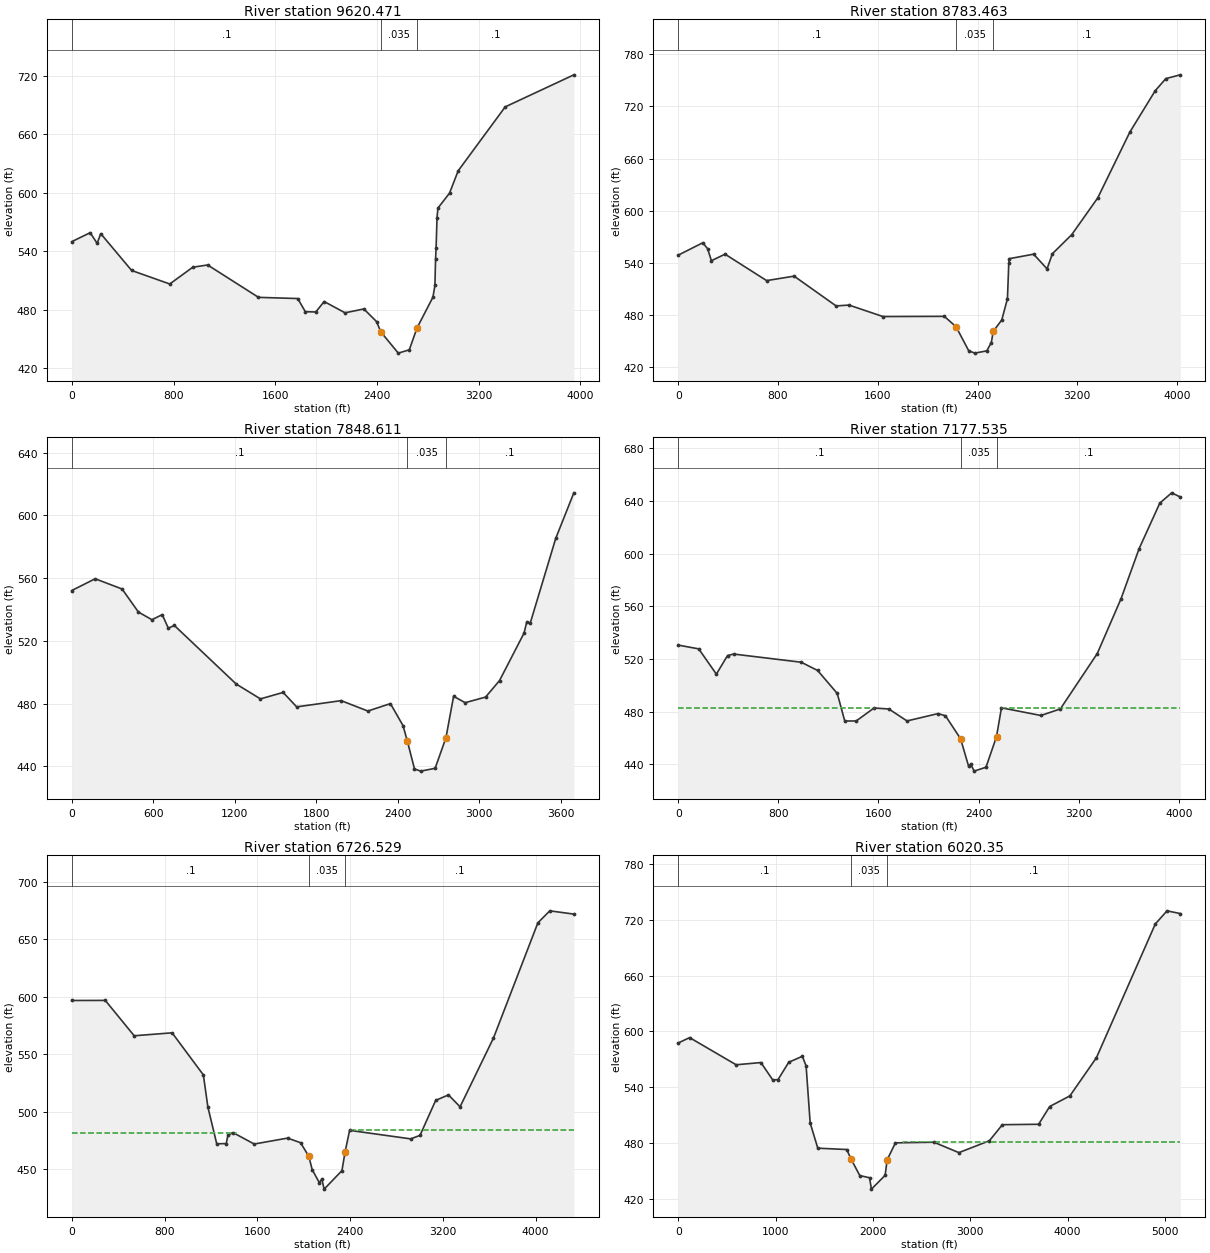
Type RM Length L Ch R = 1 ,9620.471,810.7,837,857.8
XS GIS Cut Line= 6
      1994251.77       694317.23      1994295.88       694689.23
      1994290.32       695335.35      1993783.13        696214.8
1993387.08706208696844.3617619781992693.51707367697784.461782587
#Sta/Elev= 30
       0  549.89   144.6   559.1   199.5  548.16   227.9   558.1   470.8  520.28
   770.6  506.41   951.7  523.65  1068.5  525.94  1468.3  492.68  1776.9  491.45
  1836.2  477.97  1918.6  477.64  1984.7  488.38  2148.9   476.8  2296.6  480.75
    2397  467.73 2429.68  457.28 2567.45  435.38 2654.05  438.78    2715  461.31
    2840  492.85  2855.6  504.96  2860.6  531.68  2864.8  543.13    2872  574.35
  2879.2  584.37  2970.4  599.74  3038.9  622.78  3408.4  688.37    3948  721.28
#Mann= 3 , 0 , 0
       0      .1       0 2429.68    .035       0    2715      .1       0
Bank Sta=2429.68,2715
XS Rating Curve= 0 ,0
Exp/Cntr=0.3,0.1

Type RM Length L Ch R = 1 ,8783.463,929,934.9,939.5
XS GIS Cut Line= 6
      1994222.65       694282.39      1994161.06       694577.68
      1993879.27       694986.46       1993267.6       695527.06
1992654.64411901696381.425303967      1992557.16       697733.62
#Sta/Elev= 30
       0  548.85   197.1   563.1   235.4  556.25     266  542.48   375.5  549.97
   708.8  519.57   929.3  524.69  1265.9  490.45  1369.6  491.41  1641.6  478.22
  2133.8  478.44  2227.9  466.49 2329.58  438.86 2378.12  436.15 2474.38  438.75
 2510.53  448.33  2526.3  461.16  2594.5  474.33    2640  498.78  2650.6  539.31
  2655.9  544.82  2849.9  549.96  2957.7  533.09  3000.3  550.47  3155.7  572.44
  3363.7  614.59  3621.9  690.48  3824.9  737.93  3910.1  751.91  4026.2  756.24
#Mann= 3 , 0 , 0
       0      .1       0  2227.9    .035       0  2526.3      .1       0
Bank Sta=2227.9,2526.3
XS Rating Curve= 0 ,0
Exp/Cntr=0.3,0.1

Type RM Length L Ch R = 1 ,7848.611,625.7,671.1,706.3
BEGIN DESCRIPTION:
2412.344
END DESCRIPTION:
XS GIS Cut Line= 6
      1994192.63       694248.64      1994026.25       694466.14
       1993424.1       694652.09      1992752.17       694840.31
      1991784.38       695947.82      1991351.55       696396.16
#Sta/Elev= 30
       0  552.13   172.2  559.62   370.3   553.1   490.7  538.38   590.1   533.5
     666  536.75   710.8  528.07   754.9  529.85  1210.4  492.48  1388.9     483
  1555.8  487.12  1655.5  477.91  1982.7  481.88  2179.6  475.25  2345.6  479.99
  2438.6  465.91 2469.47  456.32  2522.8  438.32  2568.8  436.92  2674.7  438.72
 2754.33   458.2  2810.7  484.67  2895.7  480.58  3046.1  484.15  3148.9  494.71
  3329.3  524.99  3348.7  531.91  3375.4   531.5  3562.6   585.4  3695.8  614.44
#Mann= 3 , 0 , 0
       0      .1       0 2469.47    .035       0 2754.33      .1       0
Bank Sta=2469.47,2754.33
XS Rating Curve= 0 ,0
Exp/Cntr=0.3,0.1

Type RM Length L Ch R = 1 ,7177.535,439.7,451,461.1
XS GIS Cut Line= 6
      1993486.91       693708.14      1993273.09       693937.52
      1992550.49       694258.511992197.13117465694692.552940495
1991225.03882921695420.005297527      1991210.24       696554.27
#Sta/Elev= 30
       0  530.52   163.7  527.66   304.8  508.47   394.2  522.61   443.9  523.72
   983.2  517.51  1113.9  511.26    1271  493.81  1330.9  472.89  1422.3  472.88
  1565.1  482.75  1683.5  481.99  1828.4  472.92  2076.6   478.5  2135.8  476.85
 2256.86  459.37 2321.38  438.32 2337.47  440.24 2365.05   434.8 2459.81  437.77
  2543.9  461.03  2583.4   482.9  2898.9  477.06    3054  482.05  3349.2  524.12
    3539  565.73    3684  603.86    3849  638.37    3944  646.18  4012.9     643
#Mann= 3 , 0 , 0
       0      .1       0 2256.86    .035       0  2543.9      .1       0
#XS Ineff= 2 , 0
          1574.5  482.77 2583.69          482.93
Permanent Ineff=
       F       F
Bank Sta=2256.86,2543.9
XS Rating Curve= 0 ,0
Exp/Cntr=0.3,0.1

Type RM Length L Ch R = 1 ,6726.529,699.5,706.2,713.7
XS GIS Cut Line= 5
       1992781.3       693168.621991992.43999742694322.442934054
1990975.09353297695012.8276532721990990.75823931695355.687650696
      1991068.93       696712.37
#Sta/Elev= 30
       0  596.72   288.9  596.79   538.2  566.04   865.2   568.6  1134.8  531.99
  1173.4   504.2  1249.9  472.11  1331.6  472.27  1346.8  479.63  1391.5  481.76
  1573.2  471.89  1861.2  477.05  1972.8  473.03    2044  461.17 2073.18  449.59
 2133.89  438.43 2156.21  441.21  2176.3  432.67  2329.8  448.77  2355.7  464.54
  2395.8  483.78  2922.6  476.38  3002.7  479.41  3137.9  509.84  3248.1  514.61
  3348.2  504.27  3636.4   564.1  4019.3  664.29    4122  674.69  4329.3  671.84
#Mann= 3 , 0 , 0
       0      .1       0    2044    .035       0  2355.7      .1       0
#XS Ineff= 2 , 0
          1414.8  481.91 2396.29          483.78
Permanent Ineff=
       F       F
Bank Sta=2044,2355.7
XS Rating Curve= 0 ,0
Exp/Cntr=0.3,0.1

Type RM Length L Ch R = 1 ,6020.35 ,1364.9,1191.2,1030.3
XS GIS Cut Line= 5
       1992076.7         692629.1991478.89999227693846.251170788
1990399.63861609694521.8585313051990197.74471278694953.528813755
      1990927.61       696870.48
#Sta/Elev= 30
       0  587.55   116.9  593.32   594.8  564.13   849.2  566.53   970.6  547.91
  1024.7  548.13  1135.1  566.84    1275  573.24  1313.4  562.95  1355.2  501.65
  1433.4  474.54  1730.9  473.09 1775.55  462.79 1864.83  445.12 1965.05  442.77
 1984.55  430.55 2125.19  445.41  2146.2  462.05  2230.8  480.26  2627.1  480.91
  2882.6  469.76  3196.2  482.51  3329.3  499.77  3701.8  500.22  3815.6  519.31
  4022.9  530.72  4295.7  571.74  4900.2  715.34  5020.6  729.51  5157.2  726.56
#Mann= 3 , 0 , 0
       0      .1       0 1775.55    .035       0  2146.2      .1       0
#XS Ineff= 2 , 0
                         2307.35          481.41
Permanent Ineff=
       F       F
Bank Sta=1775.55,2146.2
XS Rating Curve= 0 ,0
Exp/Cntr=0.3,0.1

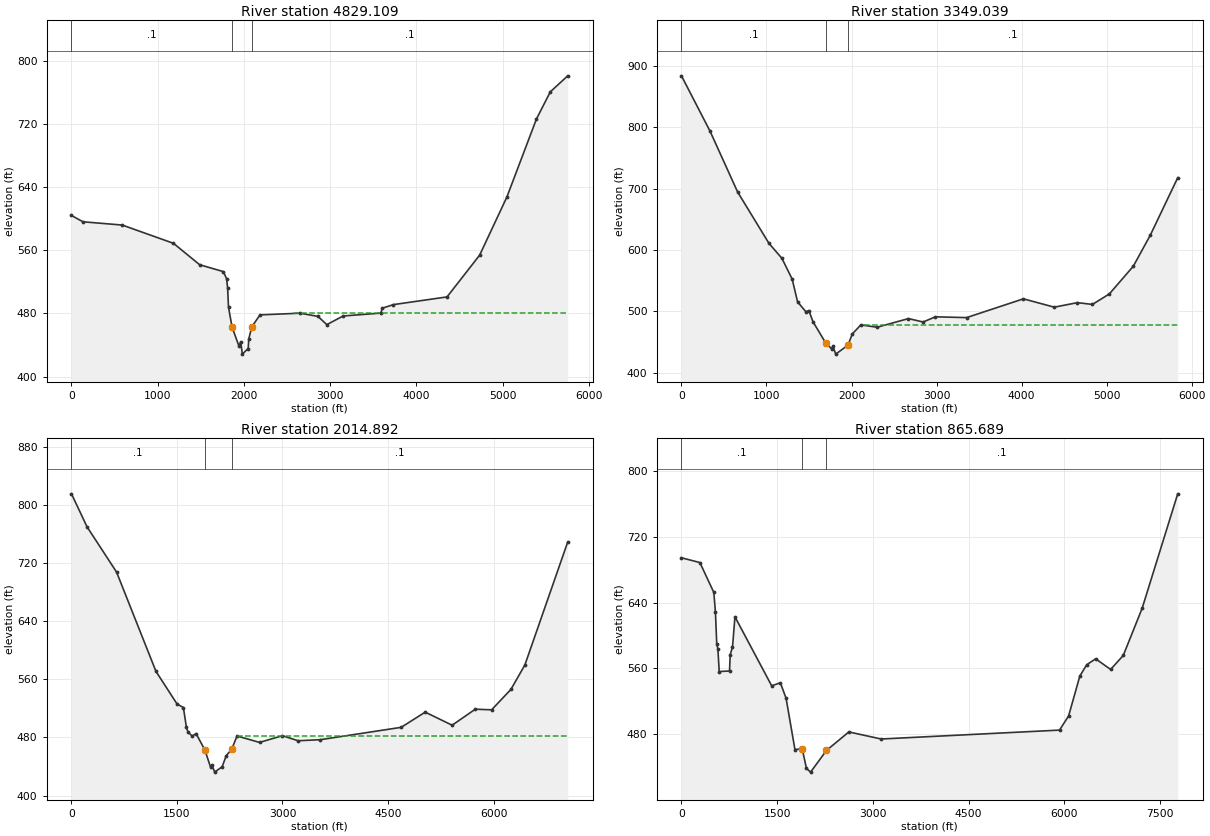
Type RM Length L Ch R = 1 ,4829.109,1482.6,1480.1,1475.5
BEGIN DESCRIPTION:
1470.010
END DESCRIPTION:
XS GIS Cut Line= 6
      1991370.98       692088.491990080.58058861693228.257644255
 1990039.5503858693943.5350099251989811.87882277694619.951178516
1990072.30764426695068.257056929       1990786.3       697028.59
#Sta/Elev= 30
       0  604.17   133.8  596.18   589.6  592.03  1183.3  568.89  1486.9  541.78
  1761.4  533.08  1799.4  524.08  1811.5  512.09  1821.5  488.04 1862.54  462.88
  1942.9  438.63  1963.9  444.33  1981.7  428.53  2049.9  435.63  2056.5  447.73
  2091.9  463.09  2186.9  478.25  2651.3  480.37  2858.4  476.36  2962.4  465.93
  3151.8  476.86    3589   480.5  3604.1  486.67  3733.8  491.25  4356.4  501.01
  4734.7   553.9  5050.8  627.58    5394  726.46  5554.1  760.77  5756.6  781.09
#Mann= 3 , 0 , 0
       0      .1       0 1862.54    .035       0  2091.9      .1       0
#XS Ineff= 2 , 0
                         2575.32          480.72
Permanent Ineff=
       F       F
Bank Sta=1862.54,2091.9
XS Rating Curve= 0 ,0
Exp/Cntr=0.3,0.1

Type RM Length L Ch R = 1 ,3349.039,1338,1334.1,1330.6
XS GIS Cut Line= 5
 1988889.1356792691580.3767313531988609.09169042692941.873268647
1988562.39319967694085.412285477      1989097.64       694673.27
       1990533.7       696728.02
#Sta/Elev= 30
       0  883.55   336.9  793.17   660.5  694.35  1028.6   610.8  1181.3  586.36
  1301.7  552.59  1365.5  515.51  1463.6  499.26  1498.6  501.34  1546.1  483.25
 1694.58  448.88 1768.72  438.61 1780.93  443.74 1813.83  430.33 1958.27  444.91
  2009.3  463.16  2109.1  477.93  2301.4  474.14  2669.7  488.21  2842.1  482.65
  2986.3  491.09  3353.4  489.81  4021.4  520.38  4384.4  506.81    4657  514.17
  4832.7  511.26  5032.2  528.34  5314.1   573.5  5512.9  623.79  5836.4  717.59
#Mann= 3 , 0 , 0
       0      .1       0 1694.58    .035       0 1958.27      .1       0
#XS Ineff= 2 , 0
                         2141.58          477.97
Permanent Ineff=
       F       F
Bank Sta=1694.58,1958.27
XS Rating Curve= 0 ,0
Exp/Cntr=0.3,0.1

Type RM Length L Ch R = 1 ,2014.892,1355.7,1149.2,965.6
XS GIS Cut Line= 5
1987309.77962662691249.6856609461987249.51372168693678.712486929
1987647.86793873694184.0249215721989849.61663407695897.717617642
1990520.49003137696882.987872301
#Sta/Elev= 30
       0  815.63   220.5  770.31   640.9  707.84  1201.1  571.06  1501.2  526.05
  1591.2   521.2  1633.7  494.13  1656.2  487.54  1716.2  481.87  1771.2  485.36
  1896.3   462.8 1977.06  439.25 1999.35  441.43 2035.87  432.24 2142.18  439.71
 2200.84  455.02  2278.9  463.92  2353.9  482.03  2673.8  473.19  2998.5  482.41
  3221.1   475.5  3535.4  476.89  4687.3  493.94  5029.1  514.87  5411.8  496.89
  5741.4  518.95  5973.4  518.07  6248.1   546.3    6446  579.87  7055.3  749.31
#Mann= 3 , 0 , 0
       0      .1       0  1896.3    .035       0  2278.9      .1       0
#XS Ineff= 2 , 0
                         2354.15          482.03
Permanent Ineff=
       F       F
Bank Sta=1896.3,2278.9
XS Rating Curve= 0 ,0
Exp/Cntr=0.3,0.1

Type RM Length L Ch R = 1 ,865.689 ,0,0,0
BEGIN DESCRIPTION:
173.0832
END DESCRIPTION:
XS GIS Cut Line= 6
      1984141.05       693805.351985937.95991114693377.134119011
1986350.29012981693742.4420969811987457.01629575694235.903808821
1989575.14405309696072.9140171921990545.09038014697023.607617642
#Sta/Elev= 30
       0  694.41   288.4  688.63   506.9  652.39   532.5  628.34   553.1  589.88
   571.1   583.5   591.6  556.26   753.5  556.97   763.8  576.86   799.8   585.7
   838.4  622.73    1414  538.98  1550.2  542.63  1640.2  523.73  1778.9   461.5
  1892.1  462.64    1959  438.74  2023.9  434.14  2272.9  460.46  2623.6  482.94
  3131.1  474.36  5926.3  485.17  6068.6   502.4  6244.6   550.8  6352.1   564.5
  6492.2  571.73  6727.4  558.83  6925.6  575.87  7220.8  632.92    7779  772.07
#Mann= 3 , 0 , 0
       0      .1       0  1892.1    .035       0  2272.9      .1       0
Bank Sta=1892.1,2272.9
XS Rating Curve= 0 ,0
Exp/Cntr=0.3,0.1
Stream Node=Caney Fork      ,Reach - 1       , 0 , 0 ,Upstream end
Stream Node=Caney Fork      ,Reach - 1       , 0 , 1 ,Downstream end
LCMann Table=0

Chan Stop Cuts=-1
Use User Specified Reach Order=0
Composite Channel Slope=5