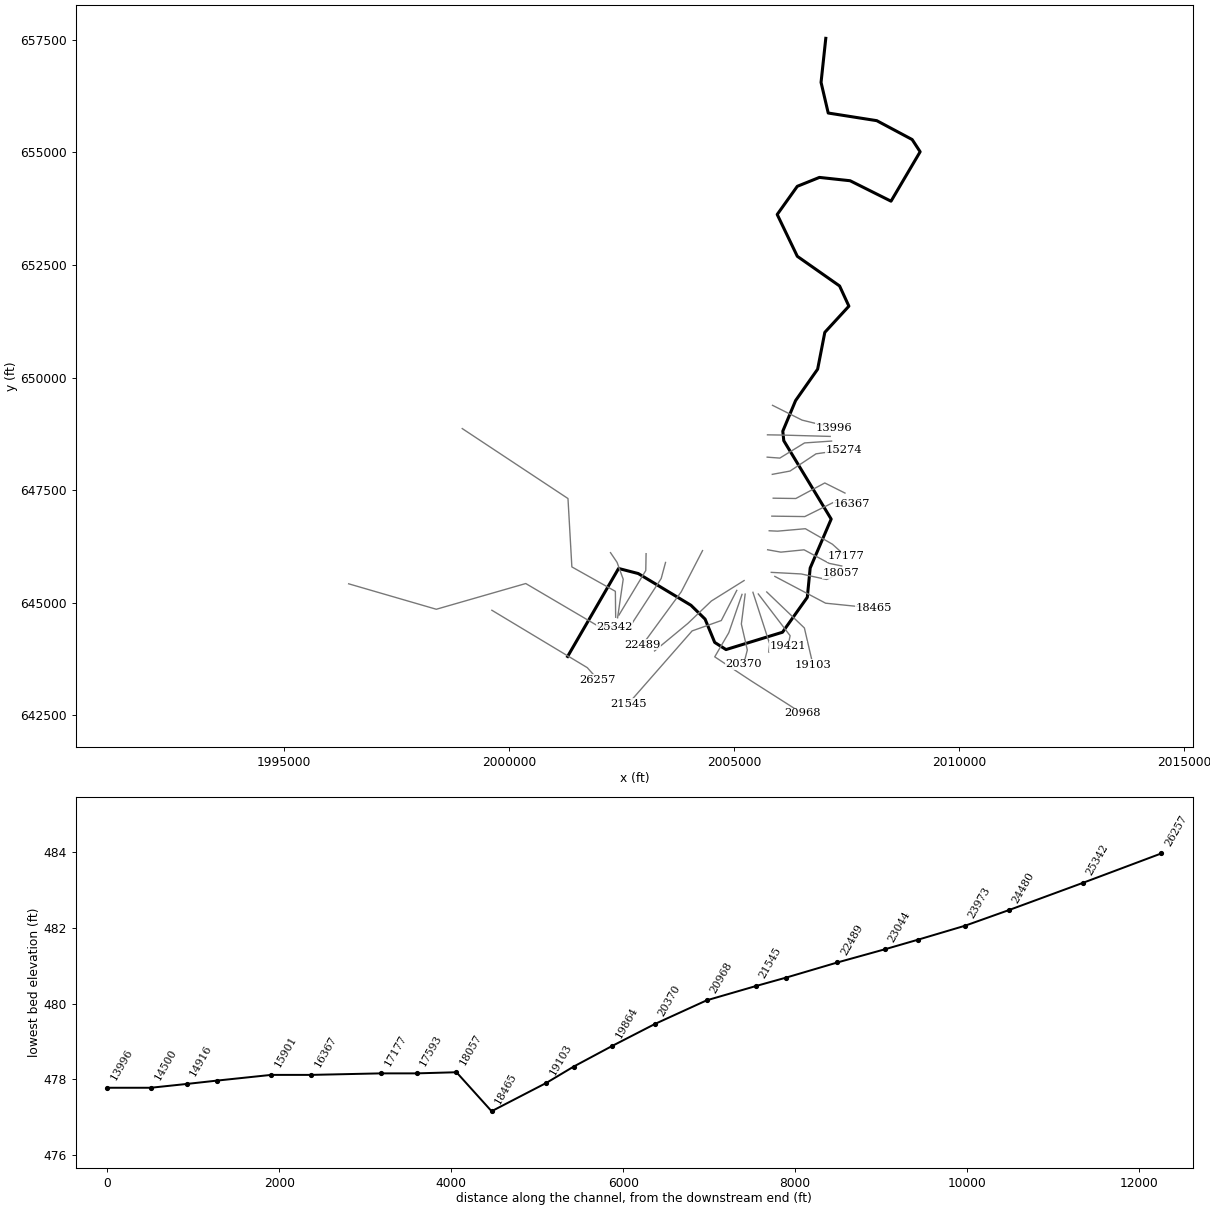
--- SmithFork2019.prj (project) ---

Proj Title=Smith County FPMS Study 2019
Current Plan=p01
Default Exp/Contr=0.3,0.1
English Units
Geom File=g07
Geom File=g02
Flow File=f04
Flow File=f06
Plan File=p01
Background Map Layer=Google Map
Background Map Layer=Google Satellite
Y Axis Title=Elevation
X Axis Title(PF)=Main Channel Distance
X Axis Title(XS)=Station
BEGIN DESCRIPTION:
Smith Fork River
END DESCRIPTION:
DSS File=dss
DSS Export Rating Curves= 0
DSS Export Rating Curve Sorted= 0
DSS Export Volume Flow Curves= 0
DXF Filename=..\Lancaster_HEC-RAS_5_0_3\HEC-RAS_5_0_3\Smith Fork River.
DXF OffsetX= 0
DXF OffsetY= 0
DXF ScaleX= 1
DXF ScaleY= 10

--- SmithFork2019.p01 (plan) ---

Plan Title=2019 Smith Fork 2019 Revision
Program Version=5.07
Short Identifier=2019Revision
Geom File=g07
Flow File=f04
Subcritical Flow
K Sum by GR= 0
Std Step Tol= 0.01
Critical Tol= 0.01
Num of Std Step Trials= 20
Max Error Tol= 0.3
Flow Tol Ratio= 0.001
Split Flow NTrial= 30
Split Flow Tol= 0.02
Split Flow Ratio= 0.02
Log Output Level= 0
Friction Slope Method= 1
Unsteady Friction Slope Method= 2
Unsteady Bridges Friction Slope Method= 1
Parabolic Critical Depth
Global Vel Dist= 0 , 0 , 0
Global Log Level= 0
CheckData=True
Encroach Param=-1 ,0,0, 2
Encroach River=Smith Fork River
Encroach Reach=Reach-1
Encroach Node=26257
       1  1618.8 2420.95
Encroach Node=25342
       1    5100    5972
Encroach Node=24480
       1    4600    5353
Encroach Node=23973
       1  302.67     900
Encroach Node=23424
       1     399    1000
Encroach Node=23044
       1     360    1000
Encroach Node=22489
       1    1008    1800
Encroach Node=21892
       1 1142.46    1950
Encroach Node=21545
       1     930    1750
Encroach Node=20968
       1   875.6    1500
Encroach Node=20370
       1     790    1247
Encroach Node=19864
       1     650 1172.51
Encroach Node=19421
       1     500    1125
Encroach Node=19103
       1     400    1050
Encroach Node=18465
       1     450    1175
Encroach Node=18057
       1     625    1200
Encroach Node=17593
       1     670    1380
Encroach Node=17177
       1     550    1430
Encroach Node=16367
       1     375    1321
Encroach Node=15901
       1     275  1126.1
Encroach Node=15274
       1     175    1025
Encroach Node=14916
       1  240.19    1050
Encroach Node=14500
       1     215     950
Encroach Node=13996
       1   316.9     930
Encroach Node=13527
       1     131     620
Encroach Node=13056
       1     440     890
Encroach Node=11972
       1   504.8    1100
Encroach Node=11529
       1     430     950
Encroach Node=11142
       1     580    1065
Encroach Node=10509
       1     600  1001.3
Encroach Node=10215
       1     475     940
Encroach Node=9984
       1     530    1000
Encroach Node=9677
       1    2430    3200
Encroach Node=9185
       1    5000 5822.59
Encroach Node=8527
       1    4449  5147.8
Encroach Node=7992
       1     198     700
Encroach Node=7500
       1     186     700
Encroach Node=7072
       1     230     700
Encroach Node=6510
       1     250     700
Encroach Node=5841
       1     500    1200
Encroach Node=5085
       1     650  1270.8
Encroach Node=3987
       1  975.76    1607
Encroach Node=2952
       1     550    1140
Encroach Node=2425
       1     700    1300
Encroach Node=2017
       1     600    1300
Encroach Node=1331
       1   225.1     850
Encroach Node=682
       1   105.5     450
Encroach Node=512
       1   172.4     450
Encroach Node=391
       1  185.84   454.1
Encroach Node=350
       1   315.3     730
Computation Interval=1MIN
Output Interval=1HOUR
Instantaneous Interval=1HOUR
Mapping Interval=1HOUR
Computation Time Step Use Courant=        0
Computation Time Step Use Time Series=    0
Computation Time Step Count To Double=0
Computation Time Step Max Doubling=0
Computation Time Step Max Halving=0
Computation Time Step Residence Courant=0
Run HTab= 0
Run UNet= 0
Run Sediment= 0
Run PostProcess= 0
Run WQNet= 0
Run RASMapper= 0
UNET Theta= 1
UNET Theta Warmup= 1
UNET ZTol= 0.02
UNET ZSATol= 0.02
UNET MxIter= 20
UNET Max Iter WO Improvement= 0
UNET MaxInSteps= 0
UNET DtIC= 0
UNET DtMin= 0
UNET MaxCRTS= 20
UNET WFStab= 2
UNET SFStab= 1
UNET WFX= 1
UNET SFX= 1
UNET 1D Methodology=Finite Difference
UNET DSS MLevel= 4
UNET Pardiso=0
UNET DZMax Abort= 100
UNET Use Existing IB Tables=-1
UNET Froude Reduction=False
UNET Froude Limit= 0.8
UNET Froude Power= 4
UNET D1 Cores= 0
UNET D2 Coriolis=0
UNET D2 Cores= 0
UNET D2 Theta= 1
UNET D2 Theta Warmup= 1
UNET D2 Z Tol= 0.01
UNET D2 Volume Tol= 0.01
UNET D2 Max Iterations= 20
UNET D2 Equation= 0
UNET D2 RampUpFraction=0.1
UNET D2 TimeSlices= 1
UNET D2 BCVolumeCheck=0
UNET D1D2 MaxIter= 0
UNET D1D2 ZTol=0.01
UNET D1D2 QTol=0.1
UNET D1D2 MinQTol=1
Write IC File= 0
Write IC File at Fixed DateTime=0
Write IC File at Sim End=0
Echo Input=False
Echo Parameters=False
Echo Output=False
Write Detailed= 0
HDF Write Warmup=0
HDF Write Time Slices=0
HDF Flush=0
HDF Face Node Velocities=0
HDF Compression= 1
HDF Chunk Size= 1
HDF Spatial Parts= 1
HDF Use Max Rows=0
HDF Fixed Rows= 1
Calibration Method= 0
Calibration Iterations= 20
Calibration Max Change=0.05
Calibration Tolerance=0.2
Calibration Maximum=1.5
Calibration Minimum=0.5
Calibration Optimization Method= 1
WQ AD Non Conservative
WQ ULTIMATE=-1
WQ Max Comp Step=1HOUR
WQ Output Interval=15MIN
WQ Output Selected Increments= 0
WQ Output face flow=0
WQ Output face velocity=0
WQ Output face area=0
WQ Output face dispersion=0
WQ Output cell volume=0
WQ Output cell surface area=0
WQ Output cell continuity=0
WQ Output cumulative cell continuity=0
WQ Output face conc=0
WQ Output face dconc_dx=0
WQ Output face courant=0
WQ Output face peclet=0
WQ Output face adv mass=0
WQ Output face disp mass=0
WQ Output cell mass=0
WQ Output cell source sink temp=0
WQ Output nsm pathways=0
WQ Output nsm derived pathways=0
WQ Output MaxMinRange=-1
WQ Daily Max Min Mean=-1
WQ Daily Range=0
WQ Daily Time=0
WQ Create Restart=0
WQ Fixed Restart=0
WQ System Summary=0
WQ Write To DSS=0
WQ Use Fixed Temperature=0
Sorting and Armoring Iterations= 10
XS Update Threshold= 0.02
Bed Roughness Predictor= 0
Hydraulics Update Threshold= 0.02
Energy Slope Method= 1
Volume Change Method= 1
Sediment Retention Method= 0
XS Weighting Method= 0
Number of US Weighted Cross Sections= 1
Number of DS Weighted Cross Sections= 1
Upstream XS Weight=0
Main XS Weight=1
Downstream XS Weight=0
Number of DS XS's Weighted with US Boundary= 1
Upstream Boundary Weight= 1
Weight of XSs Associated with US Boundary= 0
Number of US XS's Weighted with DS Boundary= 1
Downstream Boundary Weight= 0.5
Weight of XSs Associated with DS Boundary= 0.5
Percentile Method= 0
Sediment Output Level= 3
Mass or Volume Output= 0
Output Increment Type= 1
Profile and TS Output Increment= 1
XS Output Flag= 0
XS Output Increment= 10
Write Gradation File= 0
Read Gradation Hotstart= 0
Write HDF5 File= 1
Write Binary Output= 1
Write DSS Sediment File= 0
SV Curve= 0
Specific Gage Flag= 0

--- SmithFork2019.f04 (steady flow) ---

Flow Title=2019 Smith Fork Flows
Program Version=5.07
Number of Profiles= 9
Profile Names=100-year,Floodway,2-year,5-year,10-year,25-year,50-year,200-year,500-year
River Rch & RM=Smith Fork River,Reach-1         ,26257
   36044   36044   11168   17236   21706   27281   31540   40653   47288
River Rch & RM=Smith Fork River,Reach-1         ,11972
   36990   36990   11461   17688   22275   27997   32368   41720   48529
Boundary for River Rch & Prof#=Smith Fork River,Reach-1         , 1
Up Type= 0
Dn Type= 3
Dn Slope=0.00024
Boundary for River Rch & Prof#=Smith Fork River,Reach-1         , 2
Up Type= 0
Dn Type= 3
Dn Slope=0.00024
DSS Import GetInterval= 0
DSS Import GetPeak= 0
DSS Import FillOption= 0

--- SmithFork2019.f06 (steady flow) ---

Flow Title=2019 Caney Flow Normal Depth
Program Version=5.07
Number of Profiles= 2
Profile Names=100-year,Floodway
River Rch & RM=Caney Fork,1               ,26.95
   30000   30000
River Rch & RM=Caney Fork,1               ,20.56
   49966   49966
River Rch & RM=Caney Fork,1               ,16.05
   75887   75887
River Rch & RM=Caney Fork,1               ,11.92
   85646   85646
River Rch & RM=Caney Fork,1               ,0.16
   93534   93534
Boundary for River Rch & Prof#=Caney Fork,1               , 1
Up Type= 0
Dn Type= 3
Dn Slope=0.00035
Boundary for River Rch & Prof#=Caney Fork,1               , 2
Up Type= 0
Dn Type= 3
Dn Slope=0.00035
Observed WS=Caney Fork      ,1               ,14.91   ,0.05,492,
Observed WS=Caney Fork      ,1               ,11.4    ,0,491.3,
Observed WS=Caney Fork      ,1               ,7.7     ,0,488,
Observed WS=Caney Fork      ,1               ,3.37    ,0,486.3,
DSS Import GetInterval= 0
DSS Import GetPeak= 0
DSS Import FillOption= 0

--- SmithFork2019.g07 (geometry) ---

Geom Title=Existing Conditions 2019 Smith Fork
Program Version=5.07

River Reach=Smith Fork River,Reach-1
Reach XY= 30
      2001306.61       643804.16      2002438.69       645758.88
      2002875.81        645646.1      2004046.59       644941.27
      2004359.98       644633.87      2004573.73        644116.3
      2004825.25       643957.54      2006080.06       644342.52
      2006630.58       645118.15      2006694.56       645768.01
      2007160.99       646855.98      2006108.02       648597.39
      2006086.44       648808.57      2006370.65       649488.49
      2006860.36       650186.42      2007019.68       651003.83
      2007554.54       651585.51      2007347.97       652034.15
      2006408.92       652692.74       2005962.2       653622.08
       2006408.2       654247.54      2006899.99       654445.54
      2007581.18       654371.52      2008490.35       653917.24
      2009137.22       655015.27       2008959.7        655286.7
      2008174.07       655705.83      2007095.34       655875.54
      2006936.14       656556.53      2007041.22        657534.7

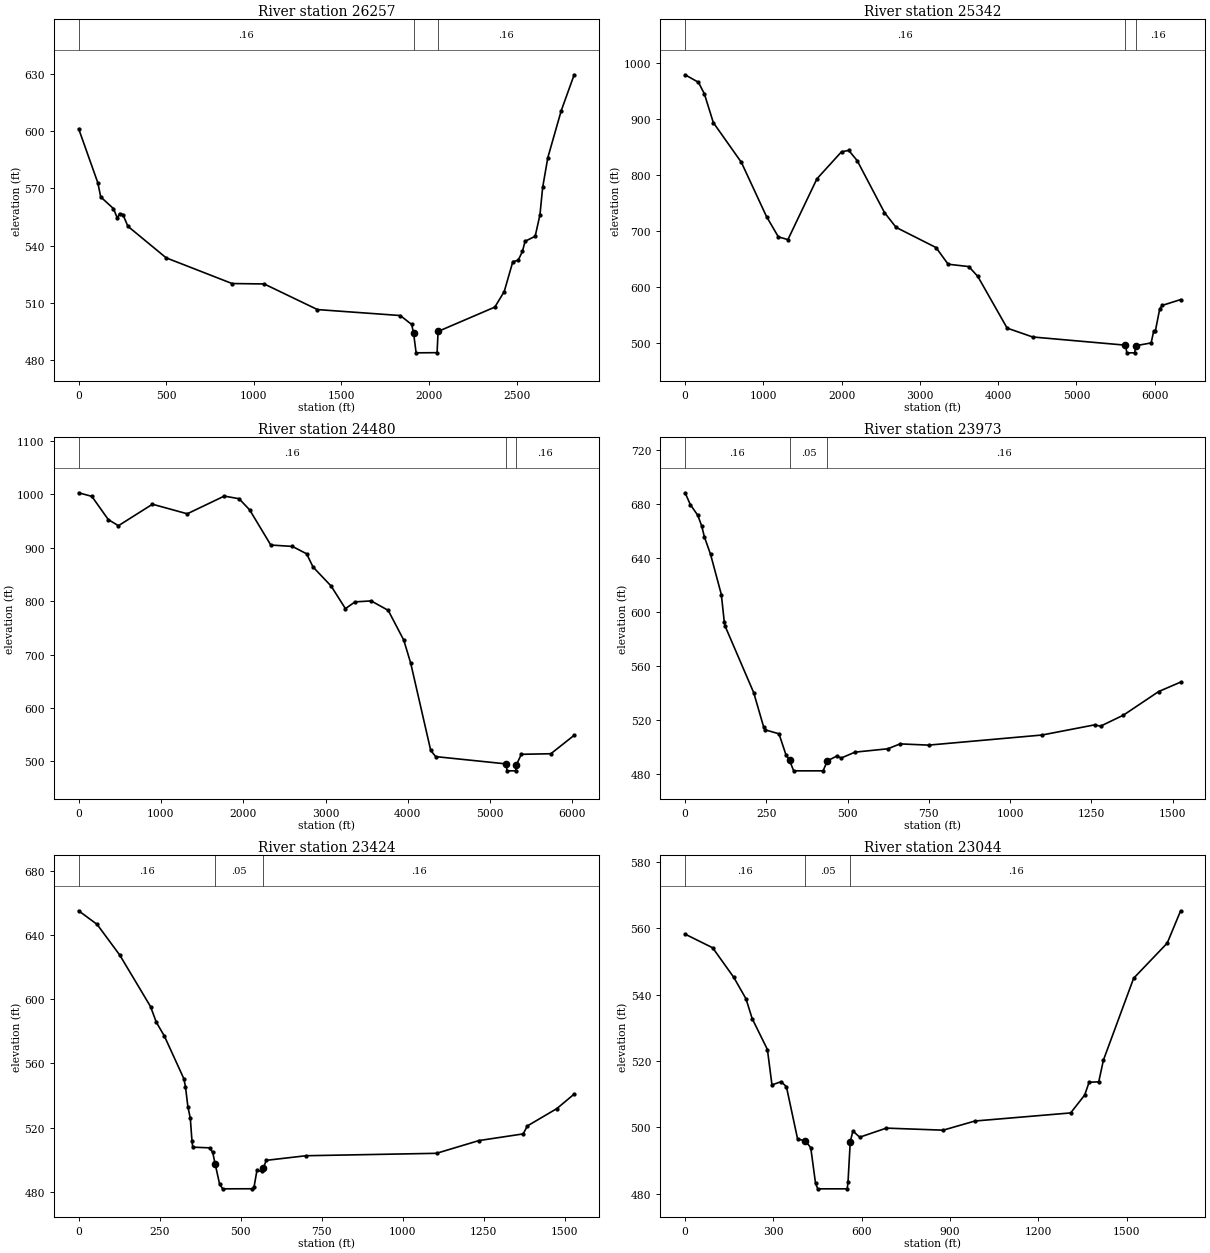
Type RM Length L Ch R = 1 ,26257   ,911.8,915.6,914.1
BEGIN DESCRIPTION:
Smith Fork River 51.0
END DESCRIPTION:
XS GIS Cut Line= 3
      1999623.89       644830.742001743.37231625643555.712142098
      2001978.94       643291.12
#Sta/Elev= 30
       0   601.3   109.7  572.94   126.1  565.57   198.6  559.49   220.8  554.48
   233.5  556.84   252.9  556.36   280.9  550.23   499.5   533.7   875.5  520.25
  1058.8  520.03  1362.7  506.62  1835.3   503.5  1900.4  498.82  1911.2  494.35
  1925.8  483.97  2045.4  484.06  2051.2  495.18  2375.1  507.92  2428.6  516.06
  2477.7  531.72  2507.8  532.38  2532.6  537.07  2547.5  542.38  2605.2  544.97
  2632.4  556.24  2647.9  570.59  2677.5  586.22  2753.9  610.75  2827.7  629.53
#Mann= 3 , 0 , 0
       0     .16       0  1911.2     .06       0  2051.2     .16       0
Bank Sta=1911.2,2051.2
XS Rating Curve= 0 ,0
Exp/Cntr=0.3,0.1

Type RM Length L Ch R = 1 ,25342   ,858.1,862,859.4
BEGIN DESCRIPTION:
Smith Fork River 50.0
END DESCRIPTION:
XS GIS Cut Line= 5
1996442.58039452645418.2461622541998389.59049417644852.824888781
2000376.62728342645424.3177706452002009.89569213644463.661398372
      2002350.86       644466.43
#Sta/Elev= 30
       0  978.31   170.8   964.9   246.3  944.32   360.8   893.1   718.5  822.52
  1040.3  725.82  1191.2  689.75  1313.6   684.8    1684  793.03  1998.7  841.26
    2091  843.62  2198.6  825.44  2547.2  732.95  2695.5  706.61  3206.1  670.65
  3360.5  640.98  3624.1  636.81  3738.6  619.47  4114.3  527.22  4440.1  511.43
  5626.4  496.83  5643.8  483.19  5742.4  483.19  5761.6  495.99  5954.1  500.83
    5986  521.47  6009.1  522.94  6064.1  561.72  6097.4  567.73  6330.9  578.02
#Mann= 3 , 0 , 0
       0     .16       0  5626.4     .06       0  5761.6     .16       0
Bank Sta=5626.4,5761.6
XS Rating Curve= 0 ,0
Exp/Cntr=0.3,0.1

Type RM Length L Ch R = 1 ,24480   ,582.1,506.2,451.1
BEGIN DESCRIPTION:
Smith Fork River 49.0
END DESCRIPTION:
XS GIS Cut Line= 5
  1998965.900086648866.3615901662001314.66968146647312.145397667
2001401.03152972645793.3493385662002367.13254763645251.268924863
      2002373.97       644675.39
#Sta/Elev= 30
       0 1002.63   160.3  995.94   360.2  952.51   483.4  941.02   897.1  981.21
  1320.1  963.31  1769.5  996.43  1949.4  991.53  2078.3  970.61  2334.9  904.88
  2597.6  902.28  2770.4  888.49  2848.3  863.81  3068.7  828.04  3241.6   785.9
  3359.1  798.56  3554.4  800.34  3761.5   782.7  3950.8  726.97  4035.2  683.82
  4278.1  520.72  4338.4  509.08  5188.6  495.56  5198.3  494.79    5204  482.47
  5310.1   482.5  5319.3493.5689  5378.9   513.4  5737.9  514.47  6021.4  548.94
#Mann= 3 , 0 , 0
       0     .16       0  5188.6     .05       0  5319.3     .16       0
Bank Sta=5188.6,5319.3
XS Rating Curve= 0 ,0
Exp/Cntr=0.3,0.1

Type RM Length L Ch R = 1 ,23973   ,634.3,548.9,497.9
BEGIN DESCRIPTION:
Smith Fork River 48.0
END DESCRIPTION:
XS GIS Cut Line= 4
 2002259.0570305646110.2680811052002405.12971224645894.469827772
2002541.53169569645519.865119778      2002416.56       644663.25
#Sta/Elev= 30
       0  688.57    16.1  679.77    39.1  671.81    51.2  663.82    59.3  655.87
    78.4  642.79   111.5  613.01   120.6  592.54   123.6  589.27   211.2  540.07
   241.4  514.92   247.4  512.44   288.9  509.57   310.2  494.09   321.5  489.75
   334.1  482.06   424.6  482.06   437.9  489.51   467.1  493.07   480.4  491.58
     523  495.95   623.8  498.44   661.6  502.07   749.2  501.16  1098.3  508.66
    1260   516.2  1278.3  515.23  1348.9  523.43  1457.3  540.95  1524.9  547.97
#Mann= 3 , 0 , 0
       0     .16       0   321.5     .05       0   437.9     .16       0
Bank Sta=321.5,437.9
XS Rating Curve= 0 ,0
Exp/Cntr=0.3,0.1

Type RM Length L Ch R = 1 ,23424   ,384.2,380.2,377.9
BEGIN DESCRIPTION:
Smith Fork River 47.0
END DESCRIPTION:
XS GIS Cut Line= 3
      2003049.51       646087.38 2003042.7423326645713.143399559
        2002447.       644724.12
#Sta/Elev= 30
       0  655.38      57  646.88     127  627.67     222  595.49   239.5  585.81
   264.5  577.15   324.6  550.49   329.6   545.6   337.1  532.93   344.6  525.75
   349.6  511.82   352.1  507.72   403.8   507.3   413.6  504.43   421.3  497.17
   434.7  484.84   444.4  481.69   535.6  481.74   541.1  482.72   550.2  493.27
   564.3  492.55   569.8494.6333   578.9  499.49   701.4  502.37  1104.2  503.88
    1235  511.84  1371.6  516.01  1384.4  520.97  1475.5  531.82  1528.9  540.88
#Mann= 3 , 0 , 0
       0     .16       0   421.3     .05       0   569.8     .16       0
Bank Sta=421.3,569.8
XS Rating Curve= 0 ,0
Exp/Cntr=0.3,0.1

Type RM Length L Ch R = 1 ,23044   ,533.8,555.4,528.7
BEGIN DESCRIPTION:
Smith Fork River 46.0
END DESCRIPTION:
XS GIS Cut Line= 3
      2003481.63       645892.622003384.86701414645535.377014144
2002669.63574033644434.672555801
#Sta/Elev= 30
       0   558.2    93.6  554.09   165.5  545.15   206.9  538.69   227.7  532.76
   279.5  523.43     295  512.76   326.1  513.74   344.1  512.21     382  496.47
   408.3  495.89   426.7  493.84     443  483.07   450.6  481.44   550.5  481.44
   553.2   483.4   560.9   495.7   569.9  498.86     593     497   683.3  499.74
   876.3  499.12   984.3  501.88  1309.3  504.32    1357  509.71  1371.8  513.55
  1404.7   513.7  1420.6  520.24  1523.2  544.91  1637.2  555.49  1682.8  565.24
#Mann= 3 , 0 , 0
       0     .16       0   408.3     .05       0   560.9     .16       0
Bank Sta=408.3,560.9
XS Rating Curve= 0 ,0
Exp/Cntr=0.3,0.1

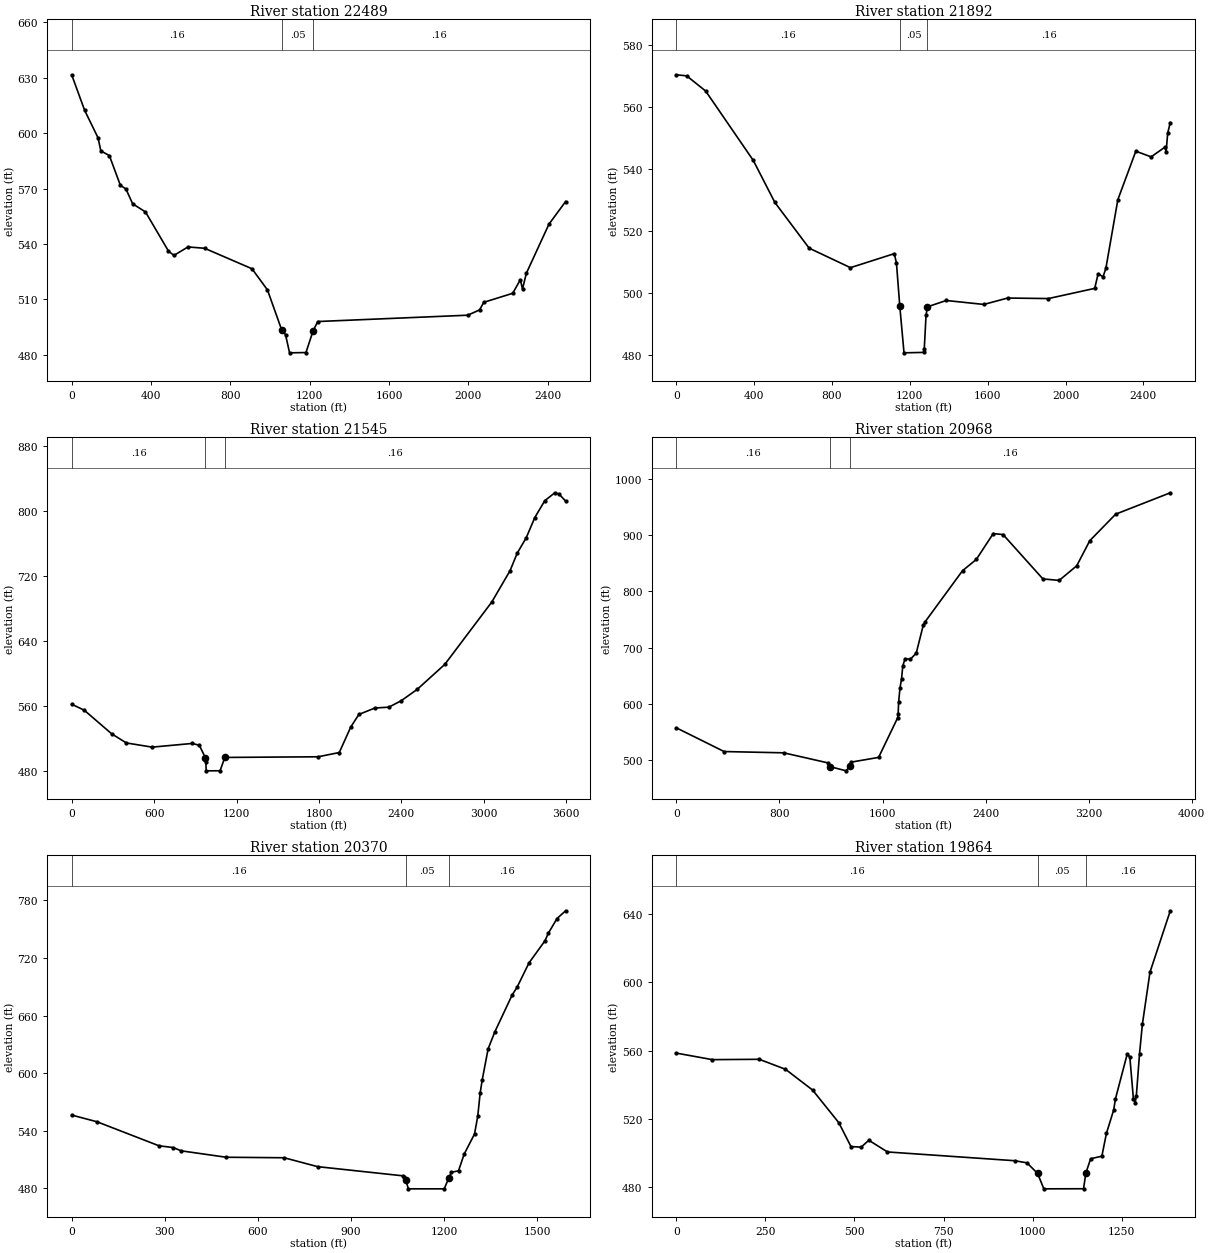
Type RM Length L Ch R = 1 ,22489   ,616.6,596.8,587.5
BEGIN DESCRIPTION:
Smith Fork River 45.0
END DESCRIPTION:
XS GIS Cut Line= 3
      2004303.76       646156.032003830.16574033645239.690206851
2002967.69892486644062.692779004
#Sta/Elev= 30
       0  631.59    65.5  612.32     133  597.46   147.1  590.35   189.9  587.89
   245.6  571.77   273.7  569.77   307.5  561.76   372.2  557.35   488.2  536.15
   515.7  533.82   586.5  538.41     670  537.69   909.3   526.6   987.3  515.14
  1058.6  493.62  1078.3  490.97  1098.8  481.09  1181.4  481.25  1217.9 493.146
  1241.1  498.04  1997.4  501.46  2056.7  504.33  2078.2  508.44  2223.9  513.31
  2262.4  520.62  2273.5  515.67  2292.8  524.17  2406.7  550.72  2490.7  562.98
#Mann= 3 , 0 , 0
       0     .16       0  1058.6     .05       0  1217.9     .16       0
Bank Sta=1058.6,1217.9
XS Rating Curve= 0 ,0
Exp/Cntr=0.3,0.1

Type RM Length L Ch R = 1 ,21892   ,418.1,346.8,318.5
BEGIN DESCRIPTION:
Smith Fork River 44.0
END DESCRIPTION:
XS GIS Cut Line= 4
      2005226.67       645490.482004499.78168752645036.204028289
2003979.93813347644540.257138704      2003238.22       643926.84
#Sta/Elev= 30
       0   570.5    53.2  570.15   150.5  565.25   395.2  542.84   506.3  529.25
   682.3   514.5   894.6   508.2    1120  512.73  1131.1  509.62 1147.98495.8334
  1169.8  480.69  1270.3  480.83  1273.8  481.86  1283.1   492.9  1290.3495.5524
  1386.8   497.6    1580  496.32  1702.2  498.39  1911.8  498.22  2149.7  501.51
  2167.5  506.27  2192.3  505.22    2207  507.95  2268.7  530.18    2361  545.82
  2439.7  543.99  2509.1  547.06  2516.9  545.72  2524.7  551.66  2538.1  555.07
#Mann= 3 , 0 , 0
       0     .16       0 1147.98     .05       0  1290.3     .16       0
Bank Sta=1147.98,1290.3
XS Rating Curve= 0 ,0
Exp/Cntr=0.3,0.1

Type RM Length L Ch R = 1 ,21545   ,491.7,577.1,624.3
BEGIN DESCRIPTION:
Smith Fork River 43.0
END DESCRIPTION:
XS GIS Cut Line= 4
      2005064.08        645271.92004720.35849481644602.533821437
2004071.85302186644371.7465099742002651.76600174642751.367425368
#Sta/Elev= 30
       0  562.49    91.6  555.13   291.2  526.05     398  514.82   585.6  509.66
   875.9  514.17     929   512.1   974.1  496.23   976.7  490.95   979.4  480.47
  1080.2  480.56  1114.7  496.97    1794  497.78  1947.9  503.03  2031.9  534.53
  2090.8  549.94  2207.4  557.84  2308.3  558.87  2397.1   566.6  2514.7  580.72
  2715.8   611.5  3058.2  688.39  3191.2  726.99  3242.9   748.4  3309.2   767.6
  3371.2  792.37  3443.9  813.12  3516.9  822.87  3546.8  821.37  3595.4   812.7
#Mann= 3 , 0 , 0
       0     .16       0   974.1     .05       0  1114.7     .16       0
Bank Sta=974.1,1114.7
XS Rating Curve= 0 ,0
Exp/Cntr=0.3,0.1

Type RM Length L Ch R = 1 ,20968   ,497.8,598.1,667.6
BEGIN DESCRIPTION:
Smith Fork River 42.0
END DESCRIPTION:
XS GIS Cut Line= 5
2005180.38020685645183.187237348  2004886.831699644331.916725001
2004574.47086011643795.8187343642005387.09943123643259.763021326
2006516.50845819642540.095525695
#Sta/Elev= 30
       0  556.77   370.5  514.49   833.3  512.22    1176  494.31  1194.3   487.5
  1318.1  480.09  1344.2  488.11  1356.5  495.62  1569.7  504.06  1718.1  574.91
  1721.5  581.64  1724.9  602.01  1735.7  627.86  1748.1   644.7  1757.3  667.03
    1775  679.92  1816.9  679.17  1861.9  690.06  1915.8  739.32  1930.7  745.88
  2221.1  836.96  2327.6  856.94  2459.3   903.1  2535.6  901.42  2844.9  822.31
  2971.1  819.65  3107.4  845.71  3208.8  890.47  3409.8  937.76  3833.6   975.9
#Mann= 3 , 0 , 0
       0     .16       0  1194.3     .05       0  1344.2     .16       0
Bank Sta=1194.3,1344.2
XS Rating Curve= 0 ,0
Exp/Cntr=0.3,0.1

Type RM Length L Ch R = 1 ,20370   ,495.6,505.7,510.6
BEGIN DESCRIPTION:
Smith Fork River 41.0
END DESCRIPTION:
XS GIS Cut Line= 4
2005250.44169569645189.314896574 2005165.6401938644524.937990637
2005298.14765105643947.518089281       2005216.2       643628.63
#Sta/Elev= 30
       0  556.35    82.1  549.29   281.2  524.33   326.6   522.5   353.4  519.04
   497.9  512.38   684.7  511.85   792.4  502.59  1066.9  493.04    1072  492.27
  1076.3  488.79  1084.8  479.47  1200.3  479.47  1215.6491.2052  1223.3  496.64
  1246.4  498.28  1264.4  515.52    1298  536.63  1308.4  555.22    1316  578.99
  1322.7  592.94  1341.8  625.35  1363.7  643.25  1419.2  681.45  1434.8  689.36
  1473.5  714.87  1525.1  737.98  1535.4  745.57  1563.8  761.08  1591.4  769.16
#Mann= 3 , 0 , 0
       0     .16       0  1076.3     .05       0  1215.6     .16       0
Bank Sta=1076.3,1215.6
XS Rating Curve= 0 ,0
Exp/Cntr=0.3,0.1

Type RM Length L Ch R = 1 ,19864   ,405.2,443.7,460.9
BEGIN DESCRIPTION:
Smith Fork River 40.0
END DESCRIPTION:
XS GIS Cut Line= 3
      2005423.14       645229.25 2005794.5829695644082.833407734
2005773.80403646643902.482340773
#Sta/Elev= 30
       0  558.54   101.1  554.71   232.7  554.91   306.3  549.06   382.5  536.85
   456.1  517.68   490.2  503.67   519.1  503.38   540.2   507.4   592.7  500.53
   950.1  495.38   984.3  494.13  1014.1  487.92  1031.6  478.88  1143.1  478.93
  1149.5  488.09    1163  496.54  1194.5  498.05  1207.3  511.42  1227.7  525.18
  1232.7  531.73  1265.4  557.76    1273  556.37  1283.1  531.59  1288.1   529.4
  1291.3   533.5  1300.3  558.23  1308.2   575.4  1329.6  606.05  1386.6  642.08
#Mann= 3 , 0 , 0
       0     .16       0  1014.1     .05       0  1149.5     .16       0
Bank Sta=1014.1,1149.5
XS Rating Curve= 0 ,0
Exp/Cntr=0.3,0.1

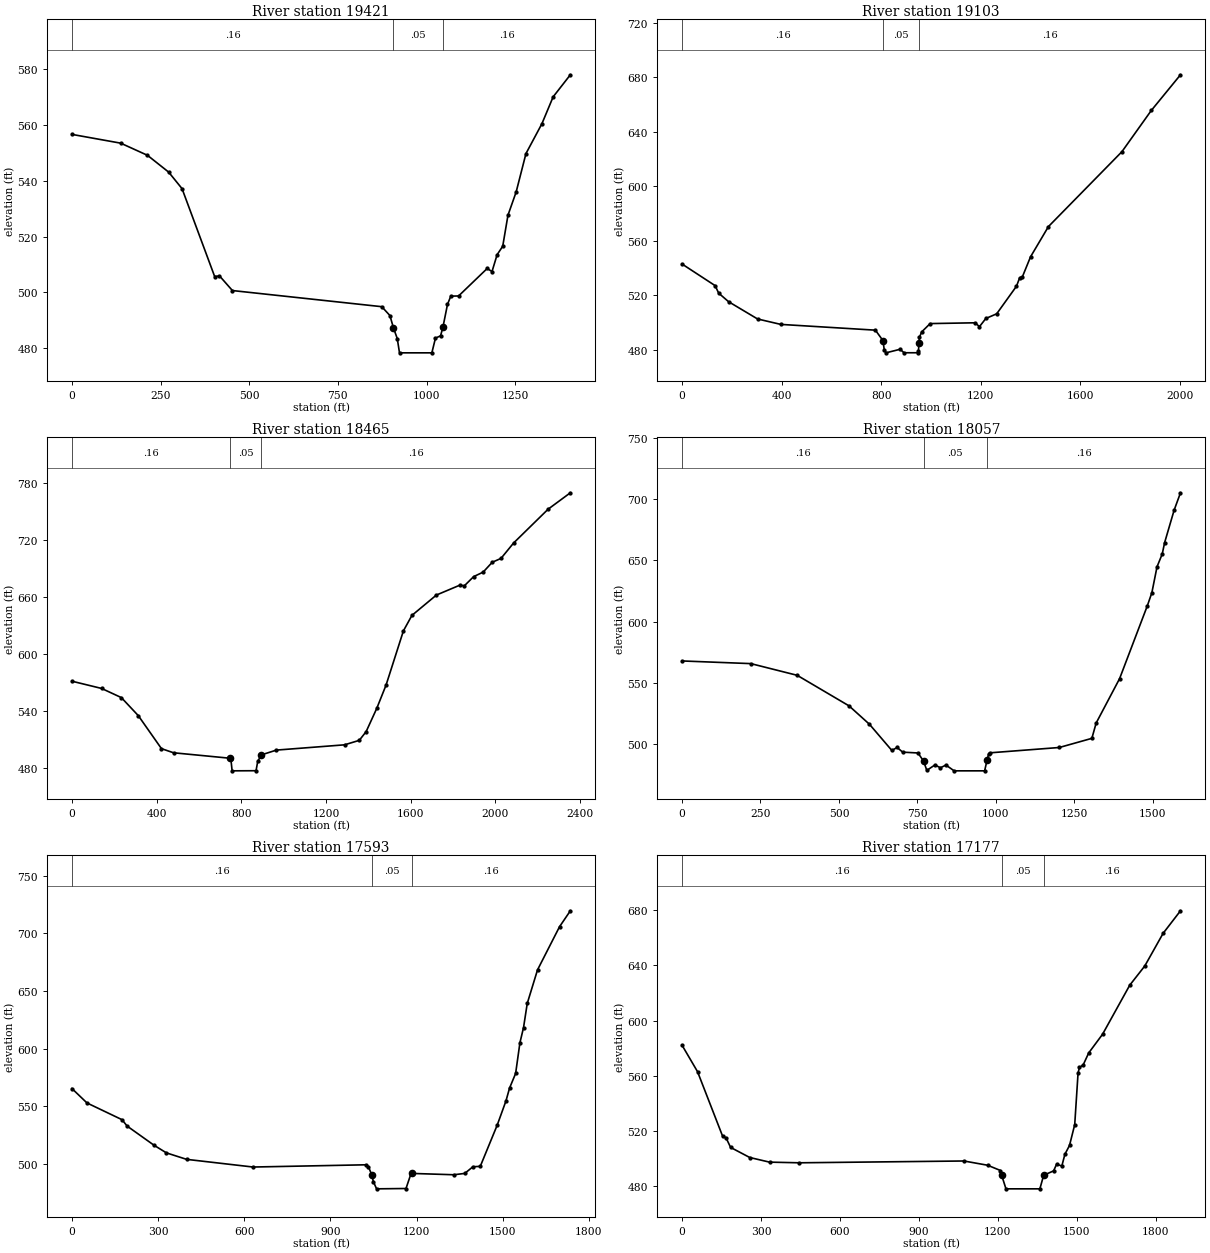
Type RM Length L Ch R = 1 ,19421   ,300.7,317.2,326.8
BEGIN DESCRIPTION:
Smith Fork River 39.0
END DESCRIPTION:
XS GIS Cut Line= 3
2005541.73085193645192.218089281 2006248.5729695644265.586600442
      2006202.16       644030.29
#Sta/Elev= 30
       0  556.58   137.5  553.44     213  549.09   272.7  543.08   310.5  537.15
   402.5  505.66   416.1   505.9   452.5  500.65   873.6  494.87   896.6  491.69
   906.6  487.25   917.3  483.45   923.6  478.34  1014.8  478.34    1025  483.61
  1039.3  484.43  1045.9487.4427  1058.9  495.69  1068.2  498.65  1090.2  498.71
  1170.8  508.55  1184.4  507.45  1198.8  513.49  1214.6  516.51  1229.4  527.63
  1252.5  535.97  1280.1   549.7  1325.1   560.4  1356.8  570.04  1405.3  577.93
#Mann= 3 , 0 , 0
       0     .16       0   906.6     .05       0  1045.9     .16       0
Bank Sta=906.6,1045.9
XS Rating Curve= 0 ,0
Exp/Cntr=0.3,0.1

Type RM Length L Ch R = 1 ,19103   ,611.8,638.1,652.7
BEGIN DESCRIPTION:
Smith Fork River 38.0
END DESCRIPTION:
XS GIS Cut Line= 3
2005729.78596354 645237.219371272006565.85743602 644436.94937127
      2006757.48       643613.62
#Sta/Elev= 30
       0     543   132.8  527.18   147.3  521.65     187  515.39   303.5  502.73
   396.9  498.75     777  494.53   807.1  486.92   812.5  480.13   819.2  477.91
     876  480.51     892  477.97   947.2  477.97   949.9  479.26   952.1  485.39
   953.8   489.3   962.7  493.22   996.9  499.35    1178  499.93  1194.9  497.08
  1220.6  503.09  1264.2  506.51  1343.8  526.75  1356.6  532.97  1366.9  533.37
  1400.2  548.27  1472.1  570.44  1767.4  625.33  1885.4  655.53  2002.7  681.69
#Mann= 3 , 0 , 0
       0     .16       0   807.1     .05       0   952.1     .16       0
Bank Sta=807.1,952.1
XS Rating Curve= 0 ,0
Exp/Cntr=0.3,0.1

Type RM Length L Ch R = 1 ,18465   ,377.5,408.8,422.9
BEGIN DESCRIPTION:
Smith Fork River 37.0
END DESCRIPTION:
XS GIS Cut Line= 3
      2005910.01       645582.272007037.31487205644987.511927071
      2008110.79       644878.17
#Sta/Elev= 30
       0  571.46   140.3  563.83   233.5  554.21   313.4  535.25   422.9  500.51
   479.9  496.16   746.4  490.42   750.8   489.1   756.5  477.16   869.5  477.29
   877.3  487.01   894.5493.9284   965.6  498.98  1287.2  504.52  1356.8  509.22
  1389.4  518.44  1439.7  542.99  1483.4  567.37  1565.3  624.41  1605.5  640.68
  1721.1  662.09  1832.3  672.52  1852.8  671.76    1897  681.46  1941.8   686.2
  1984.8  696.58  2026.2  700.65  2085.5  716.81  2248.8  752.44  2353.6  769.66
#Mann= 3 , 0 , 0
       0     .16       0   746.4     .05       0   894.5     .16       0
Bank Sta=746.4,894.5
XS Rating Curve= 0 ,0
Exp/Cntr=0.3,0.1

Type RM Length L Ch R = 1 ,18057   ,482.4,463.9,439.2
BEGIN DESCRIPTION:
Smith Fork River 36.0
END DESCRIPTION:
XS GIS Cut Line= 4
      2005830.14       645672.412006495.34224597645637.108140257
2007058.81253127645514.393837789      2007374.99645653.553192707
#Sta/Elev= 30
       0  567.92   219.2  565.74   366.9  556.19   532.2  531.23   597.3  516.19
   668.6  494.83   685.3  497.28   703.2  493.44   751.8  492.78   769.5  486.22
     780  478.56   805.6  482.97   823.5  480.71   840.9  482.92     867  478.19
   964.2  478.19   971.9  486.93     977  491.99   982.1  492.92  1202.1  497.25
  1305.9  504.72  1319.6  517.24  1394.2  553.45  1482.7  612.99  1497.1  623.65
  1513.5  644.78  1530.2   655.3  1537.7  664.51    1568  691.02  1588.3  705.23
#Mann= 3 , 0 , 0
       0     .16       0   769.5     .05       0   971.9     .16       0
Bank Sta=769.5,971.9
XS Rating Curve= 0 ,0
Exp/Cntr=0.3,0.1

Type RM Length L Ch R = 1 ,17593   ,416.6,415.9,412.3
BEGIN DESCRIPTION:
Smith Fork River 35.0
END DESCRIPTION:
XS GIS Cut Line= 5
2005749.76297523646174.3817104082006043.29086017646121.633992624
2006559.68266785646173.2783225812007115.21488022645872.788949391
2007395.98084376 645814.41341591
#Sta/Elev= 30
       0  565.28    52.6  552.73   174.6   538.2   192.3  532.66   286.3  515.96
   329.2  509.38   399.5  503.76   630.7   497.1    1024  499.04  1032.5  497.36
    1044  490.34  1049.6  484.44  1060.9  478.16  1163.3  478.45  1180.3  490.99
  1184.1  491.55  1329.8  490.39  1367.9  491.55  1396.2  497.33  1421.9  497.69
  1480.8  533.42  1511.5   554.6  1523.8  565.61    1545  578.36    1560  605.05
  1572.5  618.14  1585.5   639.2  1621.3  668.34  1697.9  705.79  1735.6  719.63
#Mann= 3 , 0 , 0
       0     .16       0    1044     .05       0  1184.1     .16       0
Bank Sta=1044,1184.1
XS Rating Curve= 0 ,0
Exp/Cntr=0.3,0.1

Type RM Length L Ch R = 1 ,17177   ,708.7,809.7,854.7
BEGIN DESCRIPTION:
Smith Fork River 34.0
END DESCRIPTION:
XS GIS Cut Line= 5
2005784.53106696646596.3504415012005968.83980056646587.642476803
2006587.25713437646642.0442534122007188.31956995646298.103630938
2007483.04979315646031.808312485
#Sta/Elev= 30
       0  582.23    58.9  563.06   154.7   516.1   167.2  515.15   184.7  508.17
   257.5  500.86   332.6  497.51   445.7  497.03  1071.7  498.34  1161.7  495.26
  1210.7  491.44  1214.6  488.32  1231.5  478.16  1360.4  478.16  1374.8  487.98
  1412.7  491.19  1423.8  495.93    1444  494.75  1455.5  503.19  1473.1  509.61
  1492.9   524.7  1505.6  562.12  1510.9  566.08  1525.1  567.96    1546  576.61
  1598.8  590.19  1702.1  625.73  1759.2  639.62    1829  663.31    1895  679.63
#Mann= 3 , 0 , 0
       0     .16       0  1214.6     .05       0  1374.8     .16       0
Bank Sta=1214.6,1374.8
XS Rating Curve= 0 ,0
Exp/Cntr=0.3,0.1

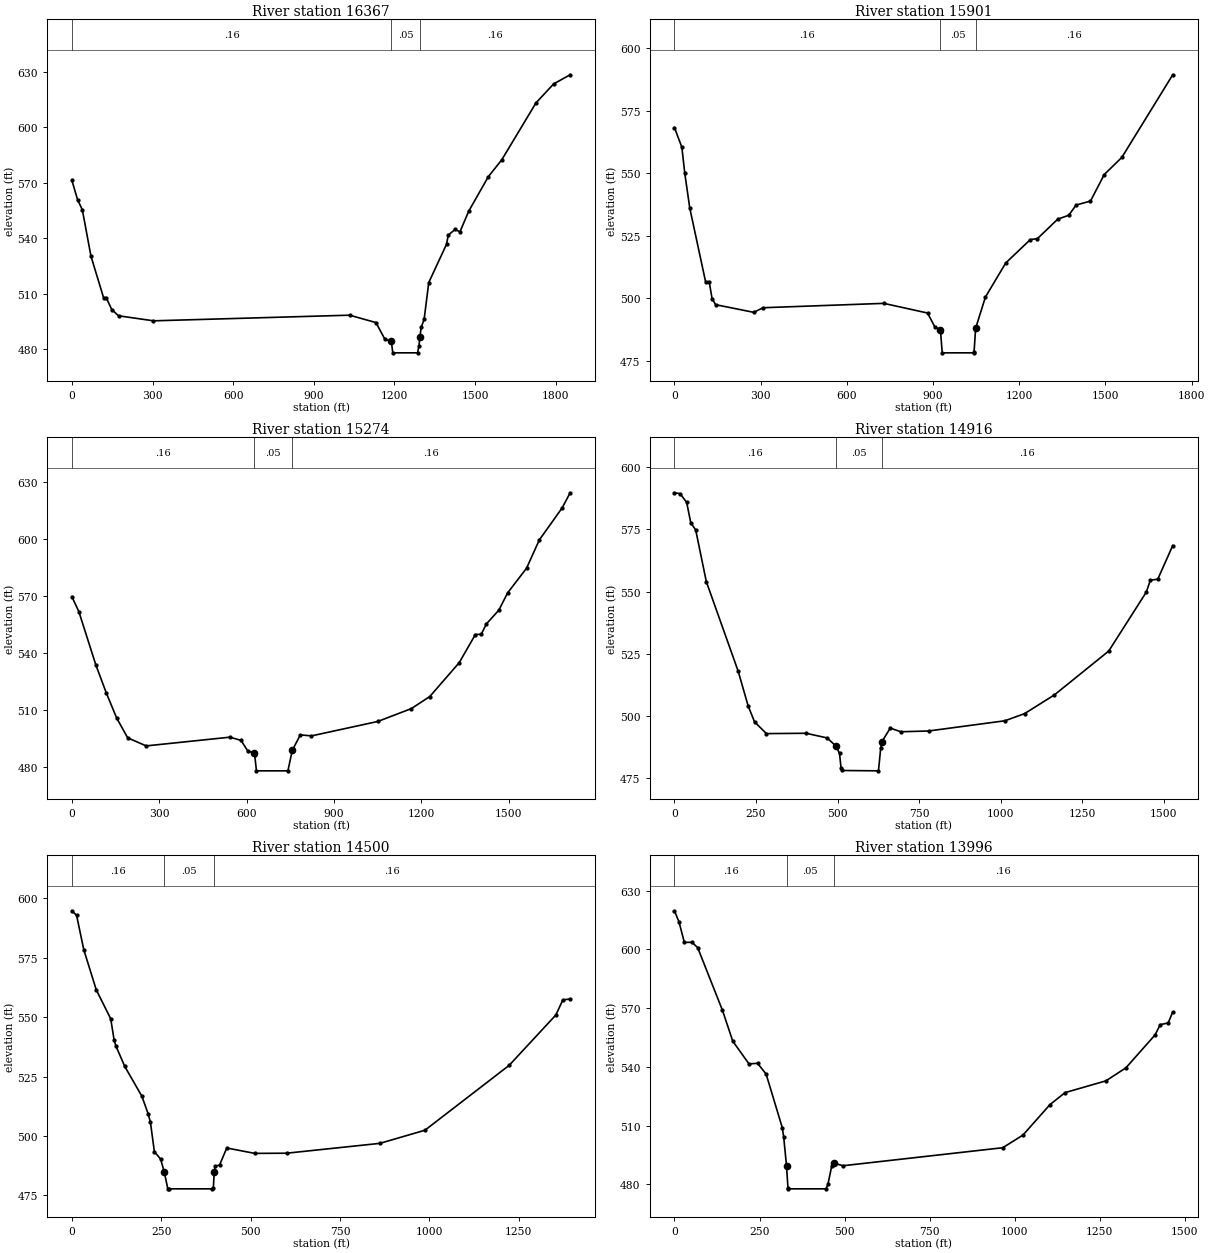
Type RM Length L Ch R = 1 ,16367   ,463.5,465.7,467.2
BEGIN DESCRIPTION:
Smith Fork River 33.0
END DESCRIPTION:
XS GIS Cut Line= 4
      2005843.04       646921.212006575.00181591 646911.66125938
 2007204.4429695647223.251695691       2007622.7        647189.9
#Sta/Elev= 30
       0  571.27      21   560.9    38.9  555.35      71  530.31   118.5  507.61
   128.5  507.62   148.5  501.46   173.5  498.14   303.6  495.41  1033.4  498.46
  1131.5  494.46  1165.1  485.33  1188.5   484.5    1194  478.12  1286.1  478.12
  1291.7  481.97  1294.5  486.43    1300  491.96  1310.7  496.22  1327.9   516.1
  1394.1  536.77  1400.5   541.7  1425.6  544.76    1444  543.48  1476.6  554.63
  1549.4  573.23  1599.5  582.37    1727  613.13  1792.6  623.37    1854   628.3
#Mann= 3 , 0 , 0
       0     .16       0  1188.5     .05       0  1294.5     .16       0
Bank Sta=1188.5,1294.5
XS Rating Curve= 0 ,0
Exp/Cntr=0.3,0.1

Type RM Length L Ch R = 1 ,15901   ,620.2,627.5,633.3
BEGIN DESCRIPTION:
Smith Fork River 32.0
END DESCRIPTION:
XS GIS Cut Line= 4
      2005873.26       647319.972006375.85289105 647313.02293872
2007019.13594718647658.339991824      2007467.47       647433.93
#Sta/Elev= 30
       0   568.3    25.8   560.4    35.8  550.05    53.3  536.05   108.3  506.58
   120.8  506.61   130.8  499.87   143.3   497.4   275.8  494.34   308.3  496.18
   728.3  497.93   880.8  494.06   906.4  488.46   923.4  487.46   926.2  486.39
   931.9  478.12  1041.5  478.12  1042.6  478.33  1048.2  487.98  1082.3  500.47
    1153  514.11  1238.3  523.44  1263.4  523.86  1333.6  531.61  1372.5  533.22
  1397.6  537.28  1447.9  538.89  1495.7  549.49    1557  556.37  1734.1  589.45
#Mann= 3 , 0 , 0
       0     .16       0   923.4     .05       0  1048.2     .16       0
Bank Sta=923.4,1048.2
XS Rating Curve= 0 ,0
Exp/Cntr=0.3,0.1

Type RM Length L Ch R = 1 ,15274   ,360.4,357.6,352.9
BEGIN DESCRIPTION:
Smith Fork River 31.0
END DESCRIPTION:
XS GIS Cut Line= 4
      2005853.08       647849.452006247.17204729647922.725031762
2006824.75998365648305.410198675      2007436.41       648392.37
#Sta/Elev= 30
       0  569.78    23.9  561.92    82.4  533.75     118  519.12   153.9  505.77
   191.7  495.36   255.3  491.12     543  495.72   580.9  494.03   604.8  488.28
     625  487.56   627.8  486.49     634  477.97     742  477.97     757  488.74
   784.7  496.93     823  496.39  1050.9  504.01  1166.2  510.79  1229.4  517.15
  1330.4  534.98  1385.9  549.81  1406.1  549.99  1423.8  555.43  1466.5  562.67
    1497  571.84  1561.8   584.8  1605.6   599.7  1683.9  616.56  1711.5  624.56
#Mann= 3 , 0 , 0
       0     .16       0     625     .05       0     757     .16       0
Bank Sta=625,757
XS Rating Curve= 0 ,0
Exp/Cntr=0.3,0.1

Type RM Length L Ch R = 1 ,14916   ,461.2,416.1,363.7
BEGIN DESCRIPTION:
Smith Fork River 30.0
END DESCRIPTION:
XS GIS Cut Line= 4
      2005739.19       648231.512006020.44865591 648210.72501541
2006569.48764287 648547.47062873      2007169.89       648588.84
#Sta/Elev= 30
       0  589.73    17.4  589.37    37.5  585.83      50  577.66    65.1  574.79
    97.6  554.02   195.4  517.94     226  503.97   245.5  497.59     282  492.86
   403.6  492.99   468.1  491.12   495.3  487.83   506.1   484.9   510.9  478.97
     515  478.02   625.6  477.88   632.3   486.9   636.1489.6084   661.7  495.08
   693.9   493.6     779  493.91  1013.4  498.02  1073.8  500.91  1165.2  508.44
  1331.7  526.07  1446.9  549.78  1459.4  554.58    1482  554.96  1527.9  568.49
#Mann= 3 , 0 , 0
       0     .16       0   495.3     .05       0   636.1     .16       0
Bank Sta=495.3,636.1
XS Rating Curve= 0 ,0
Exp/Cntr=0.3,0.1

Type RM Length L Ch R = 1 ,14500   ,538.2,504.2,472.6
BEGIN DESCRIPTION:
Smith Fork River 29.0
END DESCRIPTION:
XS GIS Cut Line= 3
      2005745.83       648727.48      2006074.79       648722.09
      2007139.47        648692.3
#Sta/Elev= 30
       0  594.81    13.2  592.86    33.2  578.46    68.2  561.53   108.6  549.36
   118.3   540.3   123.3  537.86   147.9   529.3   195.8  516.76   213.3  509.39
   219.8  505.76   230.8  493.41   248.3   490.3   258.6  484.77   268.3  477.87
   270.8  477.78   393.3  477.78   395.8  478.29   398.3  485.01   400.8  487.27
   413.3  487.83   433.3  494.97   511.8   492.7   600.9  492.78   861.7  496.92
   987.8  502.45  1223.6  529.77  1354.2  550.97  1373.7  557.31  1394.1  557.69
#Mann= 3 , 0 , 0
       0     .16       0   258.6     .05       0   398.3     .16       0
Bank Sta=258.6,398.3
XS Rating Curve= 0 ,0
Exp/Cntr=0.3,0.1

Type RM Length L Ch R = 1 ,13996   ,470.5,469.1,443.1
BEGIN DESCRIPTION:
Smith Fork River 28.0
END DESCRIPTION:
XS GIS Cut Line= 3
2005858.15319271649382.7248965742006515.13381326649054.103837789
      2007224.63       648880.97
#Sta/Elev= 30
       0  619.75    13.6  613.92      29   603.6    51.3  603.66    68.1  600.98
   140.8  569.06   171.5  553.16   219.1  541.56   244.2  541.88   269.4  536.41
   316.9  509.06   321.1  504.24   329.4  489.62   333.7  478.19     335  477.78
   445.5  477.78   451.1  480.03   462.2  489.31   467.7490.9478   495.8  489.58
   965.1  498.77  1024.5  505.22  1104.1   520.8  1148.4  526.91  1268.4  532.91
  1327.2  539.55  1412.9  556.36  1428.3  561.63  1451.5  562.47  1464.9  568.02
#Mann= 3 , 0 , 0
       0     .16       0   329.4     .05       0   467.7     .16       0
Bank Sta=329.4,467.7
XS Rating Curve= 0 ,0
Exp/Cntr=0.3,0.1