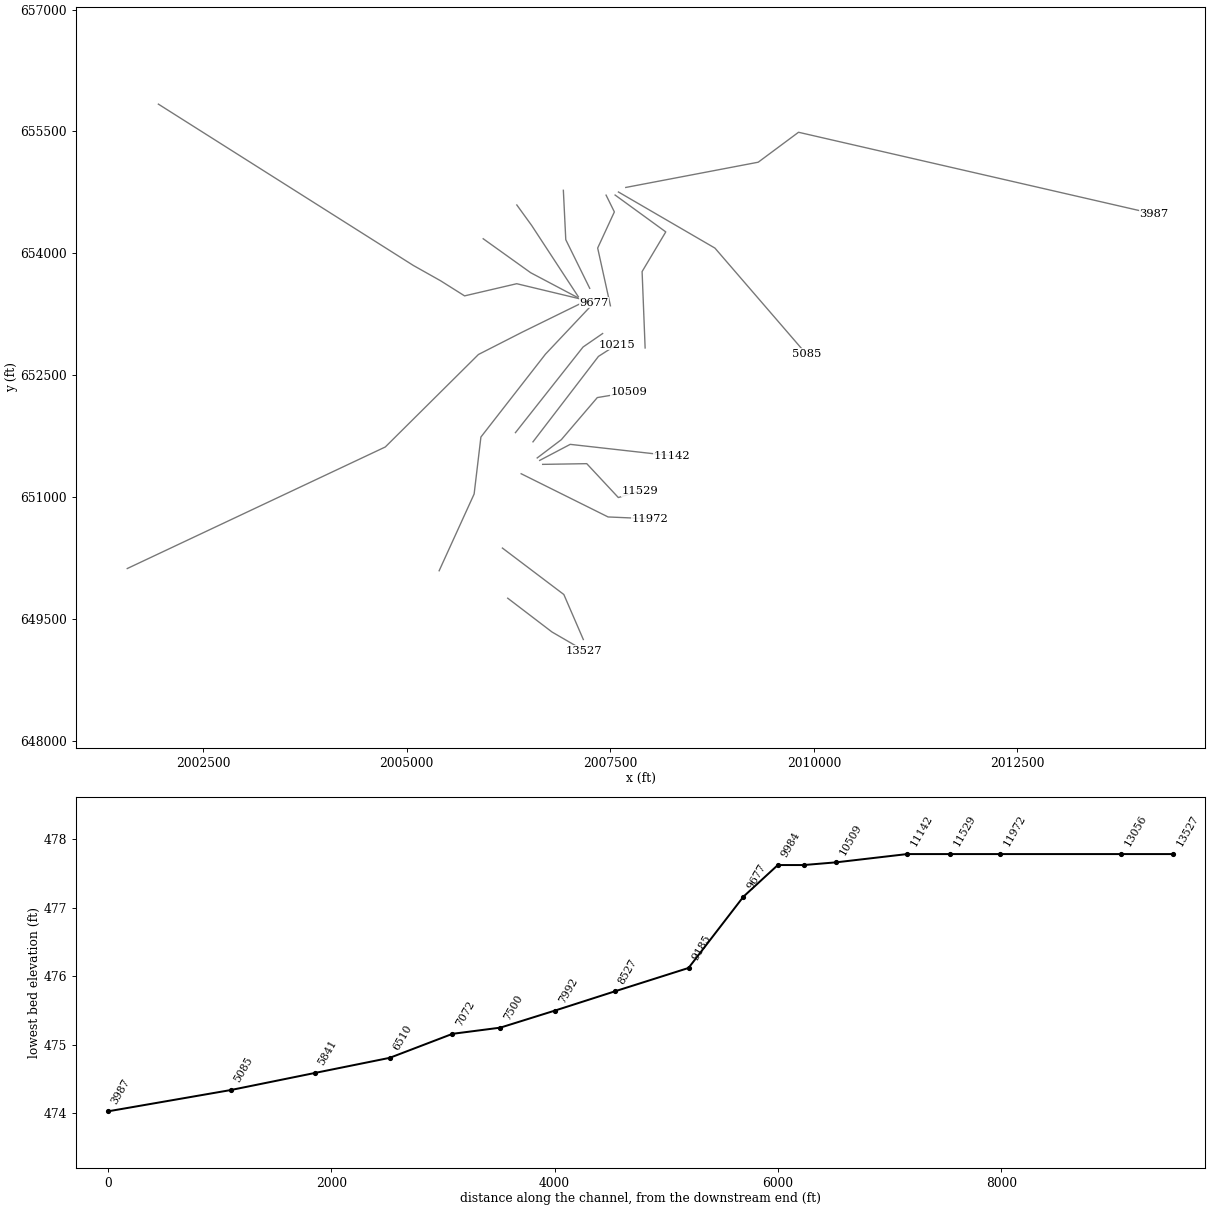
HEC-RAS study SmithFork2019.prj: Smith County FPMS Study 2019

--- SmithFork2019.g07 (geometry) --- (continued)

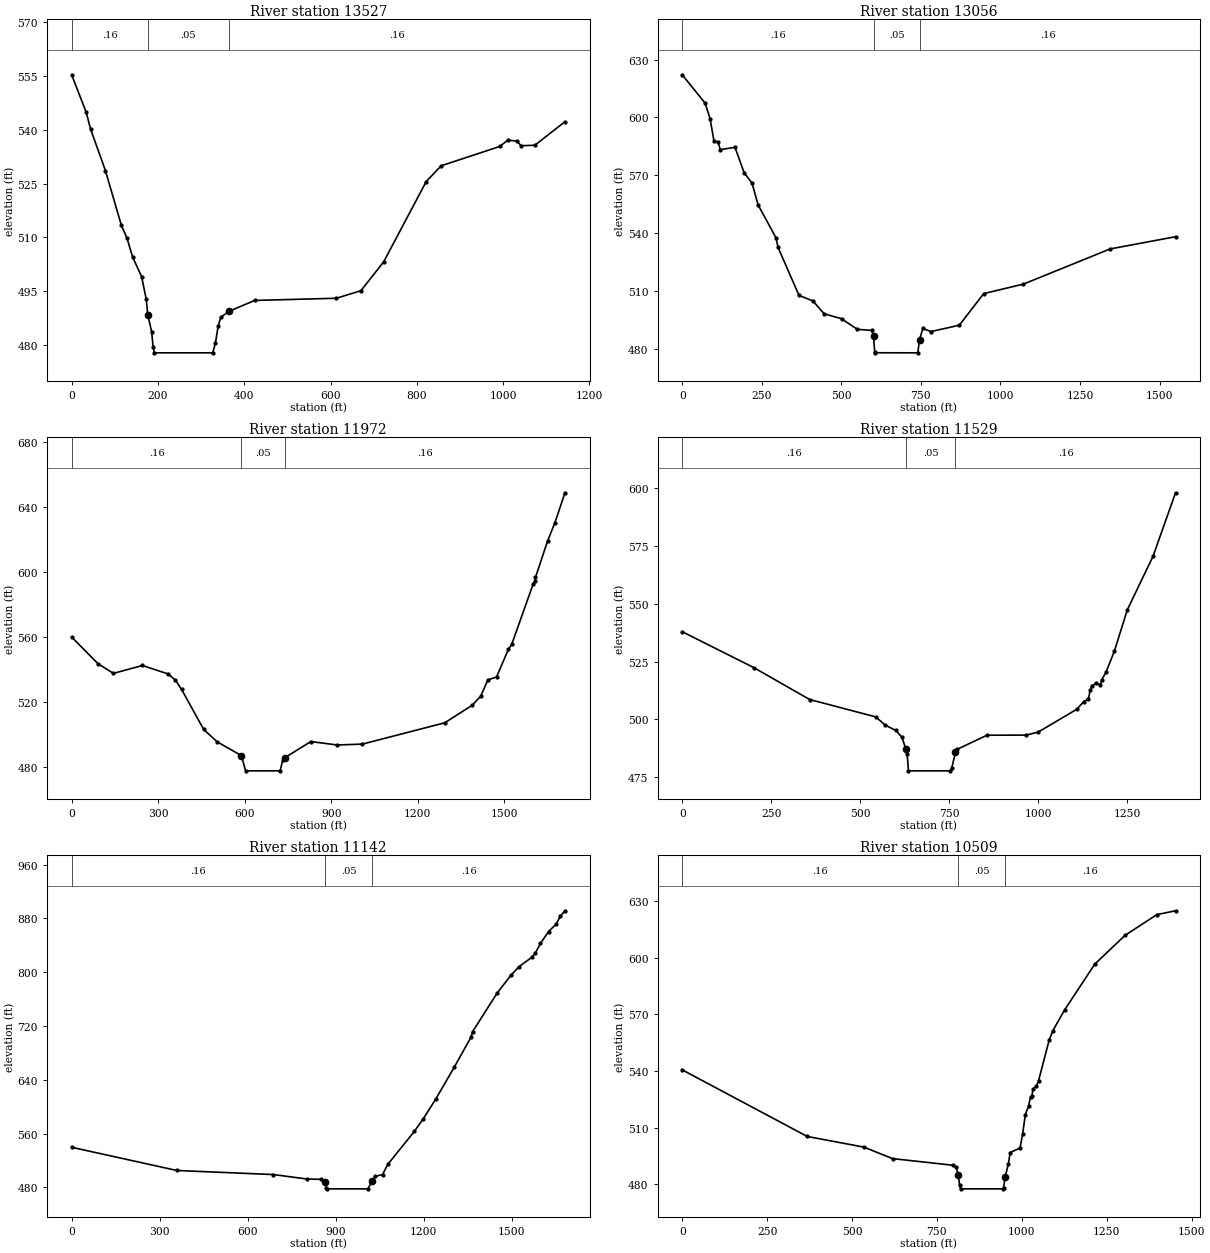
Type RM Length L Ch R = 1 ,13527   ,454.4,471.1,454.9
BEGIN DESCRIPTION:
Smith Fork River 27.0
END DESCRIPTION:
XS GIS Cut Line= 3
      2006241.82       649752.982006785.65615403649336.755971711
      2007182.05       649106.15
#Sta/Elev= 30
       0  555.35    33.8  544.88    43.8  540.23    78.3  528.62   115.3  513.33
   128.3  509.76   141.3  504.52   162.2  499.04   172.9  492.73   176.4  488.42
   185.4  483.69   188.9  479.32   191.7  477.78   327.1  477.78   333.4  480.63
   339.7  485.34   345.7  487.69   364.4489.3521   424.3   492.4   613.6  493.01
   670.4  495.11   723.1  503.14   821.8  525.56   856.4  529.96   992.5  535.36
  1010.7   537.1  1032.1  536.87  1041.6  535.57  1073.5  535.68  1143.4  542.26
#Mann= 3 , 0 , 0
       0     .16       0   176.4     .05       0   364.4     .16       0
Bank Sta=176.4,364.4
XS Rating Curve= 0 ,0
Exp/Cntr=0.3,0.1

Type RM Length L Ch R = 1 ,13056   ,1073.3,1083.9,1094.7
BEGIN DESCRIPTION:
Smith Fork River 26.0
END DESCRIPTION:
XS GIS Cut Line= 3
2006176.72276265650370.2653184532006930.91828796649798.367245524
      2007170.13       649244.31
#Sta/Elev= 30
       0  622.09      72  607.36    87.7  599.19    99.7   587.8   112.8  587.22
   119.4  583.24   165.8  584.46   194.3  571.37   219.4  565.85   238.3   554.6
   294.7  537.49     301  532.55   366.9   507.6   410.8  504.73   445.9  498.05
   500.5  495.48   550.1  489.99   595.8  489.41   601.1  486.49   604.7  478.47
   606.5  477.82   740.2  477.78   745.7  484.61   755.9  490.42   781.4  488.82
   870.6  492.11   947.4  508.53  1072.3  513.46  1344.6  531.71    1550  538.04
#Mann= 3 , 0 , 0
       0     .16       0   601.1     .05       0   745.7     .16       0
Bank Sta=601.1,745.7
XS Rating Curve= 0 ,0
Exp/Cntr=0.3,0.1

Type RM Length L Ch R = 1 ,11972   ,475.3,442.6,415.8
BEGIN DESCRIPTION:
Smith Fork River 24.0
END DESCRIPTION:
XS GIS Cut Line= 3
      2006406.99       651285.332007474.12359006 650753.30341591
      2007990.98       650730.71
#Sta/Elev= 30
       0  560.18    91.7  543.71   144.8  537.79   245.4  542.66   334.7  537.45
   359.9  533.55   380.9  527.97   457.7  503.27   504.8   495.6   588.2  487.19
   602.9  477.78   722.7  477.78   731.4  484.19   737.8  485.77   829.1  495.81
   920.5   493.7    1008  494.25  1293.5  507.39  1387.5  518.08  1417.6  523.63
  1442.6  533.82  1472.6  535.55    1514  552.65  1525.2  555.59  1600.2  593.14
  1605.4  594.41  1607.7  596.91  1649.8  619.45  1675.3  630.71  1709.8  649.02
#Mann= 3 , 0 , 0
       0     .16       0   588.2     .05       0   737.8     .16       0
Bank Sta=588.2,737.8
XS Rating Curve= 0 ,0
Exp/Cntr=0.3,0.1

Type RM Length L Ch R = 1 ,11529   ,317.3,387.2,434.2
BEGIN DESCRIPTION:
Smith Fork River 23.0
END DESCRIPTION:
XS GIS Cut Line= 4
      2006670.77       651400.652007212.27837547651409.363131671
2007599.99636906650992.117038672      2007863.65       651072.01
#Sta/Elev= 30
       0  537.88   200.8  522.41   358.3  508.59   543.9  501.09   570.9  497.51
   600.5  495.22   617.7  492.26   628.7  487.14   632.3     485     636  477.78
   753.5  477.78   757.2  478.81   768.1485.7243   771.9     487   856.4  493.17
   966.8  493.22  1000.3   494.5  1109.8  504.45  1128.5   507.7  1141.5  508.72
  1147.1  512.83    1152  514.59  1162.4  515.58  1175.2  514.91  1179.2  517.12
  1191.2   520.4  1214.7  529.48  1251.2  547.37  1323.5  570.52  1386.6  597.91
#Mann= 3 , 0 , 0
       0     .16       0   628.7     .05       0   768.1     .16       0
Bank Sta=628.7,768.1
XS Rating Curve= 0 ,0
Exp/Cntr=0.3,0.1

Type RM Length L Ch R = 1 ,11142   ,544,633,710.2
BEGIN DESCRIPTION:
Smith Fork River 22.0
END DESCRIPTION:
XS GIS Cut Line= 3
       2006634.3       651449.342007009.23907346651647.033374722
2008259.61487023651506.256824553
#Sta/Elev= 30
       0  539.62   358.7  505.08   687.9  499.04   801.1  492.47   848.9  491.93
     864  488.14   866.5  486.45     869   478.8   871.5  477.78  1009.9  477.78
  1025.6489.9312    1035  496.45  1060.2  498.92  1077.8  514.03  1168.4  563.21
  1198.6  581.65  1241.3  611.19  1304.8  658.85  1362.1  703.68  1367.1  711.57
  1450.1  768.51  1497.9  795.55  1525.6   808.3  1568.4  822.04    1581  828.46
  1598.6   842.9  1626.2  860.58  1652.2  871.55  1666.5  883.46  1682.1  891.45
#Mann= 3 , 0 , 0
       0     .16       0     864     .05       0  1025.6     .16       0
Bank Sta=864,1025.6
XS Rating Curve= 0 ,0
Exp/Cntr=0.3,0.1

Type RM Length L Ch R = 1 ,10509   ,285.3,293.5,293.2
BEGIN DESCRIPTION:
Smith Fork River 21.0
END DESCRIPTION:
XS GIS Cut Line= 4
      2006603.85       651479.762006900.30290943651704.905711862
2007341.68339865652222.917653776      2007735.88       652289.23
#Sta/Elev= 30
       0  540.65   368.1  505.38   534.9  499.75   619.2  493.67   796.6  490.16
   806.4  489.24     813  484.83   816.8  479.51   819.6  477.66   944.4  477.66
   946.3  478.33   950.9  483.98   960.1  490.68   965.8  496.88   994.8   499.3
  1002.5  506.85  1010.1  516.84  1019.9  521.53  1025.6  526.25  1029.5  526.83
  1033.1  530.48  1042.9  531.97  1049.2  534.93  1080.6  556.47  1090.7  561.18
  1126.2  572.47  1214.9  596.64  1304.4  611.93  1397.7  622.82  1452.5  624.85
#Mann= 3 , 0 , 0
       0     .16       0     813     .05       0   950.9     .16       0
Bank Sta=813,950.9
XS Rating Curve= 0 ,0
Exp/Cntr=0.5,0.3

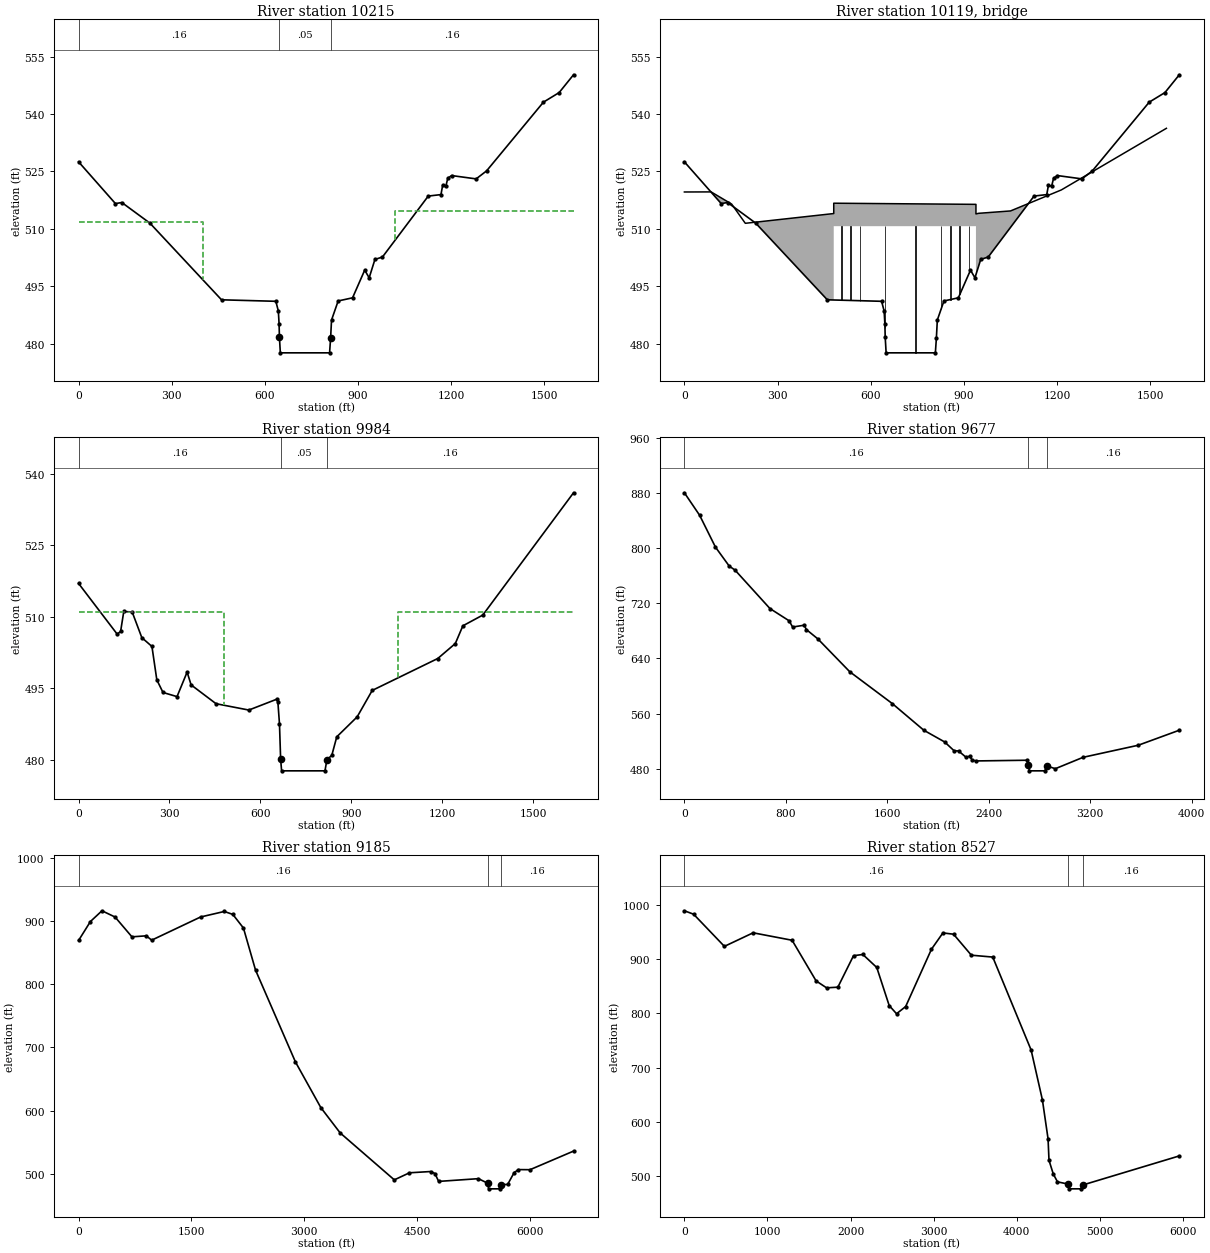
Type RM Length L Ch R = 1 ,10215   ,232.8,230.9,230.5
XS GIS Cut Line= 3
2006552.05508104651678.1857254132007356.00270442652730.052634957
2007582.99105654652876.204377013
#Sta/Elev= 30
       0   527.5   118.6   516.6   139.2  516.88   229.7  511.49   460.3  491.47
   635.2  491.08   643.3  488.54   645.6  485.27   646.8  481.65   649.7  477.62
   808.3  477.62   811.6481.5073   814.6  486.19   835.9  491.17   882.3  491.99
   921.4  499.22   935.8  497.22   954.3  502.01   978.6  502.65  1126.1  518.56
    1167  518.95  1172.5  521.41  1182.7  521.14    1189  523.22  1201.3  523.92
  1280.3  523.05  1313.9  525.14    1497  543.09  1547.6  545.59  1593.9  550.24
#Mann= 3 , 0 , 0
       0     .16       0   646.8     .05       0   811.6     .16       0
#XS Ineff= 2 , 0
             401  511.69    1019          514.68
Permanent Ineff=
       F       F
Bank Sta=646.8,811.6
XS Rating Curve= 0 ,0
Exp/Cntr(USF)=0,0
Exp/Cntr=0.5,0.3

Type RM Length L Ch R = 3 ,10119   ,,,
Bridge Culvert--1,0,-1,-1, 0
Deck Dist Width WeirC Skew NumUp NumDn MinLoCord MaxHiCord MaxSubmerge Is_Ogee
80,39,2.6,0, 12, 12, , , 0.98, 0, 0,0,,
       0   86.09  152.22   196.2     481     481     939     939   947.6 1050.33
 1213.81 1552.34
  519.63  519.65  516.47  511.45     514   516.7   516.4   513.9  514.06  514.68
  520.16  536.26
                                           510.7   510.7
                
       0   86.09  152.22   196.2  481.69     539     539     997     997 1050.33
 1213.81 1552.34
  519.63  519.65  516.47  511.45   513.8   513.9   516.6   516.6   513.9  514.68
  520.16  536.26
                                                   510.6   510.6
                
Pier Skew, UpSta & Num, DnSta & Num=  ,506, 2 ,564, 2 , 0 , 0 , 0 ,,
       1       1
       0   510.7
       1       1
       0   510.7
Pier Skew, UpSta & Num, DnSta & Num=  ,535, 2 ,593, 2 , 0 , 0 , 0 ,,
       1       1
       0   510.7
       1       1
       0   510.7
Pier Skew, UpSta & Num, DnSta & Num=  ,565, 2 ,623, 2 , 0 , 0 , 0 ,,
       2       2
       0   510.7
       2       2
       0   510.7
Pier Skew, UpSta & Num, DnSta & Num=  ,646, 2 ,704, 2 , 0 , 0 , 0 ,,
       3       2
       0   510.7
       3       2
       0   510.7
Pier Skew, UpSta & Num, DnSta & Num=  ,743, 2 ,801, 2 , 0 , 0 , 0 ,,
       3       2
       0   510.7
       3       2
       0   510.7
Pier Skew, UpSta & Num, DnSta & Num=  ,827, 2 ,885, 2 , 0 , 0 , 0 ,,
       2       2
       0   510.7
       2       2
       0   510.7
Pier Skew, UpSta & Num, DnSta & Num=  ,857, 2 ,915, 2 , 0 , 0 , 0 ,,
       2       2
       0   510.7
       2       2
       0   510.7
Pier Skew, UpSta & Num, DnSta & Num=  ,887, 2 ,945, 2 , 0 , 0 , 0 ,,
       2       2
       0   510.7
       2       2
       0   510.7
Pier Skew, UpSta & Num, DnSta & Num=  ,917, 2 ,975, 2 , 0 , 0 , 0 ,,
       2       2
       0   510.7
       2       2
       0   510.7
BR Coef=-1 , 1 , 0 ,, 0 ,,,0.8,0,1.85,0,
WSPro=,,,, 1 ,,,, 0 ,,,, 0 ,,,,-1 ,-1 ,-1 , 0 , 0 , 0 , 0 , 0
BC Design=,, 0 ,, 0 ,,,,,,
BC Use User HTab Curves=0
BC User HTab FreeFlow(D)= 0

Type RM Length L Ch R = 1 ,9984    ,306,307.3,314.3
XS GIS Cut Line= 3
2006336.82059302651791.4230447522007166.74693455652845.384380654
2007407.13921972653011.423175955
#Sta/Elev= 30
       0  516.95   127.3  506.32   138.7  506.89   149.1  511.07   176.9  510.96
   208.7  505.58   242.1  503.73   258.2  496.72   278.6  494.07   324.9   493.2
   358.2  498.35   371.4  495.66   453.7  491.71   561.9  490.38   654.2  492.66
   657.8  492.09   663.1  487.46   666.9  480.06   670.1  477.62   813.3  477.62
   819.6  479.96   835.8  480.87   852.2  484.76   919.5  488.95   969.2   494.5
  1185.6   501.2  1243.5  504.34  1268.4  508.06  1334.2  510.32  1633.7  535.99
#Mann= 3 , 0 , 0
       0     .16       0   666.9     .05       0   819.6     .16       0
#XS Ineff= 2 , 0
           481.5     511  1054.5             511
Permanent Ineff=
       F       F
Bank Sta=666.9,819.6
XS Rating Curve= 0 ,0
Exp/Cntr(USF)=0,0
Exp/Cntr=0.5,0.3

Type RM Length L Ch R = 1 ,9677    ,535.4,492,454.3
BEGIN DESCRIPTION:
Smith Fork River 19.0
END DESCRIPTION:
XS GIS Cut Line= 5
2005400.14642294650091.0028410542005829.54480349 651035.88469842
2005912.72729782651737.0215324592006705.43105243652757.694246041
       2007298.8       653388.52
#Sta/Elev= 30
       0  880.09   120.1  847.53   245.1  801.31   353.9  773.78     399  768.11
   674.6  712.34   825.9  694.57   853.3  685.54   944.6  688.19   961.6  681.92
  1052.5  668.33  1304.2  620.71  1639.1  574.67    1888  535.97  2051.8  519.05
  2126.8  506.22  2161.8  505.99  2219.8  496.94  2248.3  498.29  2270.5  492.63
    2299  491.51    2704  492.53  2711.2  485.38    2720  477.16  2842.5  477.16
  2857.3  484.26    2925  480.27  3143.7  496.76  3578.8  514.26  3902.3  536.02
#Mann= 3 ,-1 , 0
       0     .16       0  2711.2     .05       0  2857.3     .16       0
Bank Sta=2711.2,2857.3
XS Rating Curve= 0 ,0
Exp/Cntr=0.3,0.1

Type RM Length L Ch R = 1 ,9185    ,682.7,658.1,638.3
BEGIN DESCRIPTION:
Smith Fork River 18.0
END DESCRIPTION:
XS GIS Cut Line= 5
2001570.85943719650118.1981343712004738.71693551651614.688161446
 2005882.4306268652753.4162906272006419.08254217653028.094255126
      2007187.86       653406.27
#Sta/Elev= 30
       0     869   157.3  898.94   310.5  915.91   484.8     906   708.6  874.71
   899.8  876.29   971.1  869.42    1621  906.08  1936.2  914.82  2049.6  910.16
  2190.6  888.61  2351.3  822.11  2881.8   676.8  3219.1   604.6  3476.3  564.53
  4195.5  490.31    4397   501.5  4677.3  503.49  4735.3  500.37  4784.6  487.88
  5313.1  492.22  5439.5  484.78  5447.9  476.12  5593.9  476.12  5610.8  482.79
  5701.6  483.06  5787.8  501.81  5845.7  506.57  5998.9  506.39  6577.1   535.8
#Mann= 3 ,-1 , 0
       0     .16       0  5439.5     .05       0  5610.8     .16       0
Bank Sta=5439.5,5610.8
XS Rating Curve= 0 ,0
Exp/Cntr=0.3,0.1

Type RM Length L Ch R = 1 ,8527    ,619.7,535.6,453.2
BEGIN DESCRIPTION:
Smith Fork River 17.0
END DESCRIPTION:
XS GIS Cut Line= 6
2001952.93682207655835.8718895862005082.57310762653850.061487213
2005417.20553577 653661.39941869 2005712.2178705653475.118377311
 2006352.5565741653624.896592266       2007187.9       653424.03
#Sta/Elev= 30
       0  989.78   110.9  983.45   481.5  923.99   827.4  949.06  1296.3  935.29
  1585.4  860.09  1711.2  847.35    1847  848.54  2035.4  906.73  2147.7  909.01
  2315.4  884.94  2464.7  814.62  2553.3  799.43  2663.1  812.77  2973.7  918.78
  3111.4  948.86  3239.3  946.47  3453.6  907.67  3711.1   904.2  4172.7  732.45
  4308.7  640.18  4376.7  568.28  4388.1  528.53  4439.5  503.29  4490.2  488.68
  4621.2  484.52  4626.5  475.79  4772.6  475.78  4793.2  482.82  5956.3  536.64
#Mann= 3 ,-1 , 0
       0     .16       0  4621.2     .05       0  4793.2     .16       0
Bank Sta=4621.2,4793.2
XS Rating Curve= 0 ,0
Exp/Cntr=0.3,0.1

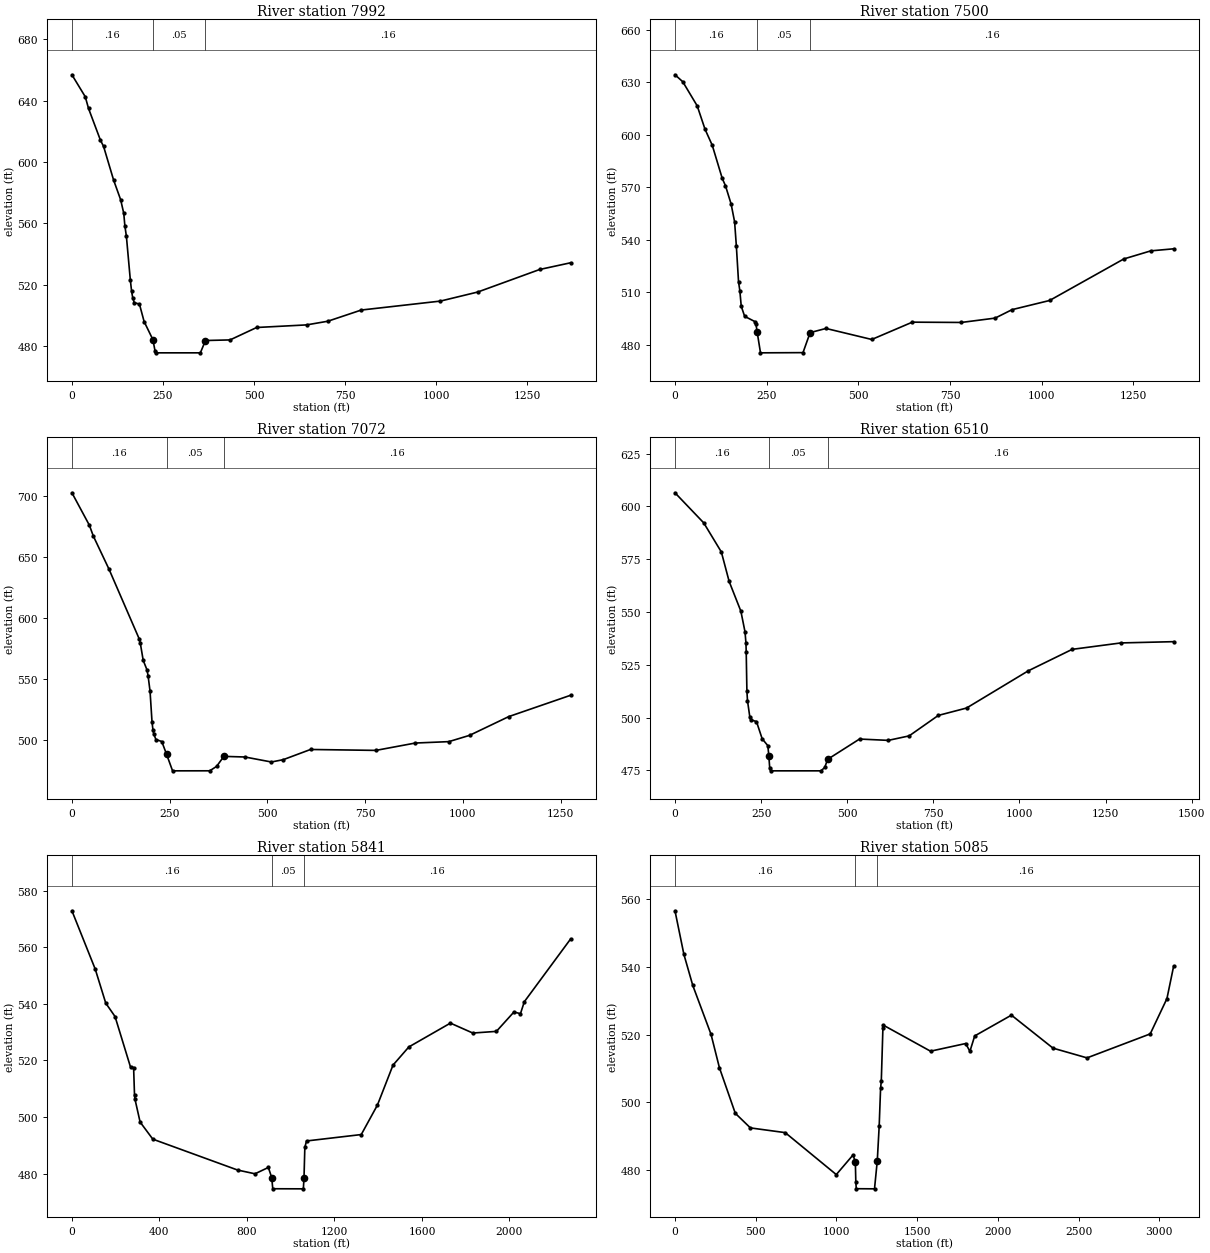
Type RM Length L Ch R = 1 ,7992    ,522.3,491.6,466
BEGIN DESCRIPTION:
Smith Fork River 16.0
END DESCRIPTION:
XS GIS Cut Line= 3
2005940.97744874654178.3842551262006524.00125746653760.080651441
      2007099.12       653455.11
#Sta/Elev= 30
       0  656.85    36.6  642.53    45.6  634.89    78.1  614.29    86.9  610.13
   114.6  588.03   133.8  575.32   142.3  566.46   145.3  558.39   149.5  551.51
   160.2  523.27   163.8  515.58   166.9  511.42     171  508.25   185.3  507.28
   198.1  495.92   222.3  484.06   228.3  476.46   231.5   475.5   352.5   475.5
   366.5483.5367     434  483.93   506.9  492.03   643.9  493.72   702.3  496.12
     794  503.41  1011.4  509.26  1113.8  515.17  1283.6  529.86  1368.5  534.24
#Mann= 3 ,-1 , 0
       0     .16       0   222.3     .05       0   366.5     .16       0
Bank Sta=222.3,366.5
XS Rating Curve= 0 ,0
Exp/Cntr=0.3,0.1

Type RM Length L Ch R = 1 ,7500    ,482.1,427.8,400
BEGIN DESCRIPTION:
Smith Fork River 15.0
END DESCRIPTION:
XS GIS Cut Line= 3
      2006353.57       654594.36      2006535.64       654342.47
      2007108.98        653463.9
#Sta/Elev= 30
       0  634.41    21.1  630.47    60.6  616.62    81.9  603.26   101.7  594.03
   128.9  575.08   137.6  570.97     153   560.5   162.6  550.25   167.3  536.58
   173.3  515.93   176.9   510.8   180.7  501.92     190  496.14   217.8  493.16
   220.8  491.76   223.9  487.45   233.2  475.25   349.1  475.37   368.5 486.825
   411.8  489.21   536.6   482.9   647.2  492.81   780.8  492.64     873  495.13
   919.3  499.98  1021.5  505.21  1223.8  528.98  1297.5  533.62  1359.9   534.8
#Mann= 3 ,-1 , 0
       0     .16       0   223.9     .05       0   368.5     .16       0
Bank Sta=223.9,368.5
XS Rating Curve= 0 ,0
Exp/Cntr=0.3,0.1

Type RM Length L Ch R = 1 ,7072    ,604.1,562.3,531.6
BEGIN DESCRIPTION:
Smith Fork River 14.0
END DESCRIPTION:
XS GIS Cut Line= 3
      2006924.99       654775.032006954.74766286654166.723845057
 2007248.7448884653568.273826888
#Sta/Elev= 30
       0   702.4    44.7  675.86    54.7  667.07    94.8  640.02   172.4  582.82
   174.9  579.62   182.4  565.43   192.1  557.65   194.9  552.77   199.9   540.2
   204.9  515.27   207.4  508.36   209.9  504.87   214.9  500.77   229.9  499.12
   242.2  488.65   257.5  475.16   352.6  475.19   370.1  478.78   388.7486.9772
   442.7  486.47   510.3  482.39   540.5  484.27   610.5  492.62   777.6  491.87
   878.5  497.88   964.3  499.03  1017.2  504.15  1117.5  519.48  1275.8  536.92
#Mann= 3 ,-1 , 0
       0     .16       0   242.2     .05       0   388.7     .16       0
Bank Sta=242.2,388.7
XS Rating Curve= 0 ,0
Exp/Cntr=0.3,0.1

Type RM Length L Ch R = 1 ,6510    ,671,668.6,648.4
BEGIN DESCRIPTION:
Smith Fork River 13.0
END DESCRIPTION:
XS GIS Cut Line= 4
      2007449.67       654715.282007551.18531664654508.818929405
2007346.26033092654064.054514085      2007502.92       653353.08
#Sta/Elev= 30
       0  606.42    83.5  592.17   134.6  578.41   157.3  564.43   191.3  550.38
   203.3  540.62     206  535.43   206.8  531.17   208.8  512.65   210.5  508.04
   217.2  500.39     220  498.97   236.6  498.14   253.1     490   269.6  486.71
   272.4  482.06   275.1  475.99   277.9  474.81   423.8  474.81   434.8  476.41
   443.1  480.25   535.8  489.86   619.2  489.23   679.8  491.35   764.5  501.04
   846.4  504.53  1025.6  522.14  1153.1  532.31  1294.4  535.35  1447.8  535.95
#Mann= 3 ,-1 , 0
       0     .16       0   272.4     .05       0   443.1     .16       0
Bank Sta=272.4,443.1
XS Rating Curve= 0 ,0
Exp/Cntr=0.3,0.1

Type RM Length L Ch R = 1 ,5841    ,549.5,756.5,820
BEGIN DESCRIPTION:
Smith Fork River 12.0
END DESCRIPTION:
XS GIS Cut Line= 4
       2007560.3       654716.522008182.33714437654262.913572185
2007891.76856689653774.510533709      2007928.88       652833.88
#Sta/Elev= 30
       0  572.93   106.8  552.25   154.7  540.26   197.1  535.53   268.3  517.54
     282   517.5   286.2  507.62     288  506.38   311.7  498.21   369.8  492.16
   757.2  481.24   836.8  479.91   897.9  482.15   913.2   478.6   918.1  474.62
  1057.9  474.59  1060.8  478.35  1064.7  489.27  1072.4  491.52  1322.6  493.79
  1396.5  504.22  1467.7  518.35    1540  524.77  1730.1   533.2  1832.4  529.69
  1940.3  530.28  2020.3  537.12  2050.3  536.55  2067.9  540.76  2279.5  562.96
#Mann= 3 ,-1 , 0
       0     .16       0   913.2     .05       0  1060.8     .16       0
Bank Sta=913.2,1060.8
XS Rating Curve= 0 ,0
Exp/Cntr=0.3,0.1

Type RM Length L Ch R = 1 ,5085    ,1014.4,1097.9,1136.3
BEGIN DESCRIPTION:
Smith Fork River 11.0
END DESCRIPTION:
XS GIS Cut Line= 3
      2007601.23       654754.122008785.77196682654063.523391457
      2009906.34       652760.93
#Sta/Elev= 30
       0  556.66    55.4  543.72   110.4  534.54   223.2   520.1   275.4  510.18
   373.7   496.7   467.3  492.38     683  490.98   999.3  478.56  1102.9  484.36
  1117.4  482.31  1120.3  476.32  1123.2  474.38  1236.1  474.34  1253.3  482.66
    1265  492.87  1273.7  504.09  1278.1  506.22  1288.1  521.86    1291  522.79
  1583.1  515.09  1800.7  517.36  1827.1  515.05  1856.8  519.61  2084.3  525.76
  2341.9  515.99  2552.6  513.11  2944.1  520.21  3047.6  530.65  3089.4  540.31
#Mann= 3 ,-1 , 0
       0     .16       0  1117.4     .05       0  1253.3     .16       0
Bank Sta=1117.4,1253.3
XS Rating Curve= 0 ,0
Exp/Cntr=0.3,0.1

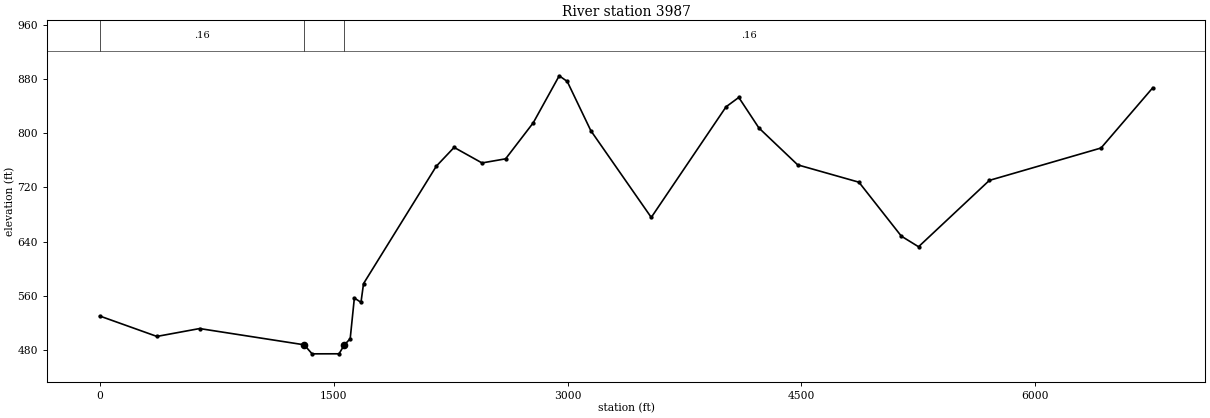
Type RM Length L Ch R = 1 ,3987    ,928.6,1035.1,1052.9
BEGIN DESCRIPTION:
Smith Fork River 8.0
END DESCRIPTION:
XS GIS Cut Line= 4
      2007691.13       654810.022009317.25518179655120.832143311
2009812.28194944 655489.520657162014177.42340144654483.630770206
#Sta/Elev= 30
       0  530.02     367  499.78   641.1  511.41  1311.3   487.4  1362.2  474.03
  1534.9  474.09  1568.3  486.99  1606.5  496.43  1633.2  556.55  1675.7  550.22
  1692.1  577.89  2158.6  751.45  2272.8  779.26  2451.7  756.28    2603  762.37
    2780  815.58  2946.8  885.16  2998.1  876.79  3149.5  803.95  3536.9  675.74
  4016.5   839.3    4098  853.15    4227  808.01  4475.8  753.45  4868.4  727.81
  5140.3  648.04  5250.6  632.37  5704.7  730.49  6420.7  778.38  6752.3  867.43
#Mann= 3 , 0 , 0
       0     .16       0  1311.3     .05       0  1568.3     .16       0
Bank Sta=1311.3,1568.3
XS Rating Curve= 0 ,0
Exp/Cntr=0.3,0.1