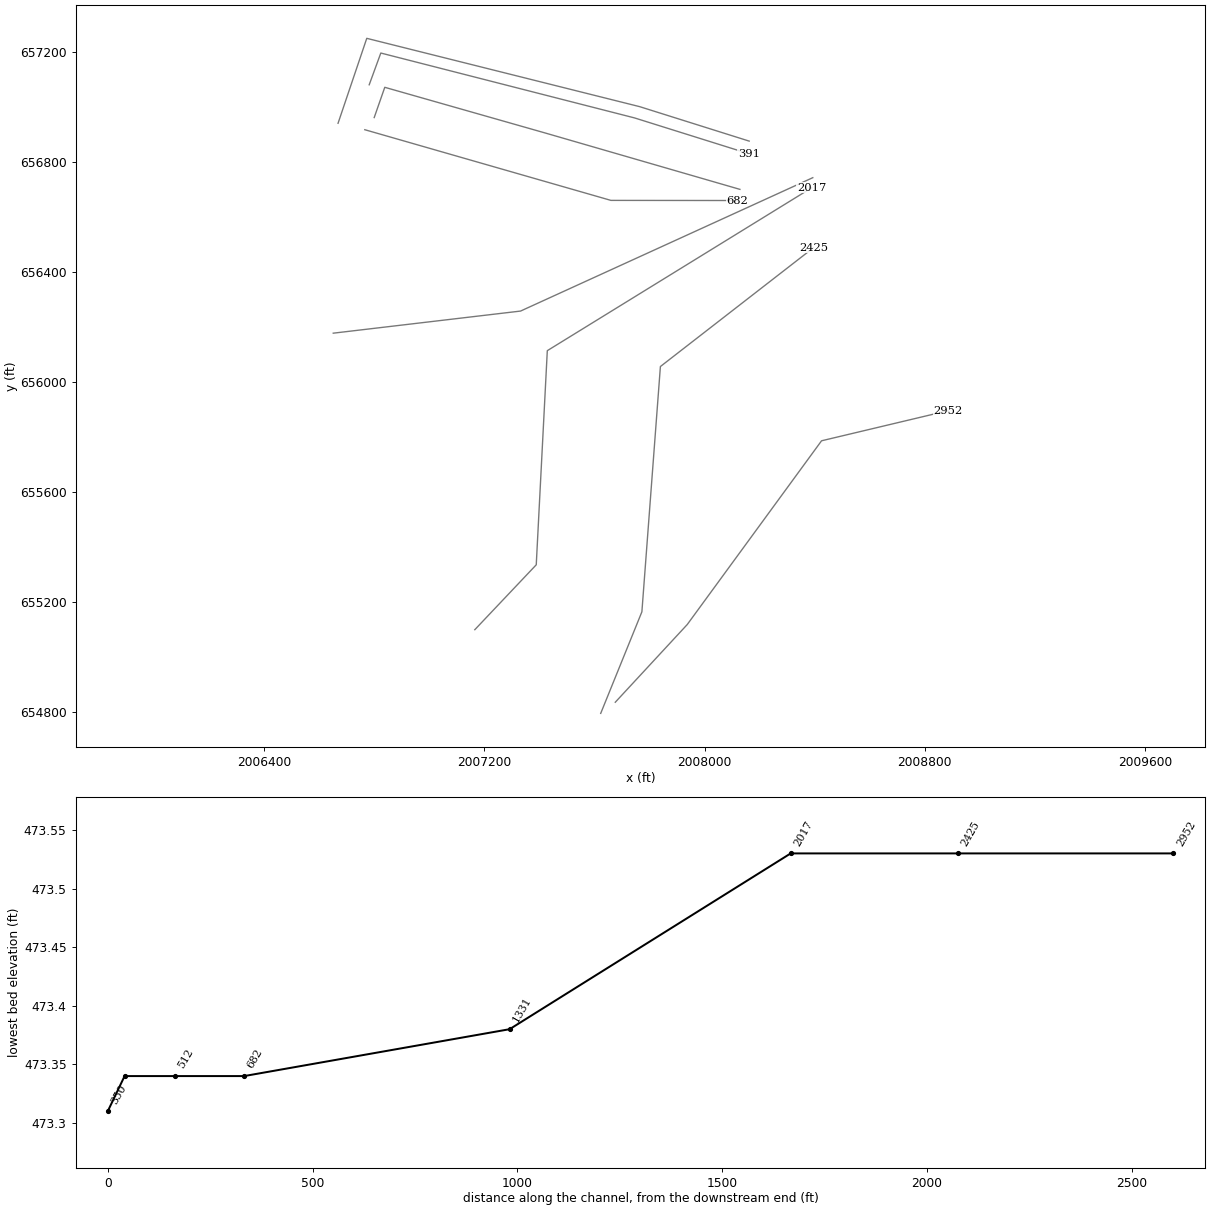
HEC-RAS study SmithFork2019.prj: Smith County FPMS Study 2019

--- SmithFork2019.g07 (geometry) --- (continued)

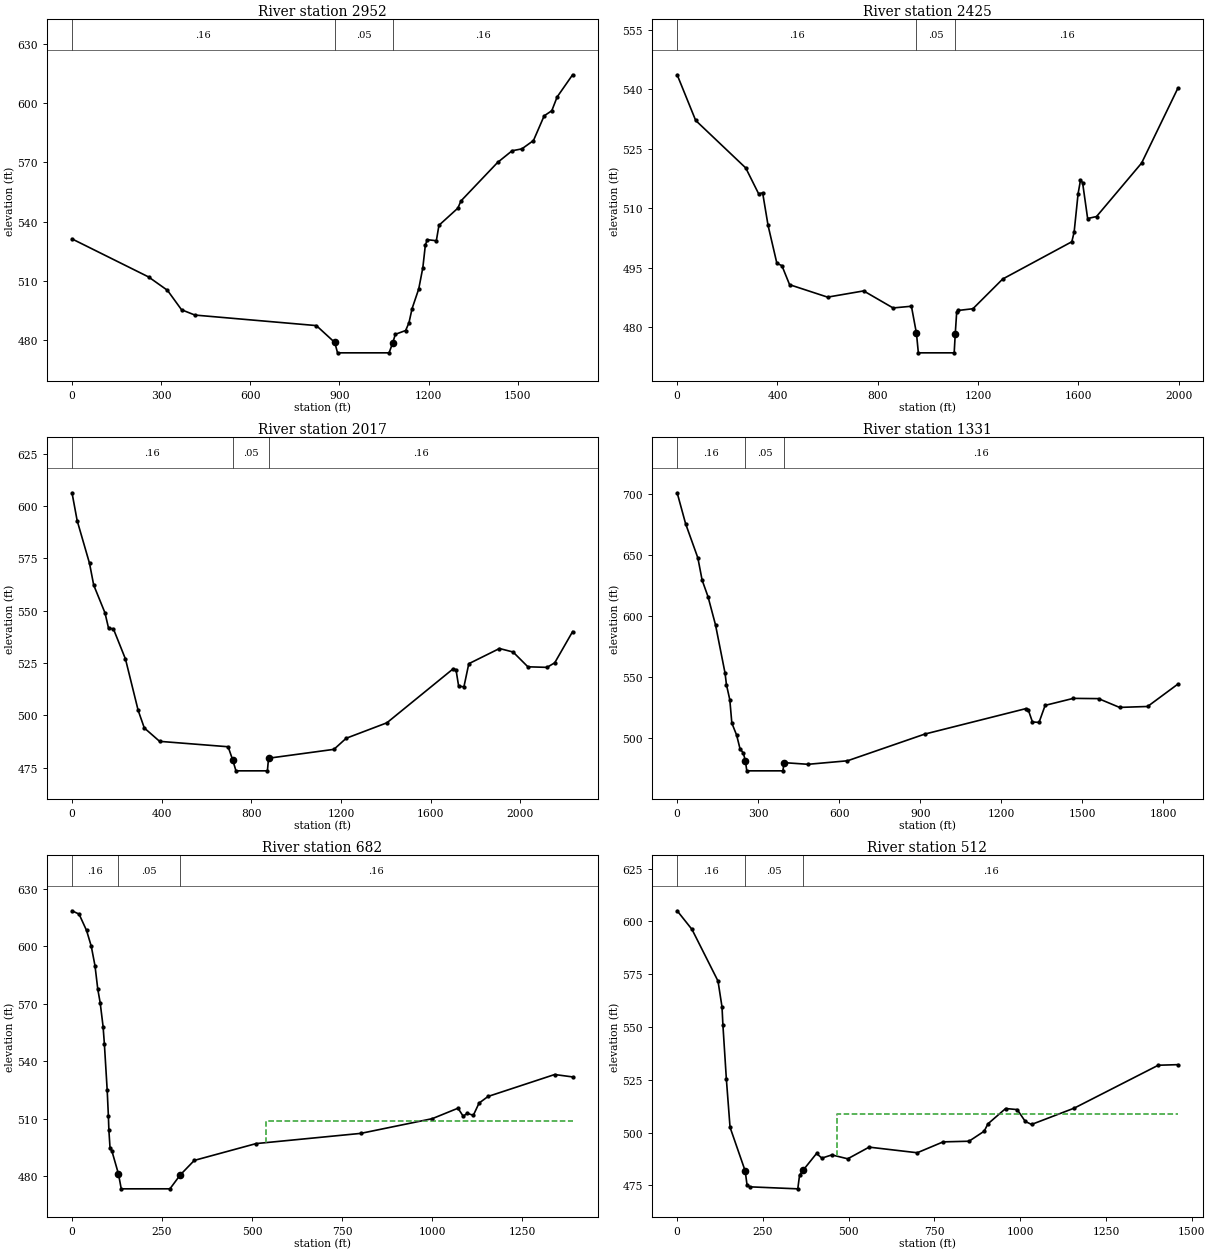
Type RM Length L Ch R = 1 ,2952    ,479.3,527.2,573.3
BEGIN DESCRIPTION:
Smith Fork River 7.0
END DESCRIPTION:
XS GIS Cut Line= 4
      2007675.55       654834.922007937.09921313655117.341552079
2008425.24178821 655785.14714649      2008884.67       655894.45
#Sta/Elev= 30
       0   531.2   257.6  511.95   321.2  505.17   368.6  495.33   413.5  492.65
   822.2  487.32   884.1  478.78   893.5  473.53  1066.9  473.53  1078.8  478.45
    1088  482.91  1122.6  484.83  1133.9   488.8  1144.3  495.93  1166.7   505.9
  1180.5  516.67  1188.9     528  1195.3  530.81  1225.9  530.27  1234.7  538.08
  1298.3  546.77  1308.6  550.38  1431.9  569.88  1480.7   575.8  1513.7  576.77
  1552.7  580.98  1588.7  593.48  1614.4  596.09  1632.4  603.05  1684.4  614.27
#Mann= 3 ,-1 , 0
       0     .16       0   884.1     .05       0  1078.8     .16       0
Bank Sta=884.1,1078.8
XS Rating Curve= 0 ,0
Exp/Cntr=0.3,0.1

Type RM Length L Ch R = 1 ,2425    ,405.5,407.5,410.5
BEGIN DESCRIPTION:
Smith Fork River 5.0
END DESCRIPTION:
XS GIS Cut Line= 4
      2007622.61       654794.452007772.26456717655163.575660092
 2007839.5466043656055.035898344       2008395.4       656486.48
#Sta/Elev= 30
       0  543.71    73.8  532.19   273.5  520.19   324.7   513.7   340.9  513.89
   362.5  505.68   397.6  496.13   417.7  495.53   448.3  490.73   599.8  487.59
   743.6  489.16   860.9  484.86   934.1  485.29   954.2  478.43   961.7  473.53
  1104.6  473.53  1108.8  478.27  1114.6  483.84  1119.6  484.22  1179.3  484.66
    1298  492.16  1573.7  501.57  1582.9  504.04  1598.7  513.73  1608.2  517.08
  1616.5   516.5  1636.7  507.43  1672.1  507.93  1851.9  521.43    1996  540.26
#Mann= 3 ,-1 , 0
       0     .16       0   954.2     .05       0  1108.8     .16       0
Bank Sta=954.2,1108.8
XS Rating Curve= 0 ,0
Exp/Cntr=0.3,0.1

Type RM Length L Ch R = 1 ,2017    ,803.9,686.4,556.8
BEGIN DESCRIPTION:
Smith Fork River 4.0
END DESCRIPTION:
XS GIS Cut Line= 4
2007165.08660854655098.649283444 2007388.3204528 655334.44084188
2007428.50285775656112.686076954      2008389.17       656704.63
#Sta/Elev= 30
       0  606.39      23  593.07    78.1  572.67    96.7  562.29     147  549.03
   163.2  541.58   184.4  541.42   238.5  526.92     295  502.42   322.4  494.01
   390.7  487.62   696.1  485.04   716.2  478.87   731.2  473.53   871.4  473.53
   876.4  479.56  1168.1   483.8  1222.6  489.09  1404.2  496.48  1700.5  522.34
  1712.5  521.79  1724.2     514  1747.7  513.66  1769.5  524.72  1906.3  531.98
  1966.9  530.31    2033  523.24  2118.4  522.97  2152.8  525.17  2232.4  540.06
#Mann= 3 ,-1 , 0
       0     .16       0   716.2     .05       0   876.4     .16       0
Bank Sta=716.2,876.4
XS Rating Curve= 0 ,0
Exp/Cntr=0.3,0.1

Type RM Length L Ch R = 1 ,1331    ,683.2,648.4,618.1
BEGIN DESCRIPTION:
Smith Fork River 3.0
END DESCRIPTION:
XS GIS Cut Line= 3
      2006650.53       656176.27 2007331.2826855656256.618213907
      2008393.39       656741.41
#Sta/Elev= 30
       0  700.59    31.3  675.29    76.6   647.4    92.4  629.24   114.3  615.63
     142  592.62   177.3  553.21   182.5  543.69   194.9  531.47   202.4   512.4
   220.1   502.6   232.6  491.49   245.2  487.79   252.8  481.14   257.8  473.38
   391.2  473.38   396.3  480.07   484.4  478.72   630.4  481.59   916.6  503.41
  1290.4  524.19  1299.9  523.05  1315.1  513.35  1339.5  512.93  1362.1  526.88
  1466.3  532.59  1559.7  532.39  1637.6  525.21  1741.4  525.97    1853  544.17
#Mann= 3 ,-1 , 0
       0     .16       0   252.8     .05       0   396.3     .16       0
Bank Sta=252.8,396.3
XS Rating Curve= 0 ,0
Exp/Cntr=0.3,0.1

Type RM Length L Ch R = 1 ,682     ,169.4,169.8,169.1
XS GIS Cut Line= 3
2006765.20772731656915.7503399722007659.73720844656658.894184342
2008118.85207599656658.397843945
#Sta/Elev= 30
       0  618.46    19.6  616.72    40.4  608.18    53.4  600.01    63.8  589.79
    71.6  577.48    78.2  570.47    86.3     558    89.8  549.16    97.7  524.74
     101  511.32   102.4  503.88   105.5   494.9   110.7  493.11   128.9  481.17
   136.7  473.34   271.9  473.35   300.5   480.6   339.5  488.18   511.2  496.96
   801.6  502.28    1000  509.95  1071.6  515.42  1085.9  511.27  1097.5  512.75
  1114.2   511.7    1130  518.07    1155  521.55    1340     533  1389.8  531.75
#Mann= 3 , 0 , 0
       0     .16       0   128.9     .05       0   300.5     .16       0
#XS Ineff= 2 , 0
                          538.46          508.61
Permanent Ineff=
       F       F
Bank Sta=128.9,300.5
XS Rating Curve= 0 ,0
Exp/Cntr(USF)=0,0
Exp/Cntr=0.5,0.3

Type RM Length L Ch R = 1 ,512     ,122,122,123.8
XS GIS Cut Line= 4
2006799.40443784656959.9144679692006837.79751043 657069.86403335
2007423.13154811656903.1988702352008128.56886031656698.943562683
#Sta/Elev= 30
       0  605.03    43.3  596.19   119.1  571.74   130.8  559.48   133.4  550.89
   143.4  525.46   154.2  502.49   198.4  481.78   203.6  475.33   211.4  474.29
   351.7  473.34   356.9  479.82   367.3  482.16   406.4  490.09   421.9  487.89
   450.9  489.41   497.3  487.57   559.7  493.09     700  490.43   775.5  495.58
     851  495.89   895.2  500.64     906  504.11   957.7  511.38   991.5  510.87
  1014.9  505.28  1033.2  503.83    1158  511.59  1402.7  531.88  1459.5  532.15
#Mann= 3 , 0 , 0
       0     .16       0   198.4     .05       0   367.3     .16       0
#XS Ineff= 2 , 0
                          466.84          508.61
Permanent Ineff=
       F       F
Bank Sta=198.4,367.3
XS Rating Curve= 0 ,0
Exp/Cntr(USF)=0,0
Exp/Cntr=0.5,0.3

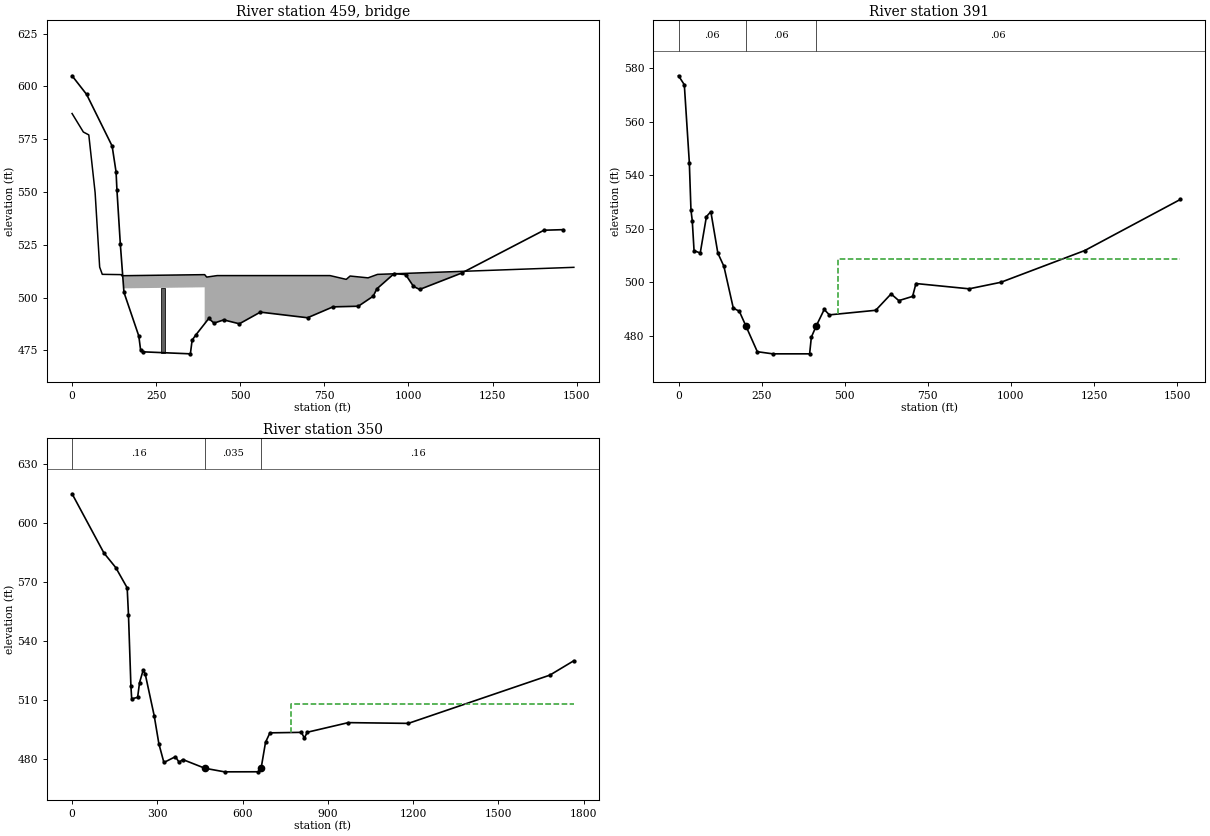
Type RM Length L Ch R = 3 ,459     ,,,
Bridge Culvert--1,0,-1,-1, 0
Deck Dist Width WeirC Skew NumUp NumDn MinLoCord MaxHiCord MaxSubmerge Is_Ogee
44,15,2.6,0, 18, 18, , , 0.98, 0, 0,0,,
       0   33.56   49.73   68.52   82.03   89.78  147.21  147.21  394.21  394.21
  400.19  431.36  766.86  815.01  826.47  879.83  907.91 1491.65
  587.15  578.39  577.03  549.71  514.42  510.99  510.85  510.34  510.85  510.85
  509.69   510.4   510.4  508.61  510.19  509.33  510.97  514.31
                                                          504.34  504.85
                                                                
      25   58.56   74.73   93.52  107.03  114.78  173.66  195.01  195.01  442.01
  442.01  456.36  791.86  840.01  851.47  904.83  932.91 1516.65
  587.15  578.39  577.03  549.71  514.42  510.99  510.47  509.06  509.06  510.05
  510.05   510.4   510.4  508.61  510.19  509.33  510.97  514.31
                                                                  503.06  504.05
                                                                
Pier Skew, UpSta & Num, DnSta & Num=  ,270.71, 2 ,318.51, 2 , 0 , 0 , 0 ,,
      12       8
       0  504.86
      12       8
       0  504.86
BR Coef=-1 , 1 , 0 ,, 0 ,,,0.8,0,2,0,
WSPro=,,,, 1 ,,,, 0 ,,,, 0 ,,,,-1 ,-1 ,-1 , 0 , 0 , 0 , 0 , 0
BC Design=,, 0 ,, 0 ,,,,,,
BC Use User HTab Curves=0
BC User HTab FreeFlow(D)= 0

Type RM Length L Ch R = 1 ,391     ,41,41.1,40.9
XS GIS Cut Line= 4
2006781.21470513657079.046330701 2006823.4036389657194.445473085
2007745.35592698656958.6837843432008161.04100977656828.394430038
#Sta/Elev= 30
       0  577.16    17.4  573.82    32.5  544.73    37.4  526.99    41.3  523.08
    46.7  511.88    65.3  510.98    83.9  524.57    97.2  526.42   118.3  510.95
   136.5  506.03   164.8  490.41   182.9  489.25   202.8  483.71   237.1  474.14
   283.5  473.34   394.5  473.34   399.7  479.57   414.4  483.76   438.4   489.9
   453.9  487.89   593.4   489.6   639.6  495.71   662.9  493.21   704.4  494.79
   714.5  499.59   874.5  497.62   969.9  500.05  1222.5  511.91  1510.1  530.98
#Mann= 3 , 0 , 0
       0     .06       0   202.8     .06       0   414.4     .06       0
#XS Ineff= 2 , 0
       0                     480       0  508.61
Permanent Ineff=
       F       F
Bank Sta=202.8,414.4
XS Rating Curve= 0 ,0
Exp/Cntr(USF)=0,0
Exp/Cntr=0.5,0.3

Type RM Length L Ch R = 1 ,350     ,,,
XS GIS Cut Line= 4
2006667.98001599656939.1779442752006772.35273501657247.860736854
2007763.96869188656999.6318671242008162.28186076656874.305916793
#Sta/Elev= 30
       0  614.86   112.2  584.69   153.7  577.29   193.9  566.97   198.5  553.19
   207.1  516.76   209.8  510.48   230.6  511.23   237.5  518.75   250.3  525.14
   257.3  523.19   288.9  501.93   305.5  487.55   323.1  478.07   363.7  481.02
   376.6  478.17   389.5  479.58   467.4  475.13   536.4  473.31   654.9  473.34
   665.2  475.16   680.7  488.34   696.2  493.16     807  493.41   817.3   490.5
   827.6  493.47   971.9  498.36  1183.2  497.98    1681  522.53  1765.6  529.88
#Mann= 3 , 0 , 0
       0     .16       0   467.4    .035       0   665.2     .16       0
#XS Ineff= 2 , 0
       0                     770       0     508
Permanent Ineff=
       F       F
Bank Sta=467.4,665.2
XS Rating Curve= 0 ,0
Exp/Cntr(USF)=0,0
Exp/Cntr=0.3,0.1
Stream Node=Caney Fork River,Reach-1         , 0 , 0 ,Upstream end
Stream Node=Caney Fork River,Reach-1         , 0 , 1 ,Downstream end
Stream Node=River (Missing) ,Reach (Missing) , 0 , 0 ,Upstream end
Stream Node=River (Missing) ,Reach (Missing) , 0 , 1 ,Downstream end
Stream Node=Smith Fork River,Reach-1         , 0 , 0 ,Upstream end
Stream Node=Smith Fork River,Reach-1         , 0 , 1 ,Downstream end
LCMann Table=0

Chan Stop Cuts=-1
Use User Specified Reach Order=0
Composite Channel Slope=5

--- SmithFork2019.g02 (geometry) ---

Geom Title=Existing Conditions 2019 Caney Fork
Program Version=5.07

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
River Reach=Caney Fork      ,1
Reach XY= 30
      2020528.93       641798.09      2017153.39        644157.2
      2012493.34       645227.982012116.31236653646213.865295207
2016408.14963141653666.4893684012020310.24152752651490.338149829
      2025342.46       654925.172026845.95374736657817.267515837
2023918.23335766658386.7081052042020294.58433804655916.103709394
2016589.04949453660044.382668846      2010758.98       661410.07
2007226.05018574657565.3276679112005479.27723171658146.526494534
2006667.61042763 662940.962722572005730.46215781664834.241284313
1995347.46243389671672.455389023      1996763.58       676699.56
      1988785.72       679537.621982795.61553441 684438.28387805
1986725.57009379688978.8688271311989006.30069465687908.960879359
1990718.15341109683947.6919410231992289.09142221684313.026362213
1995279.61461281689719.9757958321995263.95742333693420.291576176
1996605.25665541696228.1475561831994340.18324403697063.197661761
1990305.84742146693550.768155172      1985514.67       694101.78

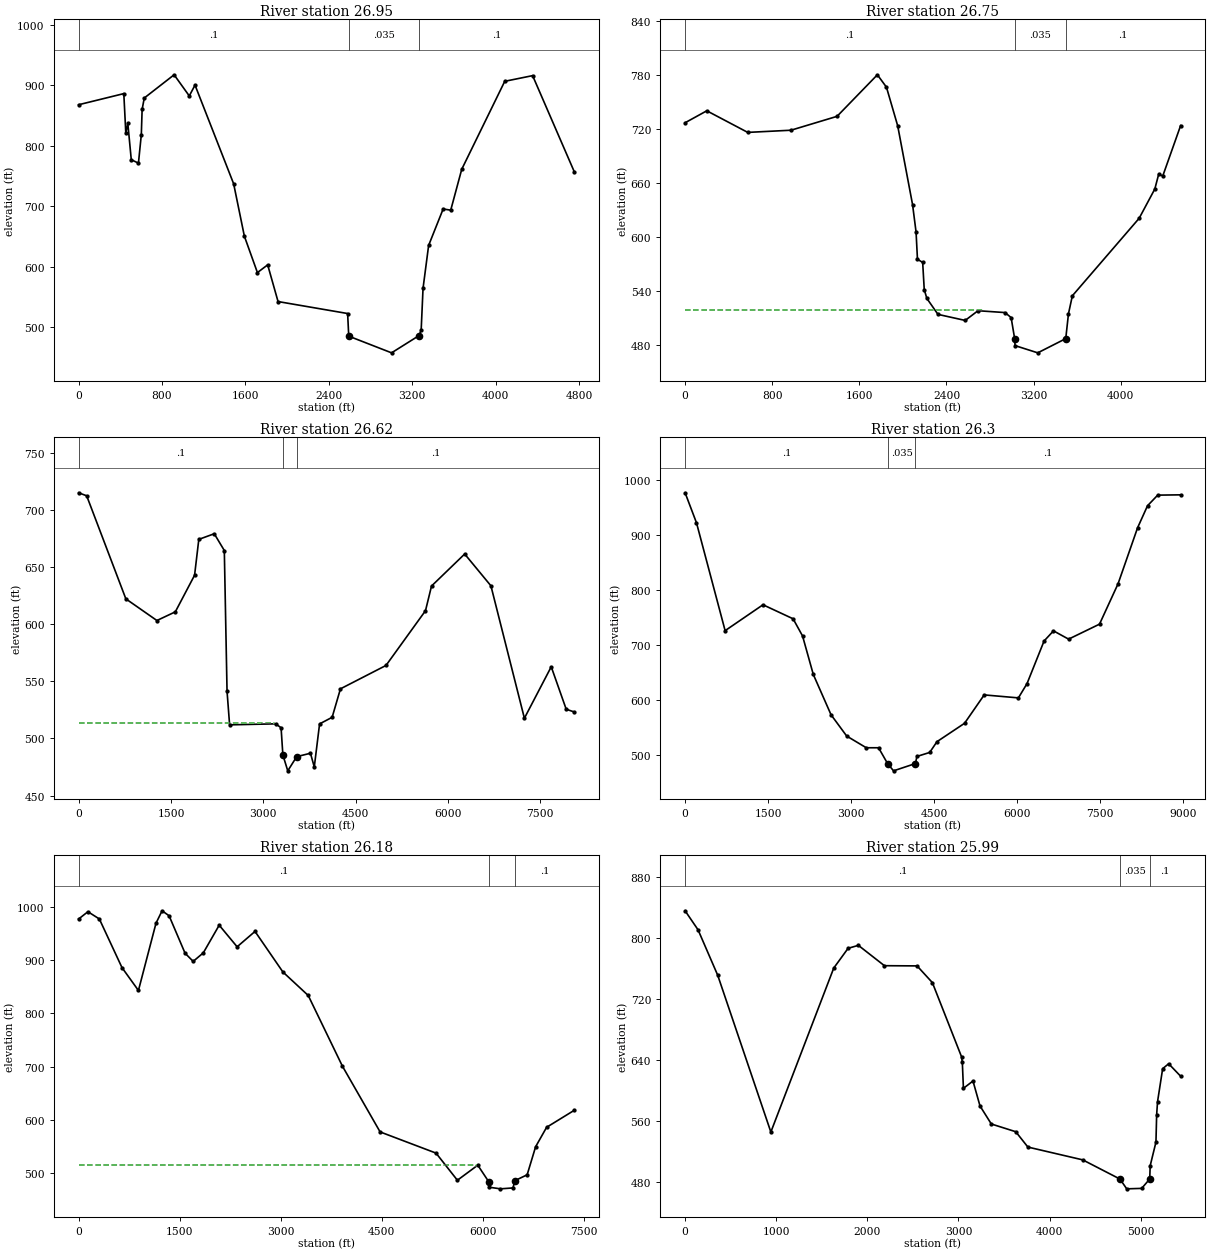
Type RM Length L Ch R = 1 ,26.95   ,1007.6,1042.2,1067.6
BEGIN DESCRIPTION:
43969.28
END DESCRIPTION:
XS GIS Cut Line= 6
      2017791.37       640312.07      2018375.64       641574.95
      2018714.11       641739.88      2018913.64       641848.07
      2019904.56       642796.92      2020809.91       643847.42
#Sta/Elev= 30
       0  867.73   433.4  886.11   452.6  820.63   471.9  836.88     505  776.81
   573.8  771.17   601.4  818.33   609.1  860.06   629.8  878.86     916  917.26
  1061.4  882.29  1116.5  900.19  1487.1  736.97    1590  650.33  1715.1   590.2
  1813.5  602.97    1913  542.29  2580.5   522.5  2591.1  485.09    3002   457.5
  3263.5  485.81  3285.9  494.84  3303.9  564.17  3357.5  635.12  3496.7  695.34
  3569.5  693.42  3675.1     761  4087.7  906.47    4355  915.85  4753.7  757.32
#Mann= 3 , 0 , 0
       0      .1       0  2591.1    .035       0  3263.5      .1       0
Bank Sta=2591.1,3263.5
XS Rating Curve= 0 ,0
Exp/Cntr=0.3,0.1

Type RM Length L Ch R = 1 ,26.75   ,640.8,666.3,687.2
BEGIN DESCRIPTION:
43651.69
END DESCRIPTION:
XS GIS Cut Line= 6
      2017403.74       640253.35      2018017.99       642143.95
      2018437.05       642668.71      2018928.73       643314.05
      2019417.25       643650.76      2019898.86        643719.5
#Sta/Elev= 30
       0  727.08   199.3  740.38   575.2  716.34   972.1  718.76  1395.3  734.21
  1765.7  780.48    1849  766.69  1952.2   723.7  2088.9  635.87  2120.9  605.48
  2133.8  575.15  2181.7  571.56    2196  541.36  2220.1  531.51  2322.1  513.76
    2572  507.03  2689.8  517.83  2938.1  515.77  2993.9  510.18  3026.1  486.89
 3030.07     479  3238.4  470.95  3495.4  486.76  3520.5  514.45  3556.2  534.47
  4169.4  620.71  4313.4  653.33  4348.7  669.72  4386.6  667.89  4550.5  723.97
#Mann= 3 , 0 , 0
       0      .1       0  3026.1    .035       0  3495.4      .1       0
#XS Ineff= 2 , 0
          2732.1  518.29
Permanent Ineff=
       F       F
Bank Sta=3026.1,3495.4
XS Rating Curve= 0 ,0
Exp/Cntr=0.3,0.1

Type RM Length L Ch R = 1 ,26.62   ,1712.2,1723.4,1734.5
BEGIN DESCRIPTION:
43448.64
END DESCRIPTION:
XS GIS Cut Line= 6
      2017239.33       640100.66      2017519.96       642400.32
      2017866.05       642884.03      2018258.42       643519.37
      2018650.31       644110.652022323.20875947644378.224875947
#Sta/Elev= 30
       0  715.01   130.7  712.37   767.2  622.15  1271.6  603.19  1570.8  610.78
  1883.6  642.83  1952.3  674.22  2203.4  679.15  2366.7  664.47  2411.1   541.2
  2452.7  511.86  3199.9  512.74  3288.9  509.34  3317.9485.5318 3397.53   471.6
 3542.23     484 3766.03     487 3828.23     475  3914.4  512.69  4118.3  518.46
  4253.3  543.38  4993.4  563.86    5635  611.79  5732.8  633.37  6271.6  661.41
  6697.7  633.58  7241.6  517.64  7677.7  562.71  7920.8  525.53  8050.3  523.16
#Mann= 3 , 0 , 0
       0      .1       0  3317.9    .035       0 3542.23      .1       0
#XS Ineff= 2 , 0
         3175.07  513.29
Permanent Ineff=
       F       F
Bank Sta=3317.9,3542.23
XS Rating Curve= 0 ,0
Exp/Cntr=0.3,0.1

Type RM Length L Ch R = 1 ,26.3    ,600.7,627.5,650.4
BEGIN DESCRIPTION:
42923.46
END DESCRIPTION:
XS GIS Cut Line= 6
      2015806.38       640511.75      2016229.58       643474.13
      2016633.32       644142.44      2016835.23       644482.09
      2016765.42       645947.622020009.20644555 646654.76438931
#Sta/Elev= 30
       0  976.86   205.7  922.31   723.4  726.17  1407.8  773.24  1951.6  747.75
  2122.5  716.57  2316.9  646.53    2638  573.16  2920.5  534.54  3274.3  513.27
  3496.3  513.26  3658.7  484.62    3767   471.3  4163.5  484.59    4189  497.46
  4420.3  504.73  4552.1  524.34  5050.2  557.75  5405.4  609.36  6023.3  603.94
  6179.2  629.87  6487.5  707.36  6657.7  725.81  6930.8  710.75  7489.3     738
  7824.5  811.38  8177.6  913.29  8357.2   953.3  8540.9  972.58  8955.5  973.12
#Mann= 3 , 0 , 0
       0      .1       0  3658.7    .035       0  4163.5      .1       0
Bank Sta=3658.7,4163.5
XS Rating Curve= 0 ,0
Exp/Cntr=0.3,0.1

Type RM Length L Ch R = 1 ,26.18   ,927.8,1004.5,1037.6
BEGIN DESCRIPTION:
42732.33
END DESCRIPTION:
XS GIS Cut Line= 6
2015074.67841125638808.000267255      2014789.85       642462.87
      2015371.38       643980.67      2015949.04       644105.08
      2016310.02        644884.6      2016088.46       645456.52
#Sta/Elev= 30
       0  976.96   137.8  990.63   307.5  977.03   643.7  885.81   887.6  842.99
  1148.4  969.12  1238.6  992.38  1342.7     983  1579.7  912.84    1700  897.51
  1850.5  913.51  2086.2  965.37  2352.3  924.87  2617.8  953.69  3031.5  877.69
  3407.7  833.58  3914.9  701.12  4474.4  577.87  5304.3  538.14  5621.4  487.28
    5924  515.53  6086.5   484.5  6091.4  474.24  6260.8  471.17  6446.5  472.87
  6474.4  486.51  6656.7  497.48  6782.3  550.03  6945.5  586.52  7354.6  618.29
#Mann= 3 , 0 , 0
       0      .1       0  6086.5    .035       0  6474.4      .1       0
#XS Ineff= 2 , 0
         5897.37  515.45
Permanent Ineff=
       F       F
Bank Sta=6086.5,6474.4
XS Rating Curve= 0 ,0
Exp/Cntr=0.3,0.1

Type RM Length L Ch R = 1 ,25.99   ,1107.4,1113.9,1124.1
BEGIN DESCRIPTION:
42426.14
END DESCRIPTION:
XS GIS Cut Line= 6
2011545.23293897 641635.94342561      2013544.71        643500.6
      2014180.29       643936.82      2014738.93       644421.86
      2015160.82       644598.28      2015278.68        645325.3
#Sta/Elev= 30
       0   836.3   142.1  811.35   357.9  751.75   941.2  546.06  1631.4  761.15
  1788.8  787.06  1901.6  790.95  2187.5  764.26  2545.9  763.99    2714  742.03
    3034  644.75  3042.7  637.29  3054.6  603.38  3159.5  612.98  3236.6  580.23
  3360.9  556.59  3629.1  546.45    3762  526.33  4364.1  509.53  4772.4  484.38
  4846.7  471.53    5011  472.13  5099.2  484.43  5104.3  501.84  5167.6  532.86
  5175.2  568.67  5185.3  586.07  5241.1  629.13  5306.9  635.64  5438.5  619.27
#Mann= 3 , 0 , 0
       0      .1       0  4772.4    .035       0  5099.2      .1       0
Bank Sta=4772.4,5099.2
XS Rating Curve= 0 ,0
Exp/Cntr=0.3,0.1

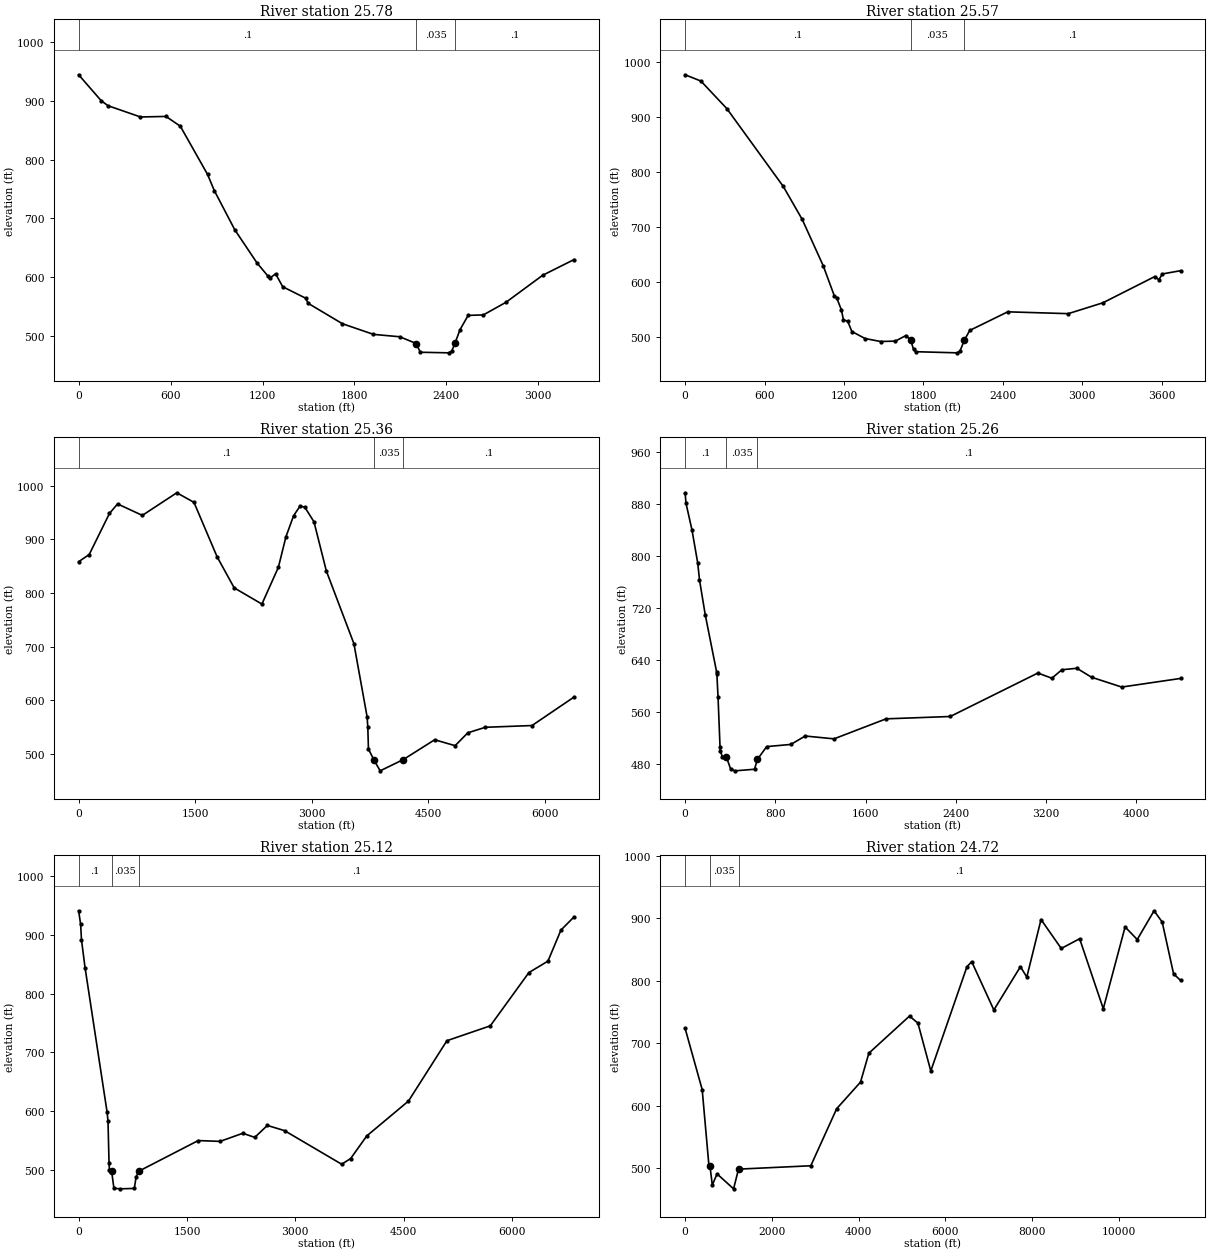
Type RM Length L Ch R = 1 ,25.78   ,1106.5,1099,1091
BEGIN DESCRIPTION:
42086.71
END DESCRIPTION:
XS GIS Cut Line= 6
      2012740.83       643189.69      2013787.75       644006.37
       2013968.1       644390.35      2014059.45       644698.06
      2014131.16        645237.5      2014655.35       645562.25
#Sta/Elev= 30
       0  944.11   146.8  900.21   191.6  891.57   403.6  872.43   570.2  873.32
   663.6  856.72   841.2  774.86   885.6  747.21  1018.7  680.89  1164.1  624.36
  1237.5  601.38  1250.2  598.98  1285.5  605.95  1331.8  583.93  1481.4   564.5
  1497.9  555.75  1721.7  521.06  1924.2     503  2095.5  498.95  2203.8  487.42
  2229.2  472.63    2414  471.63  2434.2  474.33  2456.2  487.97  2488.9  511.04
  2541.9  535.24  2641.4   536.1  2788.8  557.52  3028.1  603.41  3233.8   630.2
#Mann= 3 , 0 , 0
       0      .1       0  2203.8    .035       0  2456.2      .1       0
Bank Sta=2203.8,2456.2
XS Rating Curve= 0 ,0
Exp/Cntr=0.3,0.1

Type RM Length L Ch R = 1 ,25.57   ,1250.1,1075,879.9
BEGIN DESCRIPTION:
41751.80
END DESCRIPTION:
XS GIS Cut Line= 5
      2012646.89       643283.66      2012935.02       644698.61
      2013063.54       645402.83      2013363.09       645587.14
      2014549.63       645914.61
#Sta/Elev= 30
       0  976.28   119.1  964.95   315.6  914.77   741.6  773.58   884.5  713.75
  1042.7  629.96  1126.7  575.24  1144.7  571.66  1180.5  549.39  1195.8  531.83
  1228.5  528.55  1259.6  510.34  1359.1  497.63  1476.3  492.19  1588.1  492.92
  1666.9  502.95  1702.5  495.73 1725.08     478 1741.03  473.68    2055  471.63
  2075.2  474.33  2108.8  494.46  2149.7  512.31  2436.6  546.06  2893.8  542.74
  3155.7   562.5  3547.4   610.1    3578  604.29  3604.4  614.81  3742.4  620.72
#Mann= 3 , 0 , 0
       0      .1       0  1702.5    .035       0  2108.8      .1       0
Bank Sta=1702.5,2108.8
XS Rating Curve= 0 ,0
Exp/Cntr=0.3,0.1

Type RM Length L Ch R = 1 ,25.36   ,678.4,545,435.9
BEGIN DESCRIPTION:
41417.49
END DESCRIPTION:
XS GIS Cut Line= 6
      2009135.25       643332.79      2009664.38       644558.09
      2011258.89       645179.25      2012427.85       645762.13
      2012892.64       645933.71      2014420.42       646032.09
#Sta/Elev= 30
       0  858.47   136.3  871.93   396.7  948.53   501.2  966.35   819.8  944.92
  1263.6  987.13  1484.6  969.28  1782.2  867.68  2002.4  809.67  2359.2  779.42
  2571.2   848.1  2668.5  905.08  2766.9  944.24    2850  962.39  2911.3  960.26
  3029.5  932.91  3188.5  841.22  3543.3  705.55  3713.8  568.49  3722.1  549.65
  3730.5  508.83  3803.1  487.99  3881.4   468.2 4179.54489.2646  4582.6  526.18
  4846.4  515.17  5009.3  539.17  5235.6  549.48    5836  552.74  6378.5  606.09
#Mann= 3 , 0 , 0
       0      .1       0  3803.1    .035       0 4179.54      .1       0
Bank Sta=3803.1,4179.54
XS Rating Curve= 0 ,0
Exp/Cntr=0.3,0.1

Type RM Length L Ch R = 1 ,25.26   ,831,762.7,717
BEGIN DESCRIPTION:
41250.64
END DESCRIPTION:
XS GIS Cut Line= 6
      2011567.23       646248.172012444.02422947646044.551850897
       2013652.7       646096.66      2014486.13       646061.05
      2014803.05        645620.7      2015675.37        645380.8
#Sta/Elev= 30
       0  897.67       8  881.55    60.9  840.49   112.2   789.3   127.6  763.64
     179  709.53   279.1  622.25   281.6  618.93   291.9   583.9   309.9  505.86
   312.4  500.21   330.4  491.55     366  491.05  404.35  472.34  442.35   469.8
  615.35  472.25     641  487.48   723.1   507.1   937.7  510.44  1064.7   523.4
  1320.2  519.03  1781.5  549.81  2350.5  553.42  3127.3   620.3  3251.4  612.31
  3340.1  625.35    3473  627.61  3603.3  613.83  3870.4  598.72  4392.9  612.01
#Mann= 3 , 0 , 0
       0      .1       0     366    .035       0     641      .1       0
Bank Sta=366,641
XS Rating Curve= 0 ,0
Exp/Cntr=0.3,0.1

Type RM Length L Ch R = 1 ,25.12   ,2117.1,2111.3,2120.3
BEGIN DESCRIPTION:
41026.12
END DESCRIPTION:
XS GIS Cut Line= 6
      2011983.61       647108.61      2012907.02       646494.79
      2013443.51       646359.45      2013997.94       646268.09
      2018214.06       646959.66      2018567.38       646876.19
#Sta/Elev= 30
       0  940.43    27.6  917.54    39.6  890.88    89.2  843.64     394  598.72
   406.6  583.63   420.8  512.17   426.4   501.3   455.3   499.7   488.4   469.6
   571.2   468.6   770.8   469.3   796.1  489.14   835.1  498.68  1654.9  550.48
  1958.2  549.14  2272.7  562.89    2438  555.89  2612.2  576.19  2849.9  567.38
  3641.3  510.33  3765.5  520.01  3988.4  558.39    4566  617.56    5098  719.97
  5698.5   745.2    6233  835.61  6496.5     855  6676.3  907.62  6859.5   930.3
#Mann= 3 , 0 , 0
       0      .1       0   455.3    .035       0   835.1      .1       0
Bank Sta=455.3,835.1
XS Rating Curve= 0 ,0
Exp/Cntr=0.3,0.1

Type RM Length L Ch R = 1 ,24.72   ,1273.6,1328.6,1458.2
BEGIN DESCRIPTION:
40382.69
END DESCRIPTION:
XS GIS Cut Line= 6
      2013076.52       648743.89      2013386.31        648740.7
      2014470.36       647914.19      2015506.97       647993.33
      2019001.14        649614.4      2023816.73       649626.15
#Sta/Elev= 30
       0  723.96   393.9  625.87   548.6  504.54   573.7  503.15   627.4   472.9
   736.2  490.88  1117.3   466.9  1231.2 498.473    2897  503.85  3493.5  595.24
  4043.2  637.89  4234.9  684.15  5172.1  743.63  5365.9  732.33  5662.9  655.71
  6495.7   822.6  6605.7  830.76    7116  753.43  7728.2  822.68  7875.7  806.08
  8203.2  898.28  8669.1  851.93  9093.2  867.46  9638.2   755.4 10140.7  886.41
 10420.7  866.26 10808.2  912.28 10995.7   894.3 11258.2  811.25 11420.9  800.63
#Mann= 3 , 0 , 0
       0      .1       0   573.7    .035       0  1231.2      .1       0
Bank Sta=573.7,1231.2
XS Rating Curve= 0 ,0
Exp/Cntr=0.3,0.1

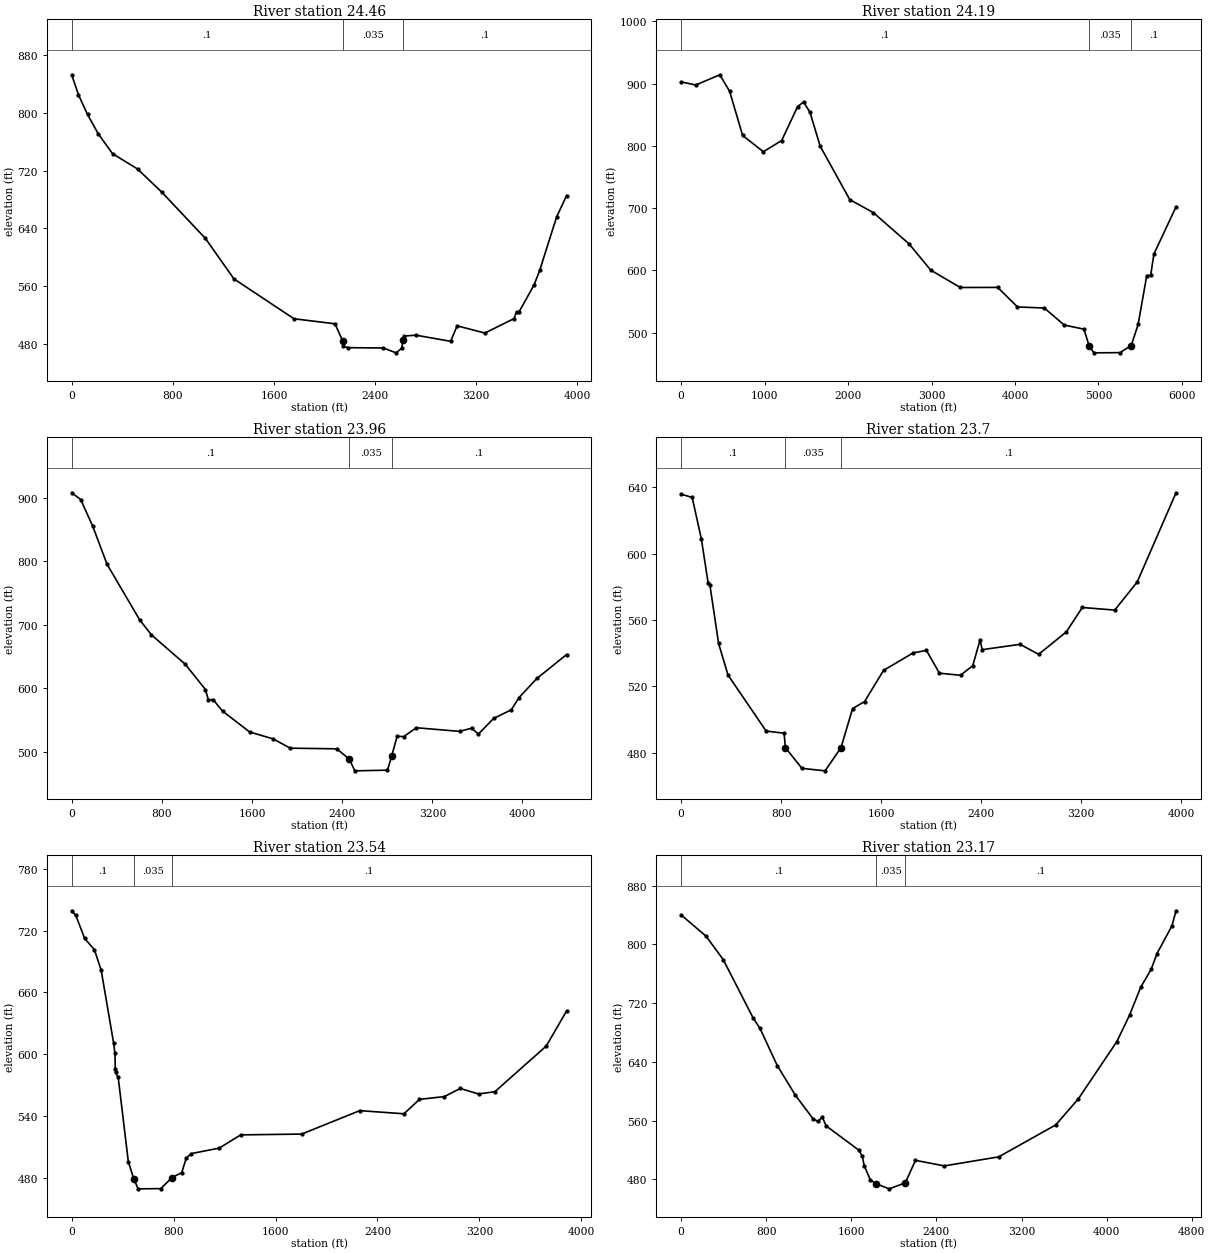
Type RM Length L Ch R = 1 ,24.46   ,1403.3,1427.3,1534.8
BEGIN DESCRIPTION:
39977.92
END DESCRIPTION:
XS GIS Cut Line= 5
      2012364.99       649250.31      2014189.77       649679.34
2015221.80392595649107.319906158      2015525.19       648832.02
      2015972.74       648785.73
#Sta/Elev= 30
       0  852.63      53  825.06   124.9  797.74   209.6  770.99   322.6  743.55
   520.4  722.31     713  690.12  1057.1  626.29  1283.1  570.23  1758.2  515.06
  2082.4  508.11  2142.4  484.67  2149.6  476.71 2186.91  475.08  2463.6  474.61
  2566.2  467.91  2608.9  474.11  2621.7  485.54  2629.1   491.1  2722.7  492.34
  2997.1  483.84  3048.5  505.28  3268.1   495.3  3498.2  515.26  3518.3  524.86
  3538.4  524.68  3656.6   561.7  3701.8  582.07    3835  655.74  3914.1  685.45
#Mann= 3 , 0 , 0
       0      .1       0  2142.4    .035       0  2621.7      .1       0
Bank Sta=2142.4,2621.7
XS Rating Curve= 0 ,0
Exp/Cntr=0.3,0.1

Type RM Length L Ch R = 1 ,24.19   ,1202.2,1230.7,1294.7
BEGIN DESCRIPTION:
39542.25
END DESCRIPTION:
XS GIS Cut Line= 6
      2010313.07       650690.09      2011779.04       650383.65
      2014411.16       650916.69      2014900.37       650869.94
 2015654.2105353650563.712248777      2015934.96       650223.67
#Sta/Elev= 30
       0  902.58   174.7  897.61   462.9  914.03   580.8  887.47   736.6  816.56
     985  790.44    1204  808.43  1395.5  862.89    1467  870.37  1543.5  853.78
    1666  799.29  2020.6  713.53  2303.1  692.58  2731.6  642.38  2990.3  600.36
  3344.4   572.4  3793.4  572.52  4030.6  541.14  4351.9  539.44  4590.5  512.06
  4826.6  505.47 4890.77  477.97  4947.7  467.44 5258.16  467.77 5393.15     479
  5476.1  513.01  5579.4  591.36  5626.6  591.93  5665.5  626.22  5930.3   701.8
#Mann= 3 , 0 , 0
       0      .1       0 4890.77    .035       0 5393.15      .1       0
Bank Sta=4890.77,5393.15
XS Rating Curve= 0 ,0
Exp/Cntr=0.3,0.1

Type RM Length L Ch R = 1 ,23.96   ,1447.6,1405.9,1362.4
BEGIN DESCRIPTION:
39178.58
END DESCRIPTION:
XS GIS Cut Line= 6
      2013539.52        653314.22014815.08787687652039.243935997
2015366.80710939651950.2028435562015903.39075074651840.595046921
      2016229.95       651502.61      2016546.34        650542.3
#Sta/Elev= 30
       0  907.73    79.7  897.07   185.8  855.43   313.5  795.26   603.4  707.64
   707.7  684.15  1006.5  638.18  1186.6  598.21  1211.5   582.4  1255.7  582.13
    1339   564.1  1579.1  531.39  1787.7  520.51  1939.5  505.94    2352  504.89
  2463.7  488.67  2511.8  470.27 2802.08  471.33  2839.3  493.71  2887.5  524.55
    2947  524.17  3057.4  538.08  3442.4  532.35  3548.2   537.4  3608.7  528.13
  3742.9  552.62  3900.9  566.31  3969.3  585.54  4127.2  615.55  4391.1   653.2
#Mann= 3 , 0 , 0
       0      .1       0  2463.7    .035       0  2839.3      .1       0
Bank Sta=2463.7,2839.3
XS Rating Curve= 0 ,0
Exp/Cntr=0.3,0.1

Type RM Length L Ch R = 1 ,23.7    ,1075.4,803,470.8
BEGIN DESCRIPTION:
38731.23
END DESCRIPTION:
XS GIS Cut Line= 6
      2015190.56       653774.35      2015416.87       653490.71
 2016358.9351002653096.441275658      2016744.88        651924.5
      2016802.99       651496.71      2016640.29       650612.77
#Sta/Elev= 30
       0  635.78    88.2  633.76     162   608.6   215.2  582.52   229.5  581.29
   299.3  545.94   374.3  526.93   679.6  493.16   823.3  491.85   834.1  483.12
   966.2   470.7  1151.1   469.2 1278.64  483.12  1371.6  506.73  1466.9  510.84
  1619.2  529.66  1856.3  540.22  1962.5  541.69    2066  527.98  2235.1  526.74
  2332.9  532.51  2391.6  548.05  2408.1  542.15  2711.6  545.36    2860  539.35
  3082.1  552.87  3209.2  567.54  3468.6  565.97  3648.4  582.83  3959.2   636.6
#Mann= 3 , 0 , 0
       0      .1       0   834.1    .035       0 1278.64      .1       0
Bank Sta=834.1,1278.64
XS Rating Curve= 0 ,0
Exp/Cntr=0.3,0.1

Type RM Length L Ch R = 1 ,23.54   ,2083.2,1951.1,1835.5
BEGIN DESCRIPTION:
38469.10
END DESCRIPTION:
XS GIS Cut Line= 6
      2016852.05       654236.54      2016639.39653841.355369013
2016602.32187928653340.550202828      2016835.95       652673.77
      2016922.19        651634.6      2016781.24       650471.81
#Sta/Elev= 30
       0  739.24    32.6  734.68   100.9  712.47   178.4  701.36   231.3  681.47
   328.1  611.23   339.2  600.81     342  585.75   343.9  582.31   364.8  577.44
   444.2  495.57  486.66     479   521.1  469.13   698.8  469.33  787.15  480.09
   863.4  484.81   898.5  498.85   938.6  503.39    1157  508.65  1326.7  521.56
    1805  522.32  2260.8  545.09  2608.1  542.04  2729.6  556.07  2923.5  558.69
  3049.5  566.62    3193  561.29  3321.4   563.5  3724.3  607.79  3884.1  641.87
#Mann= 3 , 0 , 0
       0      .1       0  486.66    .035       0  787.15      .1       0
Bank Sta=486.66,787.15
XS Rating Curve= 0 ,0
Exp/Cntr=0.3,0.1

Type RM Length L Ch R = 1 ,23.17   ,1043.5,975.7,971.7
BEGIN DESCRIPTION:
37861.89
END DESCRIPTION:
XS GIS Cut Line= 6
       2019361.7       654108.192018368.56409113652702.772273392
2018040.39015026652370.413179824      2017556.98       651864.05
      2017522.16       651520.54      2017717.35       650114.76
#Sta/Elev= 30
       0  840.21   234.2  811.23   395.3  779.42     676  700.03   741.2  685.56
   903.4  635.03  1074.7  594.39  1243.2  561.89  1289.1  558.91  1325.9     565
  1362.6  552.86  1671.8  519.64  1702.5  511.38  1720.9  498.81 1778.08  479.36
  1833.4  473.87  1955.7  467.07 2106.66   475.2  2203.1  505.91  2473.6  498.32
  2985.3  510.64  3521.2  554.12  3733.2  589.45  4096.7  667.78  4216.1  703.89
  4321.3  741.95  4418.3  766.01    4474  787.62  4614.1  825.32  4652.6   845.9
#Mann= 3 , 0 , 0
       0      .1       0  1833.4    .035       0 2106.66      .1       0
Bank Sta=1833.4,2106.66
XS Rating Curve= 0 ,0
Exp/Cntr=0.3,0.1

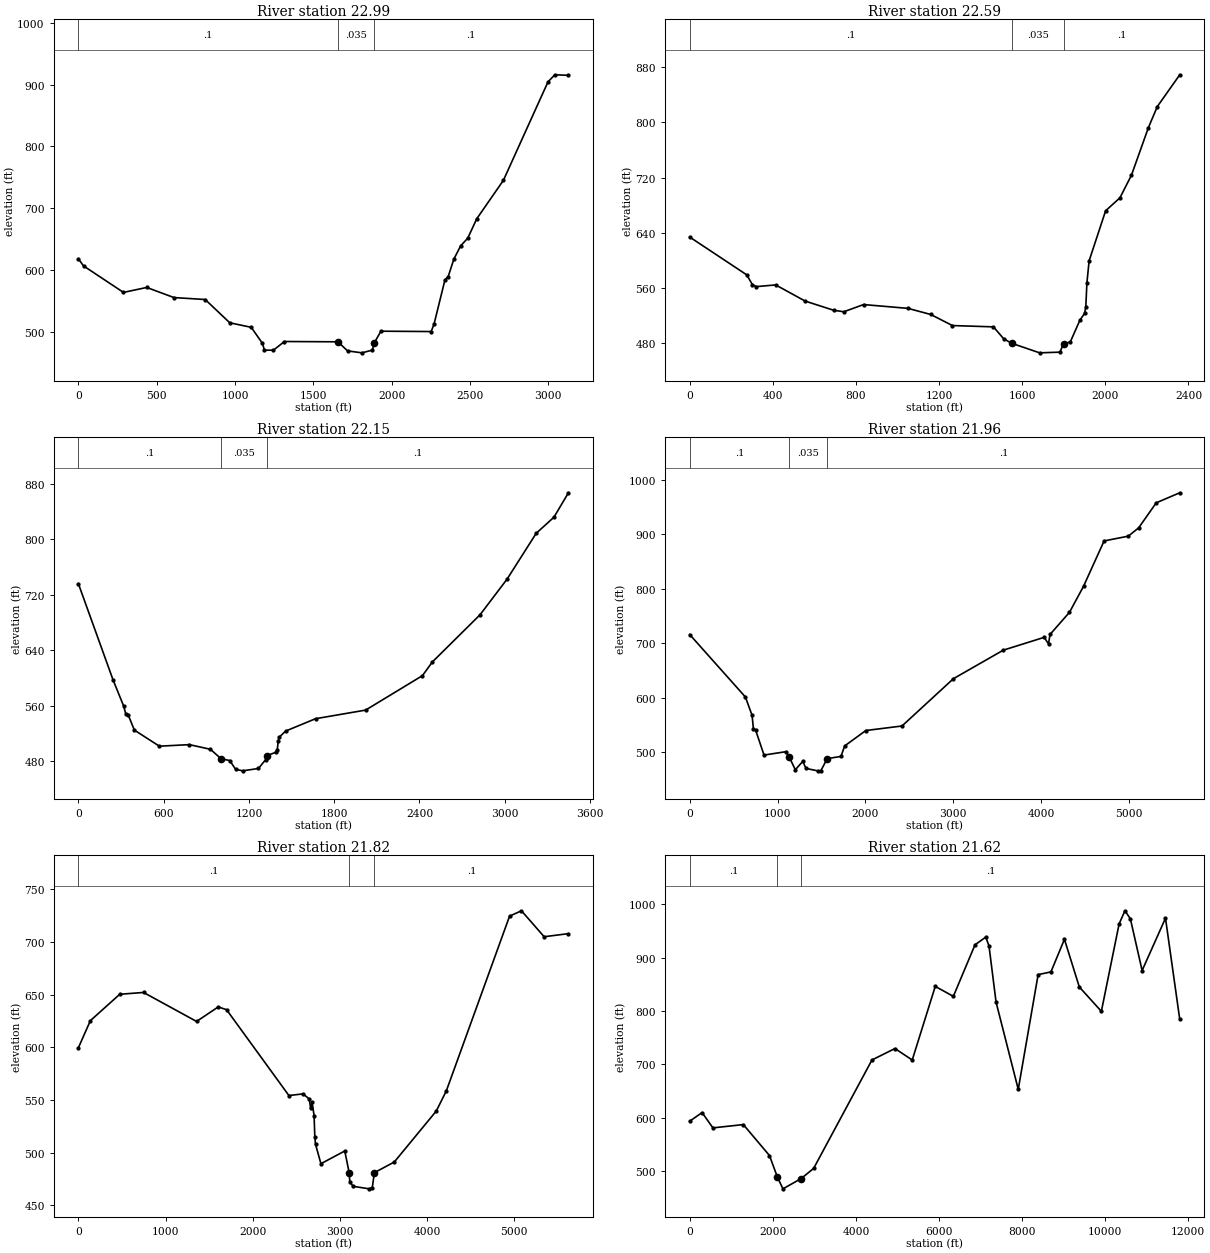
Type RM Length L Ch R = 1 ,22.99   ,1458.8,2081.3,2233.5
BEGIN DESCRIPTION:
37558.08
END DESCRIPTION:
XS GIS Cut Line= 6
      2019602.76       653218.35      2019598.89       652843.29
      2019342.81       652262.43      2018658.97       651623.46
      2018580.06       651302.86       2018633.8       650451.05
#Sta/Elev= 30
       0   618.6      33  607.07     288  564.27   436.6  572.25   610.5  555.94
   809.9  552.79   966.9  515.19    1104   507.9  1175.8  481.84  1188.1  470.96
  1245.6  470.96  1316.1  484.95  1657.4  484.48  1719.4  469.76  1811.5  466.66
  1877.9  471.16    1888  481.91    1932  501.62  2252.8  501.05  2270.8  512.54
  2341.1  584.59  2361.1  589.38  2397.5  617.77  2441.3  639.55  2486.4  651.73
    2544  683.17  2714.3  745.29  2998.9  904.27  3042.5  915.76  3129.5  914.87
#Mann= 3 , 0 , 0
       0      .1       0  1657.4    .035       0    1888      .1       0
Bank Sta=1657.4,1888
XS Rating Curve= 0 ,0
Exp/Cntr=0.3,0.1

Type RM Length L Ch R = 1 ,22.59   ,2310.8,2366.4,2403.9
BEGIN DESCRIPTION:
36958.20
END DESCRIPTION:
XS GIS Cut Line= 6
      2019946.45       653204.37      2020312.93       652367.03
2020550.40442062 651840.75661813      2020577.79       651780.81
2020698.33598226651488.381586581      2020538.79         651031.
#Sta/Elev= 30
       0  633.67   274.5  578.82   301.8  564.65   320.9  561.76   413.7  564.24
   555.2  540.82   692.1  527.54   741.5  525.29   836.7  535.74  1050.3  530.22
  1159.9  521.34  1264.2  505.28  1461.6   503.4  1511.1  485.97 1550.47  479.46
  1683.6  465.71  1781.5  466.71  1798.6     479  1830.9  481.28  1877.3  512.94
    1900  522.96  1905.9  532.32  1911.2  567.09  1921.8  599.14  2001.2  671.76
  2070.1  690.57  2125.7   723.5  2207.1  792.42  2250.1  823.01    2358  869.05
#Mann= 3 , 0 , 0
       0      .1       0 1550.47    .035       0  1798.6      .1       0
#XS Ineff= 2 , 0
            .492 620.345
Permanent Ineff=
       F       F
Bank Sta=1550.47,1798.6
XS Rating Curve= 0 ,0
Exp/Cntr=0.3,0.1

Type RM Length L Ch R = 1 ,22.15   ,1015.8,987.9,974.8
BEGIN DESCRIPTION:
36240.60
END DESCRIPTION:
XS GIS Cut Line= 6
      2021864.67       653759.67      2022549.34       653010.84
2022777.29794575652677.883269059      2022559.98       652020.89
      2022540.53       651057.21      2022442.92        650699.1
#Sta/Elev= 30
       0  735.94   244.1  597.09   319.1  559.18   332.9  548.54   350.6  546.59
   393.9   524.7   570.1  501.49   780.7  503.74   929.3  497.01  1003.2  483.49
 1064.94480.7564    1106  468.24  1156.1  465.94  1267.1  469.34  1317.8  482.13
  1326.5  487.82  1393.3  493.05  1399.6  496.19  1405.6  508.42  1411.7  514.12
  1457.6  523.23  1668.7  541.12  2020.9  553.53  2420.8  603.25  2490.9  623.03
  2825.9  690.99    3016  742.38  3221.1  808.53  3346.1  831.75  3447.8  866.95
#Mann= 3 , 0 , 0
       0      .1       0  1003.2    .035       0  1326.5      .1       0
Bank Sta=1003.2,1326.5
XS Rating Curve= 0 ,0
Exp/Cntr=0.3,0.1

Type RM Length L Ch R = 1 ,21.96   ,743.4,732.5,728
BEGIN DESCRIPTION:
35935.38
END DESCRIPTION:
XS GIS Cut Line= 6
      2022298.88       653982.45      2023080.57       654005.64
      2023511.38       653344.79      2023567.34        652708.6
      2024573.43       650589.12      2024625.58       649585.72
#Sta/Elev= 30
       0  715.85   633.8   601.2   709.7  567.63     725  542.77   750.9  540.03
   845.6  494.65  1096.5   500.9  1129.1  492.01  1202.1   467.7  1286.2  483.09
  1323.4   470.2  1454.8   465.7  1492.5   465.9  1564.5  488.12  1721.1   492.1
  1763.3   511.4  2004.5   539.7  2415.8  548.01  3000.2  634.75  3568.2  687.15
  4033.1  710.66    4083  698.65  4099.9  715.95  4321.4  756.65  4480.9  804.27
  4715.3  887.62  4990.7  896.37  5108.4  911.58  5308.6  957.58  5576.2  975.97
#Mann= 3 , 0 , 0
       0      .1       0  1129.1    .035       0  1564.5      .1       0
Bank Sta=1129.1,1564.5
XS Rating Curve= 0 ,0
Exp/Cntr=0.3,0.1

Type RM Length L Ch R = 1 ,21.82   ,1058.9,1064.1,1078.6
BEGIN DESCRIPTION:
35712.24
END DESCRIPTION:
XS GIS Cut Line= 6
      2021041.52       654848.83      2022867.31       654679.42
      2023564.77       654521.41      2024211.89       653556.67
      2025119.11       652556.98      2025239.31       652014.49
#Sta/Elev= 30
       0  599.57   138.1  625.39   474.6  650.39   747.6  652.11  1355.8  624.61
  1604.4  638.38  1699.8  635.76  2414.8  554.32  2576.2  555.88  2648.4  551.11
  2664.3  542.06  2680.8  547.82  2703.7  535.32  2712.2   515.1    2720  508.15
  2782.1  489.63  3055.5  501.72  3107.8  480.41  3112.7   472.6  3151.1   468.2
  3336.4   465.8  3371.3   466.9  3395.1  481.15  3623.2  491.22  4105.3  539.62
  4220.7  558.77  4945.9  724.52  5082.2   729.6  5342.4  704.97  5620.9  707.91
#Mann= 3 , 0 , 0
       0      .1       0  3107.8    .035       0  3395.1      .1       0
Bank Sta=3107.8,3395.1
XS Rating Curve= 0 ,0
Exp/Cntr=0.3,0.1

Type RM Length L Ch R = 1 ,21.62   ,1774.4,1877.8,2014.7
BEGIN DESCRIPTION:
35387.86
END DESCRIPTION:
XS GIS Cut Line= 6
      2023906.88       656539.24      2024124.95       656528.58
      2025173.88       653942.09      2025124.89       652968.83
      2026081.71       649159.49      2029671.24       647801.92
#Sta/Elev= 30
       0   593.5   298.2  609.72   558.8  581.03    1291  587.21  1920.3  529.21
  2111.3  488.77  2244.4  466.81  2681.8  485.97  2983.4  505.11  4387.6  708.32
  4940.6   729.7  5356.5  708.18  5910.7  846.12  6346.4  827.51  6867.6  924.07
  7126.4  938.46  7204.7  921.92  7374.4  816.67  7908.4  653.26  8386.7  868.16
  8695.2  873.32  9020.2  934.41  9378.1  845.08  9909.1  799.42   10337  963.47
 10476.7  987.82 10607.3  972.79   10890  875.86 11452.6  973.98 11796.2  784.19
#Mann= 3 , 0 , 0
       0      .1       0  2111.3    .035       0  2681.8      .1       0
Bank Sta=2111.3,2681.8
XS Rating Curve= 0 ,0
Exp/Cntr=0.3,0.1